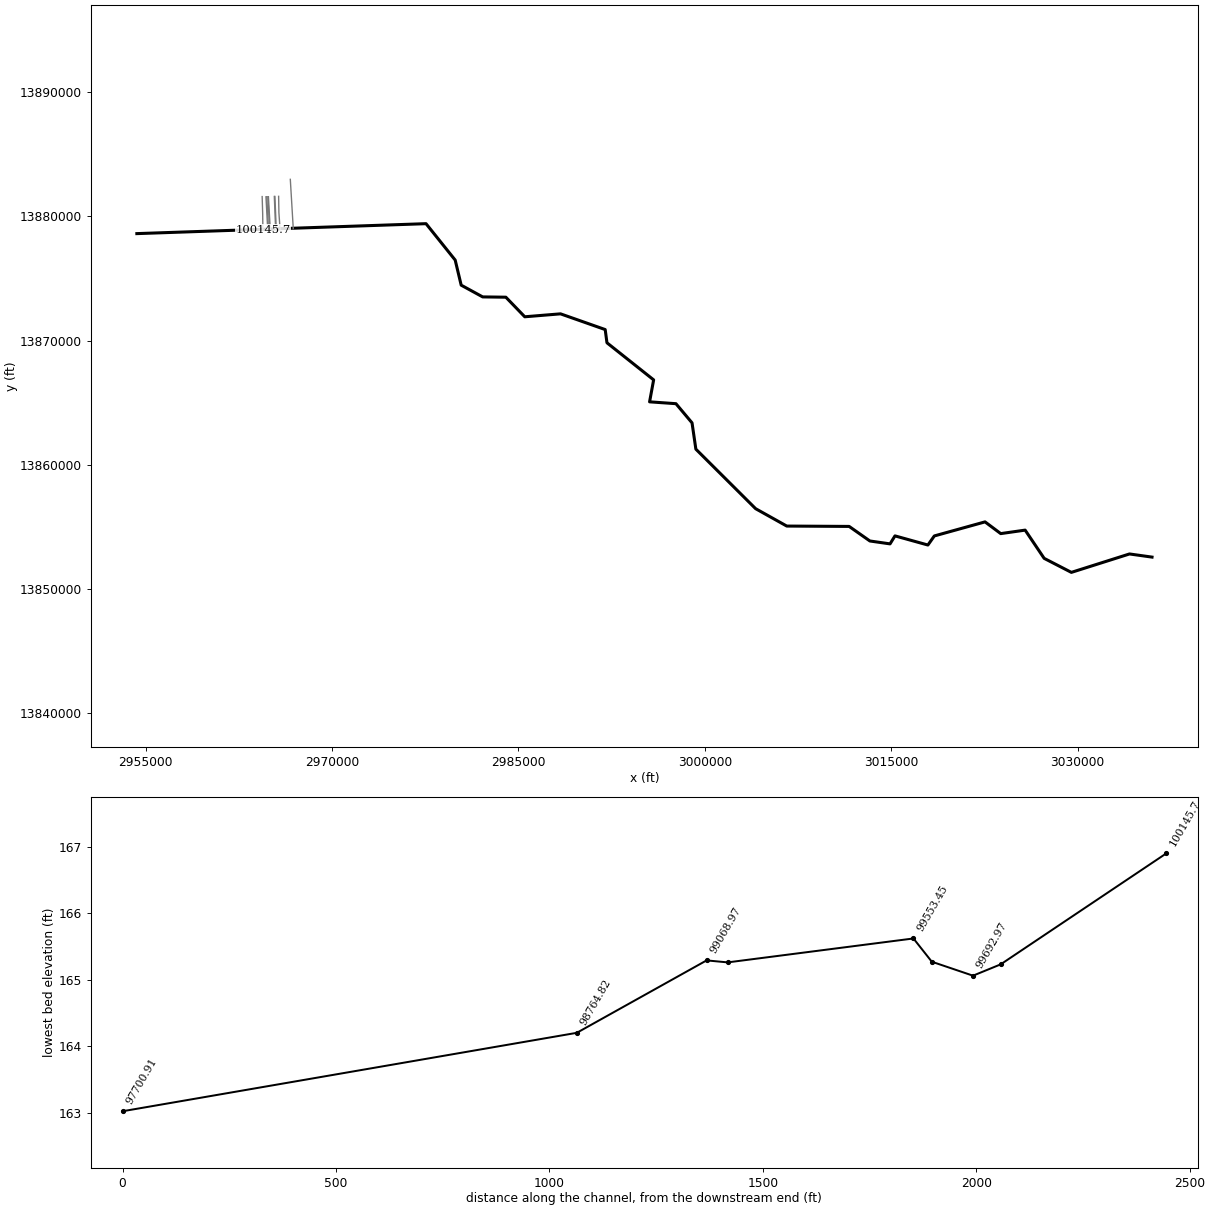
HEC-RAS study U101-00-00.prj: U101-00-00 2019 (Re-Study)

--- U101-00-00.f01 (steady flow) ---

Flow Title=Effective Multi-Profile 2019
Program Version=4.10
Number of Profiles= 4
Profile Names=10YR,50YR,100YR,500YR
River Rch & RM=U101-00-00,U101-00-00_0193 ,100145.7
     339     557     677    1030
River Rch & RM=U101-00-00,U101-00-00_0193 ,99596.47
     349     575     698    1064
River Rch & RM=U101-00-00,U101-00-00_0193 ,99118.3
     357     588     714    1089
River Rch & RM=U101-00-00,U101-00-00_0193 ,98764.82
     383     630     764    1170
River Rch & RM=U101-00-00,U101-00-00_0193 ,97700.91
     396     651     791    1212
River Rch & RM=U101-00-00,U101-00-00_0193 ,97174.13
     413     679     824    1265
River Rch & RM=U101-00-00,U101-00-00_0193 ,96527.58
     432     710     862    1326
River Rch & RM=U101-00-00,U101-00-00_0193 ,95830.44
     438     721     875    1347
River Rch & RM=U101-00-00,U101-00-00_0193 ,95594.33
     455     749     909    1401
River Rch & RM=U101-00-00,U101-00-00_0193 ,95003.93
     479     788     957    1478
River Rch & RM=U101-00-00,U101-00-00_0193 ,94207.76
     508     836    1016    1572
River Rch & RM=U101-00-00,U101-00-00_0193 ,93287.06
     540     888    1079    1674
River Rch & RM=U101-00-00,U101-00-00_0193 ,92350.25
     555     912    1108    1720
River Rch & RM=U101-00-00,U101-00-00_0193 ,91938.92
     573     943    1145    1782
River Rch & RM=U101-00-00,U101-00-00_0193 ,91417.91
     603     992    1204    1877
River Rch & RM=U101-00-00,U101-00-00_0193 ,90641.11
     635    1044    1268    1980
River Rch & RM=U101-00-00,U101-00-00_0193 ,89839.63
     653    1074    1304    2040
River Rch & RM=U101-00-00,U101-00-00_0193 ,89398.27
     682    1122    1362    2134
River Rch & RM=U101-00-00,U101-00-00_0193 ,88725.2
     734    1207    1466    2303
River Rch & RM=U101-00-00,U101-00-00_0193 ,87583.91
     764    1256    1525    2400
River Rch & RM=U101-00-00,U101-00-00_0193 ,86968.8
     780    1282    1557    2452
River Rch & RM=U101-00-00,U101-00-00_0193 ,86647.11
     826    1359    1650    2605
River Rch & RM=U101-00-00,U101-00-00_0193 ,85743.88
     881    1450    1761    2786
River Rch & RM=U101-00-00,U101-00-00_0193 ,84739.7
     948    1559    1893    3004
River Rch & RM=U101-00-00,U101-00-00_0193 ,83615.02
     986    1622    1969    3131
River Rch & RM=U101-00-00,U101-00-00_0193 ,82999.61
    1051    1729    2100    3347
River Rch & RM=U101-00-00,U101-00-00_0193 ,82000.36
    1108    1822    2213    3534
River Rch & RM=U101-00-00,U101-00-00_0193 ,81188.76
    1227    2015    2445    3843
River Rch & RM=U101-00-00,U101-00-00_0193 ,81071.45
    1555    2543    3077    4662
River Rch & RM=U101-00-00,U101-00-00_0193 ,80800.84
    1608    2634    3193    4903
River Rch & RM=U101-00-00,U101-00-00_0193 ,78183.56
    1671    2744    3332    5196
River Rch & RM=U101-00-00,U101-00-00_0193 ,75178.59
    1730    2847    3464    5478
River Rch & RM=U101-00-00,U101-00-00_0193 ,72447.08
    1771    2919    3556    5677
River Rch & RM=U101-00-00,U101-00-00_0193 ,70595.77
    1846    3049    3722    6041
River Rch & RM=U101-00-00,U101-00-00_0193 ,67376.78
    1898    3139    3839    6300
River Rch & RM=U101-00-00,U101-00-00_0193 ,65202.7
    1930    3197    3912    6464
River Rch & RM=U101-00-00,U101-00-00_0193 ,63870.36
    2034    3365    4111    6733
River Rch & RM=U101-00-00,U101-00-00_0193 ,62112.98
    2099    3470    4235    6899
River Rch & RM=U101-00-00,U101-00-00_0193 ,61062.95
    2193    3624    4417    7141
River Rch & RM=U101-00-00,U101-00-00_0193 ,59580.12
    2302    3801    4625    7415
River Rch & RM=U101-00-00,U101-00-00_0193 ,57954.2
    2397    3956    4807    7653
River Rch & RM=U101-00-00,U101-00-00_0193 ,56593.08
    2460    4059    4927    7810
River Rch & RM=U101-00-00,U101-00-00_0193 ,55716.98
    2551    4206    5100    8034
River Rch & RM=U101-00-00,U101-00-00_0193 ,54496.94
    2658    4379    5303    8295
River Rch & RM=U101-00-00,U101-00-00_0193 ,53121.04
    2839    4672    5645    8731
River Rch & RM=U101-00-00,U101-00-00_0193 ,50911.78
    3237    5211    6267    9693
River Rch & RM=U101-00-00,U101-00-00_0193 ,50735.53
    3371    5405    6453    9916
River Rch & RM=U101-00-00,U101-00-00_0193 ,47176.75
    3382    5421    6468    9934
River Rch & RM=U101-00-00,U101-00-00_0193 ,46896.98
    3472    5590    6669   10195
River Rch & RM=U101-00-00,U101-00-00_0193 ,46603.5
    3709    5923    7056   10650
River Rch & RM=U101-00-00,U101-00-00_0193 ,43550
    3945    6252    7439   11096
River Rch & RM=U101-00-00,U101-00-00_0193 ,40683.68
    4219    6630    7877   11600
River Rch & RM=U101-00-00,U101-00-00_0193 ,37581.29
    4483    6992    8296   12076
River Rch & RM=U101-00-00,U101-00-00_0193 ,34769.88
    5017    7814    9153   13120
River Rch & RM=U101-00-00,U101-00-00_0193 ,34393.11
    4938    7848    9241   13382
River Rch & RM=U101-00-00,U101-00-00_0193 ,31447.05
    4898    7867    9287   13522
River Rch & RM=U101-00-00,U101-00-00_0193 ,29898.14
    4815    7905    9383   13816
River Rch & RM=U101-00-00,U101-00-00_0193 ,26701.34
    4762    7930    9445   14008
River Rch & RM=U101-00-00,U101-00-00_0193 ,24646.42
    4628    7994    9609   14520
Boundary for River Rch & Prof#=U101-00-00,U101-00-00_0193 , 1
Up Type= 0
Dn Type= 1
Dn Known WS=97.6
Boundary for River Rch & Prof#=U101-00-00,U101-00-00_0193 , 2
Up Type= 0
Dn Type= 1
Dn Known WS=99.9
Boundary for River Rch & Prof#=U101-00-00,U101-00-00_0193 , 3
Up Type= 0
Dn Type= 1
Dn Known WS=100.8
Boundary for River Rch & Prof#=U101-00-00,U101-00-00_0193 , 4
Up Type= 0
Dn Type= 1
Dn Known WS=102.4
Observed WS=U101-00-00      ,U101-00-00_0193 ,100145.7,0,169.5,169.99,170.15,171.21
Observed WS=U101-00-00      ,U101-00-00_0193 ,99757.7 ,0,169.3,169.83,170.01,171.1
Observed WS=U101-00-00      ,U101-00-00_0193 ,99692.97,0,169.27,169.8,169.99,171.08
Observed WS=U101-00-00      ,U101-00-00_0193 ,99596.47,0,169.19,169.74,169.93,171.01
Observed WS=U101-00-00      ,U101-00-00_0193 ,99553.45,0,169.15,169.71,169.9,170.98
Observed WS=U101-00-00      ,U101-00-00_0193 ,99118.3 ,0,168.79,169.42,169.62,170.67
Observed WS=U101-00-00      ,U101-00-00_0193 ,99068.97,0,168.65,169.25,169.45,170.48
Observed WS=U101-00-00      ,U101-00-00_0193 ,98764.82,0,167.8,168.22,168.42,169.34
Observed WS=U101-00-00      ,U101-00-00_0193 ,97700.91,0,166.51,166.84,166.94,167.51
Observed WS=U101-00-00      ,U101-00-00_0193 ,97686.69,0,166.49,166.81,166.91,167.46
Observed WS=U101-00-00      ,U101-00-00_0193 ,97642.79,0,166.48,166.78,166.9,167.46
Observed WS=U101-00-00      ,U101-00-00_0193 ,97503.91,0,166.47,166.76,166.88,167.42
Observed WS=U101-00-00      ,U101-00-00_0193 ,97192.83,0,166.44,166.72,166.83,167.34
Observed WS=U101-00-00      ,U101-00-00_0193 ,97174.13,0,166.44,166.72,166.83,167.33
Observed WS=U101-00-00      ,U101-00-00_0193 ,97085.78,0,166.42,166.7,166.81,167.31
Observed WS=U101-00-00      ,U101-00-00_0193 ,96591.66,0,166.35,166.59,166.69,167.15
Observed WS=U101-00-00      ,U101-00-00_0193 ,96527.58,0,166.34,166.58,166.68,167.13
Observed WS=U101-00-00      ,U101-00-00_0193 ,96475.77,0,166.31,166.55,166.65,167.1
Observed WS=U101-00-00      ,U101-00-00_0193 ,96297.05,0,166.19,166.45,166.55,167
Observed WS=U101-00-00      ,U101-00-00_0193 ,96254.03,0,166.16,166.43,166.53,166.97
Observed WS=U101-00-00      ,U101-00-00_0193 ,96040.27,0,166.02,166.31,166.41,166.85
Observed WS=U101-00-00      ,U101-00-00_0193 ,95995.92,0,166,166.29,166.39,166.82
Observed WS=U101-00-00      ,U101-00-00_0193 ,95871.22,0,165.96,166.22,166.32,166.75
Observed WS=U101-00-00      ,U101-00-00_0193 ,95830.44,0,165.95,166.2,166.29,166.72
Observed WS=U101-00-00      ,U101-00-00_0193 ,95752.84,0,165.92,166.16,166.25,166.68
Observed WS=U101-00-00      ,U101-00-00_0193 ,95657.73,0,165.89,166.11,166.2,166.62
Observed WS=U101-00-00      ,U101-00-00_0193 ,95644.5 ,0,165.86,166.08,166.17,166.58
Observed WS=U101-00-00      ,U101-00-00_0193 ,95594.33,0,165.86,166.08,166.17,166.58
Observed WS=U101-00-00      ,U101-00-00_0193 ,95524.92,0,165.85,166.06,166.15,166.56
Observed WS=U101-00-00      ,U101-00-00_0193 ,95322.02,0,165.73,165.94,166.02,166.42
Observed WS=U101-00-00      ,U101-00-00_0193 ,95282.95,0,165.71,165.92,166,166.39
Observed WS=U101-00-00      ,U101-00-00_0193 ,95173.02,0,165.65,165.85,165.93,166.32
Observed WS=U101-00-00      ,U101-00-00_0193 ,95119.43,0,165.59,165.8,165.88,166.27
Observed WS=U101-00-00      ,U101-00-00_0193 ,95097.17,0,165.56,165.77,165.86,166.25
Observed WS=U101-00-00      ,U101-00-00_0193 ,95061.74,0,165.52,165.74,165.82,166.22
Observed WS=U101-00-00      ,U101-00-00_0193 ,95003.93,0,165.46,165.68,165.77,166.17
Observed WS=U101-00-00      ,U101-00-00_0193 ,94207.76,0,164.55,164.86,165.01,165.48
Observed WS=U101-00-00      ,U101-00-00_0193 ,93287.06,0,163.65,163.89,163.96,164.21
Observed WS=U101-00-00      ,U101-00-00_0193 ,92350.25,0,161.34,161.69,161.83,162.33
Observed WS=U101-00-00      ,U101-00-00_0193 ,92305.42,0,161.46,161.77,161.86,162.33
Observed WS=U101-00-00      ,U101-00-00_0193 ,92256.93,0,161.41,161.72,161.82,162.29
Observed WS=U101-00-00      ,U101-00-00_0193 ,92245.8 ,0,161.4,161.71,161.81,162.28
Observed WS=U101-00-00      ,U101-00-00_0193 ,92205.4 ,0,161.36,161.67,161.78,162.25
Observed WS=U101-00-00      ,U101-00-00_0193 ,91938.92,0,161.11,161.42,161.56,162.04
Observed WS=U101-00-00      ,U101-00-00_0193 ,91578.98,0,160.9,161.2,161.33,161.81
Observed WS=U101-00-00      ,U101-00-00_0193 ,91508.91,0,160.86,161.16,161.29,161.76
Observed WS=U101-00-00      ,U101-00-00_0193 ,91417.91,0,160.81,161.1,161.23,161.7
Observed WS=U101-00-00      ,U101-00-00_0193 ,90641.11,0,160.37,160.65,160.78,161.23
Observed WS=U101-00-00      ,U101-00-00_0193 ,90590.89,0,160.33,160.61,160.74,161.18
Observed WS=U101-00-00      ,U101-00-00_0193 ,89839.63,0,159.71,159.99,160.09,160.42
Observed WS=U101-00-00      ,U101-00-00_0193 ,89791.85,0,159.67,159.95,160.05,160.37
Observed WS=U101-00-00      ,U101-00-00_0193 ,89744.73,0,159.57,159.8,159.89,160.24
Observed WS=U101-00-00      ,U101-00-00_0193 ,89694.23,0,159.47,159.63,159.71,160.11
Observed WS=U101-00-00      ,U101-00-00_0193 ,89543.23,0,159.17,159.45,159.57,159.96
Observed WS=U101-00-00      ,U101-00-00_0193 ,89492.98,0,159.12,159.39,159.51,159.9
Observed WS=U101-00-00      ,U101-00-00_0193 ,89441.95,0,159.06,159.33,159.45,159.84
Observed WS=U101-00-00      ,U101-00-00_0193 ,89398.27,0,159.02,159.28,159.4,159.79
Observed WS=U101-00-00      ,U101-00-00_0193 ,88725.2 ,0,158.27,158.52,158.64,159.01
Observed WS=U101-00-00      ,U101-00-00_0193 ,87583.91,0,157.45,157.73,157.84,158.18
Observed WS=U101-00-00      ,U101-00-00_0193 ,87239.7 ,0,157.38,157.64,157.75,158.08
Observed WS=U101-00-00      ,U101-00-00_0193 ,86968.8 ,0,157.3,157.55,157.66,158
Observed WS=U101-00-00      ,U101-00-00_0193 ,86895.63,0,157.23,157.49,157.6,157.94
Observed WS=U101-00-00      ,U101-00-00_0193 ,86647.11,0,157.12,157.37,157.48,157.81
Observed WS=U101-00-00      ,U101-00-00_0193 ,85743.88,0,156.68,156.99,157.12,157.48
Observed WS=U101-00-00      ,U101-00-00_0193 ,84739.7 ,0,156.17,156.49,156.63,157.03
Observed WS=U101-00-00      ,U101-00-00_0193 ,83615.02,0,155.42,155.85,156.03,156.47
Observed WS=U101-00-00      ,U101-00-00_0193 ,83574.32,0,155.43,155.85,156.03,156.47
Observed WS=U101-00-00      ,U101-00-00_0193 ,83514.11,0,155.39,155.81,155.99,156.43
Observed WS=U101-00-00      ,U101-00-00_0193 ,82999.61,0,155.05,155.56,155.76,156.2
Observed WS=U101-00-00      ,U101-00-00_0193 ,82000.36,0,154.2,154.8,155.07,155.42
Observed WS=U101-00-00      ,U101-00-00_0193 ,81188.76,0,153.52,154.29,154.72,154.84
Observed WS=U101-00-00      ,U101-00-00_0193 ,81071.45,0,153.21,154.25,154.7,154.79
Observed WS=U101-00-00      ,U101-00-00_0193 ,80941.05,0,153.01,153.44,153.62,154.07
Observed WS=U101-00-00      ,U101-00-00_0193 ,80800.84,0,152.94,153.33,153.51,153.95
Observed WS=U101-00-00      ,U101-00-00_0193 ,79906.94,0,152.47,152.83,153,153.43
Observed WS=U101-00-00      ,U101-00-00_0193 ,79155.22,0,151.8,152.19,152.37,152.85
Observed WS=U101-00-00      ,U101-00-00_0193 ,78183.56,0,150.92,151.4,151.6,152.04
Observed WS=U101-00-00      ,U101-00-00_0193 ,77207.09,0,149.74,150.16,150.34,150.77
Observed WS=U101-00-00      ,U101-00-00_0193 ,76083.47,0,148.88,149.31,149.5,149.99
Observed WS=U101-00-00      ,U101-00-00_0193 ,75178.59,0,147.87,148.45,148.68,149.25
Observed WS=U101-00-00      ,U101-00-00_0193 ,74013.76,0,147.29,147.71,147.9,148.42
Observed WS=U101-00-00      ,U101-00-00_0193 ,73983.55,0,147.29,147.7,147.9,148.41
Observed WS=U101-00-00      ,U101-00-00_0193 ,73928.7 ,0,147.28,147.7,147.9,148.41
Observed WS=U101-00-00      ,U101-00-00_0193 ,73904.55,0,147.19,147.62,147.83,148.36
Observed WS=U101-00-00      ,U101-00-00_0193 ,72447.08,0,146.03,146.68,146.88,147.37
Observed WS=U101-00-00      ,U101-00-00_0193 ,71547.45,0,145.46,146.07,146.29,146.78
Observed WS=U101-00-00      ,U101-00-00_0193 ,70595.77,0,144.65,145.2,145.42,145.95
Observed WS=U101-00-00      ,U101-00-00_0193 ,69231.29,0,143.91,144.44,144.67,145.19
Observed WS=U101-00-00      ,U101-00-00_0193 ,68228.34,0,143.06,143.69,143.93,144.46
Observed WS=U101-00-00      ,U101-00-00_0193 ,67376.78,0,142.58,143.09,143.3,143.8
Observed WS=U101-00-00      ,U101-00-00_0193 ,67342.94,0,142.57,143.07,143.29,143.78
Observed WS=U101-00-00      ,U101-00-00_0193 ,67186.98,0,142.36,142.95,143.18,143.69
Observed WS=U101-00-00      ,U101-00-00_0193 ,66963   ,0,142.09,142.71,142.95,143.46
Observed WS=U101-00-00      ,U101-00-00_0193 ,65976.19,0,141.09,141.83,142.14,142.82
Observed WS=U101-00-00      ,U101-00-00_0193 ,65202.7 ,0,140.55,141.24,141.54,142.27
Observed WS=U101-00-00      ,U101-00-00_0193 ,64431.81,0,139.63,140.41,140.74,141.5
Observed WS=U101-00-00      ,U101-00-00_0193 ,64170.88,0,139.56,140.32,140.65,141.42
Observed WS=U101-00-00      ,U101-00-00_0193 ,64099.09,0,139.54,140.3,140.62,141.4
Observed WS=U101-00-00      ,U101-00-00_0193 ,64044.47,0,139.44,140.23,140.56,141.33
Observed WS=U101-00-00      ,U101-00-00_0193 ,63870.36,0,139.35,140.15,140.47,141.21
Observed WS=U101-00-00      ,U101-00-00_0193 ,63281.11,0,138.74,139.62,139.94,140.7
Observed WS=U101-00-00      ,U101-00-00_0193 ,62473.67,0,138.44,139.32,139.64,140.39
Observed WS=U101-00-00      ,U101-00-00_0193 ,62112.98,0,138.31,139.19,139.5,140.25
Observed WS=U101-00-00      ,U101-00-00_0193 ,61300.01,0,138.09,138.99,139.29,140.05
Observed WS=U101-00-00      ,U101-00-00_0193 ,61062.95,0,138.03,138.93,139.23,139.99
Observed WS=U101-00-00      ,U101-00-00_0193 ,60100.05,0,137.47,138.5,138.8,139.58
Observed WS=U101-00-00      ,U101-00-00_0193 ,60076.41,0,137.48,138.48,138.77,139.46
Observed WS=U101-00-00      ,U101-00-00_0193 ,60012.43,0,137.47,138.47,138.77,139.48
Observed WS=U101-00-00      ,U101-00-00_0193 ,59985.94,0,137.32,138.41,138.73,139.48
Observed WS=U101-00-00      ,U101-00-00_0193 ,59580.12,0,136.42,137.85,138.28,139.07
Observed WS=U101-00-00      ,U101-00-00_0193 ,58910.02,0,135.3,136.86,137.29,138.25
Observed WS=U101-00-00      ,U101-00-00_0193 ,58579.48,0,134.75,136.37,136.8,137.84
Observed WS=U101-00-00      ,U101-00-00_0193 ,57954.2 ,0,133.48,135.73,136.31,137.4
Observed WS=U101-00-00      ,U101-00-00_0193 ,57379.89,0,132.54,134.93,135.74,137.02
Observed WS=U101-00-00      ,U101-00-00_0193 ,56593.08,0,131.25,133.83,134.96,136.49
Observed WS=U101-00-00      ,U101-00-00_0193 ,55716.98,0,129.84,132.74,133.92,135.57
Observed WS=U101-00-00      ,U101-00-00_0193 ,54496.94,0,127.82,130.76,131.88,133.98
Observed WS=U101-00-00      ,U101-00-00_0193 ,53801.16,0,127.04,129.82,131.08,133.48
Observed WS=U101-00-00      ,U101-00-00_0193 ,53721.16,0,126.96,129.71,130.99,133.42
Observed WS=U101-00-00      ,U101-00-00_0193 ,53611.05,0,126.83,129.56,130.86,133.34
Observed WS=U101-00-00      ,U101-00-00_0193 ,53572.32,0,126.79,129.51,130.82,133.31
Observed WS=U101-00-00      ,U101-00-00_0193 ,53530.98,0,126.34,128.83,129.91,133.12
Observed WS=U101-00-00      ,U101-00-00_0193 ,53423.02,0,125.91,128.22,129.21,131.54
Observed WS=U101-00-00      ,U101-00-00_0193 ,53419.87,0,125.92,128.27,129.29,131.61
Observed WS=U101-00-00      ,U101-00-00_0193 ,53409.96,0,125.96,128.44,129.54,131.84
Observed WS=U101-00-00      ,U101-00-00_0193 ,53339.23,0,125.87,128.36,129.45,131.74
Observed WS=U101-00-00      ,U101-00-00_0193 ,53226.12,0,125.73,128.23,129.32,131.57
Observed WS=U101-00-00      ,U101-00-00_0193 ,53121.04,0,125.6,128.11,129.19,131.42
Observed WS=U101-00-00      ,U101-00-00_0193 ,52062.53,0,124.54,127.22,128.3,130.38
Observed WS=U101-00-00      ,U101-00-00_0193 ,51513.27,0,124.1,126.82,127.89,129.92
Observed WS=U101-00-00      ,U101-00-00_0193 ,50911.78,0,123.62,126.39,127.45,129.43
Observed WS=U101-00-00      ,U101-00-00_0193 ,50735.53,0,123.48,126.26,127.32,129.28
Observed WS=U101-00-00      ,U101-00-00_0193 ,50632.55,0,123.41,126.2,127.25,129.19
Observed WS=U101-00-00      ,U101-00-00_0193 ,49800.39,0,122.87,125.67,126.7,128.5
Observed WS=U101-00-00      ,U101-00-00_0193 ,49123.86,0,122.68,125.46,126.47,128.18
Observed WS=U101-00-00      ,U101-00-00_0193 ,48890.5 ,0,122.6,125.37,126.38,128.07
Observed WS=U101-00-00      ,U101-00-00_0193 ,48759.05,0,122.49,125.28,126.28,127.97
Observed WS=U101-00-00      ,U101-00-00_0193 ,48099.26,0,122.15,124.91,125.92,127.65
Observed WS=U101-00-00      ,U101-00-00_0193 ,47700.77,0,121.89,124.65,125.62,127.26
Observed WS=U101-00-00      ,U101-00-00_0193 ,47546.16,0,121.79,124.55,125.5,127.11
Observed WS=U101-00-00      ,U101-00-00_0193 ,47176.75,0,121.54,124.3,125.23,126.74
Observed WS=U101-00-00      ,U101-00-00_0193 ,46896.98,0,121.36,124.12,125.03,126.51
Observed WS=U101-00-00      ,U101-00-00_0193 ,46603.5 ,0,121.18,123.94,124.81,126.26
Observed WS=U101-00-00      ,U101-00-00_0193 ,46472.27,0,121.09,123.85,124.71,126.16
Observed WS=U101-00-00      ,U101-00-00_0193 ,46335.09,0,120.99,123.33,124.22,126.04
Observed WS=U101-00-00      ,U101-00-00_0193 ,45896.04,0,120.63,122.92,123.82,125.77
Observed WS=U101-00-00      ,U101-00-00_0193 ,45743.27,0,120.5,122.78,123.68,125.68
Observed WS=U101-00-00      ,U101-00-00_0193 ,45377.89,0,120.29,122.54,123.42,125.42
Observed WS=U101-00-00      ,U101-00-00_0193 ,44351.62,0,119.69,121.86,122.7,124.7
Observed WS=U101-00-00      ,U101-00-00_0193 ,43550   ,0,119.2,121.28,122.06,123.97
Observed WS=U101-00-00      ,U101-00-00_0193 ,42980.1 ,0,118.94,121.02,121.79,123.78
Observed WS=U101-00-00      ,U101-00-00_0193 ,42786.2 ,0,118.82,120.87,121.61,123.53
Observed WS=U101-00-00      ,U101-00-00_0193 ,42713.65,0,118.68,120.62,121.21,122.52
Observed WS=U101-00-00      ,U101-00-00_0193 ,42135.18,0,118.35,120.24,120.78,121.93
Observed WS=U101-00-00      ,U101-00-00_0193 ,41930.96,0,118.18,120.09,120.64,121.82
Observed WS=U101-00-00      ,U101-00-00_0193 ,40683.68,0,117.2,119.05,119.65,120.98
Observed WS=U101-00-00      ,U101-00-00_0193 ,40002.11,0,116.63,118.56,119.19,120.6
Observed WS=U101-00-00      ,U101-00-00_0193 ,39070.47,0,115.57,117.64,118.32,120.03
Observed WS=U101-00-00      ,U101-00-00_0193 ,38548.08,0,115.08,117.15,117.84,119.69
Observed WS=U101-00-00      ,U101-00-00_0193 ,38347.6 ,0,114.91,116.9,117.56,119.46
Observed WS=U101-00-00      ,U101-00-00_0193 ,38316.57,0,114.77,116.83,117.54,119.26
Observed WS=U101-00-00      ,U101-00-00_0193 ,37581.29,0,114.58,116.59,117.34,119.07
Observed WS=U101-00-00      ,U101-00-00_0193 ,37364.75,0,114.51,116.58,117.31,119.05
Observed WS=U101-00-00      ,U101-00-00_0193 ,37219.4 ,0,114.15,116.26,117.01,118.7
Observed WS=U101-00-00      ,U101-00-00_0193 ,36591.11,0,113.51,115.56,116.3,117.9
Observed WS=U101-00-00      ,U101-00-00_0193 ,35792.36,0,112.86,114.87,115.6,117.13
Observed WS=U101-00-00      ,U101-00-00_0193 ,34769.88,0,111.94,113.72,114.39,115.96
Observed WS=U101-00-00      ,U101-00-00_0193 ,34393.11,0,111.6,113.29,113.95,115.53
Observed WS=U101-00-00      ,U101-00-00_0193 ,33420.95,0,110.38,111.45,111.81,112.57
Observed WS=U101-00-00      ,U101-00-00_0193 ,32152.3 ,0,109.87,110.93,111.34,112.22
Observed WS=U101-00-00      ,U101-00-00_0193 ,31747.41,0,109.69,110.74,111.16,112.04
Observed WS=U101-00-00      ,U101-00-00_0193 ,31447.05,0,109.58,110.63,111.04,111.9
Observed WS=U101-00-00      ,U101-00-00_0193 ,31343.59,0,109.46,110.41,110.85,111.72
Observed WS=U101-00-00      ,U101-00-00_0193 ,31253.61,0,109.39,110.34,110.79,111.66
Observed WS=U101-00-00      ,U101-00-00_0193 ,31076.4 ,0,109.26,110.19,110.67,111.56
Observed WS=U101-00-00      ,U101-00-00_0193 ,30385.92,0,108.74,109.63,110.21,111.13
Observed WS=U101-00-00      ,U101-00-00_0193 ,29947.52,0,108.55,109.43,110.04,111
Observed WS=U101-00-00      ,U101-00-00_0193 ,29898.14,0,108.52,109.4,110.02,110.99
Observed WS=U101-00-00      ,U101-00-00_0193 ,29812.82,0,108.33,109.28,109.97,110.95
Observed WS=U101-00-00      ,U101-00-00_0193 ,29699.63,0,108.27,109.22,109.93,110.91
Observed WS=U101-00-00      ,U101-00-00_0193 ,29249.24,0,108.05,109.03,109.79,110.79
Observed WS=U101-00-00      ,U101-00-00_0193 ,28913.98,0,107.91,108.91,109.71,110.71
Observed WS=U101-00-00      ,U101-00-00_0193 ,27746.61,0,107.46,108.47,109.41,110.4
Observed WS=U101-00-00      ,U101-00-00_0193 ,26767.03,0,107.29,108.28,109.28,110.26
Observed WS=U101-00-00      ,U101-00-00_0193 ,26701.34,0,107.28,108.27,109.27,110.25
Observed WS=U101-00-00      ,U101-00-00_0193 ,26611.14,0,107.27,108.25,109.26,110.24
Observed WS=U101-00-00      ,U101-00-00_0193 ,26316.96,0,107.23,108.2,109.22,110.19
Observed WS=U101-00-00      ,U101-00-00_0193 ,25395.09,0,106.98,107.91,109.04,110.02
Observed WS=U101-00-00      ,U101-00-00_0193 ,24933.98,0,106.65,107.54,108.86,109.85
Observed WS=U101-00-00      ,U101-00-00_0193 ,24646.42,0,106.31,107.32,108.73,109.69
Observed WS=U101-00-00      ,U101-00-00_0193 ,24472.12,0,106.09,107.26,107.73,108.84
Observed WS=U101-00-00      ,U101-00-00_0193 ,24324.98,0,105.94,107.13,107.6,108.7
Observed WS=U101-00-00      ,U101-00-00_0193 ,23269.93,0,104.88,106.22,106.65,107.69
Observed WS=U101-00-00      ,U101-00-00_0193 ,22132.32,0,104.23,105.52,105.93,106.86
Observed WS=U101-00-00      ,U101-00-00_0193 ,21398.91,0,103.53,104.74,105.11,105.94
Observed WS=U101-00-00      ,U101-00-00_0193 ,20720.25,0,102.64,103.75,104.01,104.7
Observed WS=U101-00-00      ,U101-00-00_0193 ,19300.97,0,99.48,100.21,100.8,102.4
DSS Import GetInterval= 0
DSS Import GetPeak= 0
DSS Import FillOption= 0

--- U101-00-00.f03 (steady flow) ---

Flow Title=Storage Routing Flows
Program Version=4.10
Number of Profiles= 8
Profile Names=0.2,0.4,0.6,0.8,1,1.2,1.5,2
River Rch & RM=U101-00-00,U101-00-00_0193 ,100145.7
     443     885    1328    1770    2213    2656    3320    4426
River Rch & RM=U101-00-00,U101-00-00_0193 ,81188.76
     779    1558    2337    3116    3895    4674    5843    7790
River Rch & RM=U101-00-00,U101-00-00_0193 ,63870.36
    1133    2265    3398    4530    5663    6796    8495   11326
River Rch & RM=U101-00-00,U101-00-00_0193 ,50911.78
    1301    2602    3904    5205    6506    7807    9759   13012
River Rch & RM=U101-00-00,U101-00-00_0193 ,46896.98
    1660    3320    4979    6639    8299    9959   12449   16598
River Rch & RM=U101-00-00,U101-00-00_0193 ,34769.88
    1924    3848    5773    7697    9621   11545   14432   19242
Boundary for River Rch & Prof#=U101-00-00,U101-00-00_0193 , 1
Up Type= 0
Dn Type= 3
Dn Slope=0.00163
Boundary for River Rch & Prof#=U101-00-00,U101-00-00_0193 , 2
Up Type= 0
Dn Type= 3
Dn Slope=0.00163
Boundary for River Rch & Prof#=U101-00-00,U101-00-00_0193 , 3
Up Type= 0
Dn Type= 3
Dn Slope=0.00163
Boundary for River Rch & Prof#=U101-00-00,U101-00-00_0193 , 4
Up Type= 0
Dn Type= 3
Dn Slope=0.00163
Boundary for River Rch & Prof#=U101-00-00,U101-00-00_0193 , 5
Up Type= 0
Dn Type= 3
Dn Slope=0.00163
Boundary for River Rch & Prof#=U101-00-00,U101-00-00_0193 , 6
Up Type= 0
Dn Type= 3
Dn Slope=0.00163
Boundary for River Rch & Prof#=U101-00-00,U101-00-00_0193 , 7
Up Type= 0
Dn Type= 3
Dn Slope=0.00163
Boundary for River Rch & Prof#=U101-00-00,U101-00-00_0193 , 8
Up Type= 0
Dn Type= 3
Dn Slope=0.00163
DSS Import GetInterval= 0
DSS Import GetPeak= 0
DSS Import FillOption= 0

--- U101-00-00.g01 (geometry) ---

Geom Title=U101-00-00 2019 (ReStudy)
Program Version=4.10

River Reach=U101-00-00      ,U101-00-00_0193
Reach XY= 30
2954291.3153516913878615.41419872977563.4144766913879415.3295936
2979910.1108987813876485.84923212980392.2890682813874467.4795812
2982122.1405954513873522.13107822983987.6788591113873498.0796171
2985508.9871681913871922.49877882988387.1123174413872159.1944996
2991981.8994191913870893.70884162992123.6780070213869830.0124782
2995880.3578296213866844.90919642995553.9250835313865077.8641741
2997675.7394094513864929.00456372998970.1367550313863386.7599448
2999278.5629754413861270.31043753004086.8056555213856480.0001363
3006593.4883061913855080.56986433011613.8437510313855051.7930189
3013282.8456623613853879.80783013014905.0100689413853646.7899234
3015302.2300750313854290.36507993017952.47903961 13853554.642798
3018468.8851590313854285.89297593022549.6489791113855416.9838896
3023812.8643004413854473.35027823025778.0549238613854753.9028667
3027307.3609203513852482.30471963029497.1482074413851353.2525158
3034173.9213341913852835.56221523035988.0627190313852582.4367372

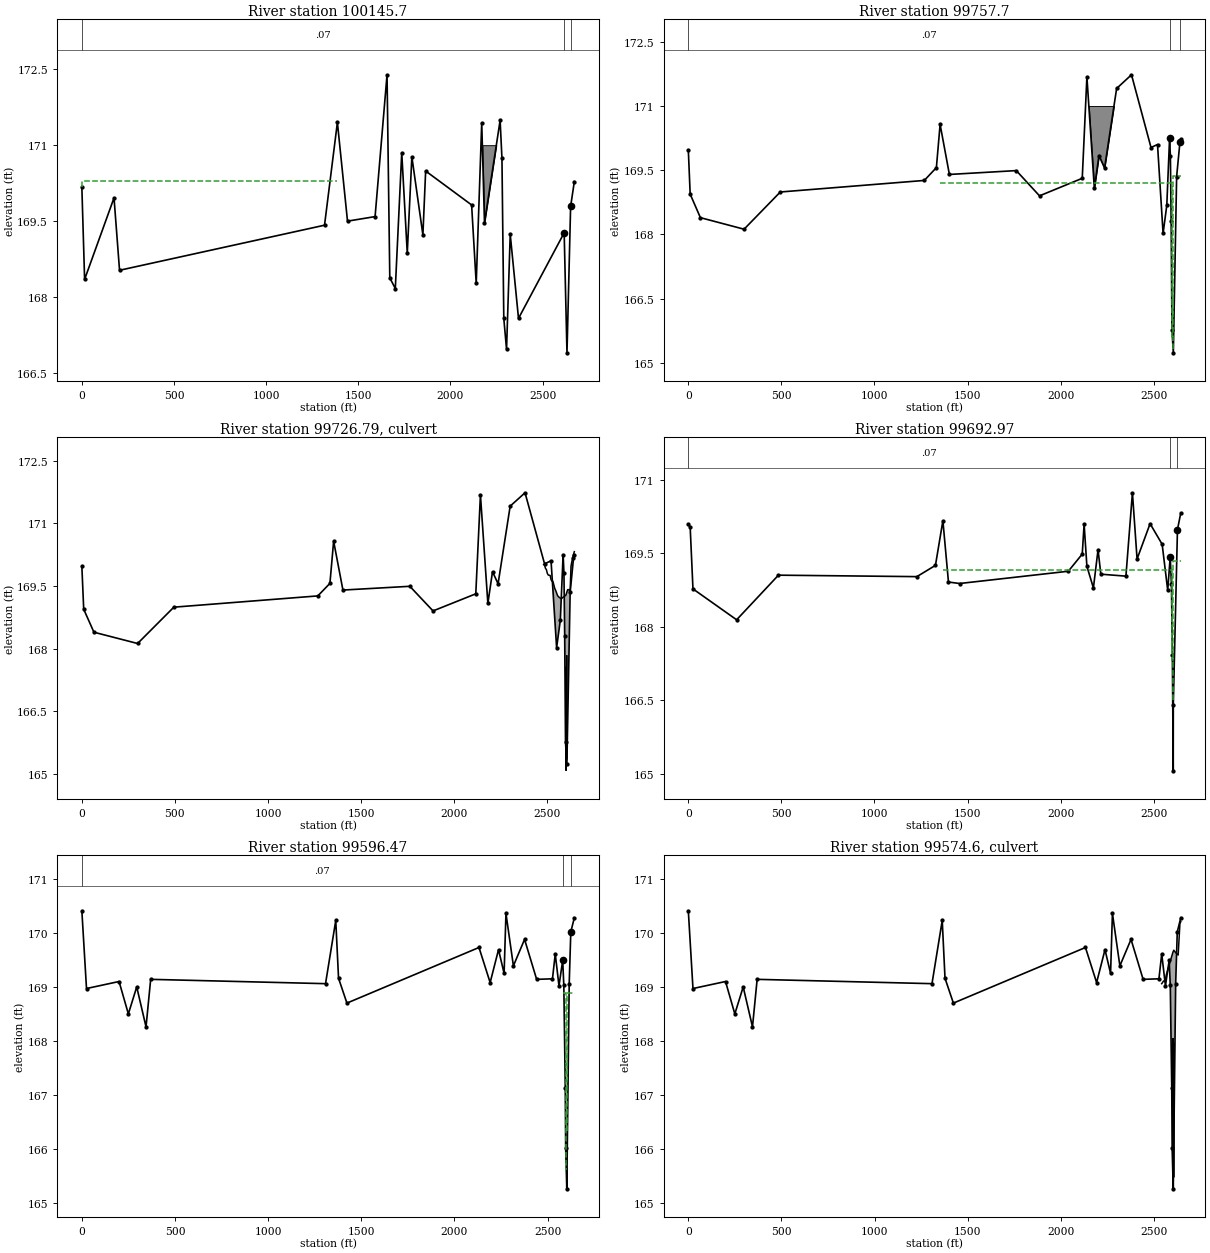
Type RM Length L Ch R = 1 ,100145.7,387.86,387.99,388.64
BEGIN DESCRIPTION:
LIMIT OF DETAILED STUDY
END DESCRIPTION:
Node Name=BI
XS GIS Cut Line= 5
2964376.2797617813881596.85574242964417.8400461113880190.9599321
2964433.2199366113879023.81003542964432.7199376113878927.6501228
 2964432.708454713878925.4201404
#Sta/Elev= 30
       0  170.17   14.96  168.35  174.57  169.96  204.49  168.53 1316.73  169.42
 1386.56  171.45 1441.43   169.5 1591.07  169.59 1655.92  172.39 1670.89  168.38
 1700.82  168.17 1735.73  170.85 1765.66  168.87  1790.6  170.77 1850.46  169.23
 1865.43  170.49 2114.84  169.82 2139.78  168.27 2169.71  171.44 2184.68  169.47
 2269.48  171.49 2279.45  170.74 2289.43  167.58 2304.39  166.97 2324.35  169.24
 2369.24  167.58 2617.03  169.27 2632.28   166.9 2652.02  169.79 2672.15  170.28
#Mann= 3 ,-1 , 0
       0     .07       0 2617.03     .04       0 2652.02     .05       0
#XS Ineff= 2 ,-1
       0 1386.56   170.3 1386.56 2617.03   169.2
Permanent Ineff=
       F       F
#Block Obstruct= 1 ,-1
 2169.71 2269.48     171
Bank Sta=2617.03,2652.02
XS Rating Curve= 0 ,0
Exp/Cntr=0.5,0.3

Type RM Length L Ch R = 1 ,99757.7 ,64.69,64.73,64.58
BEGIN DESCRIPTION:
Upstream Section - DRIVEWAY #12
END DESCRIPTION:
XS GIS Cut Line= 3
2964682.0898456913881578.8800565 2964820.583663213878977.2615721
2964820.7919961113878937.0333061
#Sta/Elev= 30
       0  169.97    9.98  168.94   64.88  168.39  299.46  168.12  494.11  168.99
 1267.71  169.26  1332.6  169.56 1352.56  170.57 1402.47   169.4 1761.82  169.49
  1886.6   168.9 2116.18  169.31 2141.14  171.68 2181.07  169.08 2206.02  169.84
 2235.97  169.55 2300.85  171.41 2380.71  171.73 2485.52  170.03 2520.45   170.1
  2550.4  168.02 2570.36  168.68 2585.34  170.25 2589.69  169.82 2593.79  168.31
 2598.14  165.76 2605.48  165.23 2623.18  169.35 2641.06  170.16 2645.53  170.23
#Mann= 3 ,-1 , 0
       0     .07       0 2585.34     .04       0 2641.06     .05       0
#XS Ineff= 3 ,-1
       0 1352.56  169.85 1352.56 2600.52  169.19 2605.83 2645.53  169.36
Permanent Ineff=
       F       F       F
#Block Obstruct= 1 ,-1
 2141.14 2300.85     171
Bank Sta=2585.34,2641.06
XS Rating Curve= 0 ,0
Exp/Cntr=0.5,0.3

Type RM Length L Ch R = 2 ,99726.79,,,
BEGIN DESCRIPTION:
DRIVEWAY #12
END DESCRIPTION:
Node Name=DRIVEWAY #12
Bridge Culvert--1,0,-1,-1, 0
Deck Dist Width WeirC Skew NumUp NumDn MinLoCord MaxHiCord MaxSubmerge Is_Ogee
26,15,2.6,0, 29, 29, , , 0.98, 0, 2,2,,
 2480.53 2485.52 2490.51  2495.5 2500.49 2505.48 2515.46 2520.45 2525.44 2530.44
 2540.42 2545.41 2555.39 2560.38 2575.35 2580.35 2585.34 2590.33 2595.32 2600.31
  2605.3 2609.77 2614.24 2618.71 2623.18 2627.65 2632.12 2641.06 2645.53
  170.01     170  169.92  169.89   169.8  169.76  169.75  169.65  169.61  169.61
  169.44  169.39  169.27  169.24  169.19  169.21  169.23  169.24  169.26  169.28
  169.35  169.41  169.41   169.4  169.39  169.97  170.08  170.25  170.32
       0       0       0       0       0       0       0       0       0       0
       0       0       0       0       0       0       0       0       0       0
       0       0       0       0       0       0       0       0       0
 2480.53 2485.52 2490.51  2495.5 2500.49 2505.48 2515.46 2520.45 2525.44 2530.44
 2540.42 2545.41 2555.39 2560.38 2575.35 2580.35 2585.34 2590.33 2595.32 2600.31
  2605.3 2609.77 2614.24 2618.71 2623.18 2627.65 2632.12 2641.06 2645.53
  170.01     170  169.92  169.89   169.8  169.76  169.75  169.65  169.61  169.61
  169.44  169.39  169.27  169.24  169.19  169.21  169.23  169.24  169.26  169.28
  169.35  169.41  169.41   169.4  169.39  169.97  170.08  170.25  170.32
       0       0       0       0       0       0       0       0       0       0
       0       0       0       0       0       0       0       0       0       0
       0       0       0       0       0       0       0       0       0
BR Coef=-1 , 0 , 0 ,, 0 ,,,0.8,0,,0,
WSPro=,,,, 1 ,,,, 0 ,,,, 0 ,,,,-1 ,-1 ,-1 , 0 , 0 , 0 , 0 , 0
Culvert=1,2.5,,33,0.013,0.5,1,1,3,165.07,2601.78,165.29,2601.78,Culvert #1  , 0 ,18.5
Culvert Bottom n=0.013
Culvert=1,2.5,,33,0.013,0.5,1,1,3,165.34,2604.58,165.45,2604.58,Culvert #2  , 0 ,18.5
Culvert Bottom n=0.013
BC Design=,, 0 ,, 0 ,,,,,,
BC Use User HTab Curves=0
BC User HTab FreeFlow(D)= 0

Type RM Length L Ch R = 1 ,99692.97,96.42,96.5,97.48
BEGIN DESCRIPTION:
Downstream Section - DRIVEWAY #12
END DESCRIPTION:
XS GIS Cut Line= 3
2964746.5939817713881584.11757882964885.0877992813878982.4990944
2964885.2961321913878942.2708284
#Sta/Elev= 30
       0  170.09    9.98  170.03   24.95  168.77  259.53  168.14  484.13  169.05
 1227.79  169.02 1327.61  169.25 1367.53  170.16 1397.48  168.91 1457.37  168.88
 2041.32  169.13 2116.18  169.48 2126.17  170.09 2141.14  169.23 2176.08  168.79
 2201.03  169.57    2216  169.07 2350.76  169.03  2385.7  170.73 2410.65  169.38
 2480.53   170.1 2545.41  169.68 2575.35  168.74 2588.77  169.43 2595.32  168.86
 2600.31  167.42 2604.95  165.06  2605.3  166.41 2627.65  169.98 2645.53  170.32
#Mann= 3 ,-1 , 0
       0     .07       0 2588.77     .04       0 2627.65     .05       0
#XS Ineff= 3 ,-1
       0 1367.53  169.55 1367.53 2600.53  169.16 2605.83 2645.53  169.33
Permanent Ineff=
       F       F       F
Bank Sta=2588.77,2627.65
XS Rating Curve= 0 ,0
Exp/Cntr=0.5,0.3

Type RM Length L Ch R = 1 ,99596.47,42.91,43.02,42.95
BEGIN DESCRIPTION:
Upstream Section - DRIVEWAY #11
END DESCRIPTION:
XS GIS Cut Line= 3
2964836.7752318513881584.85150132964981.4462023713878987.7740183
2964983.5587309513878945.3626858
#Sta/Elev= 30
       0  170.42   24.96  168.98   199.7  169.11  249.63  168.51  294.56  169.01
  344.48  168.27  369.45  169.15 1308.04  169.07 1362.96  170.24 1377.94  169.17
 1422.87  168.71 2131.81  169.74 2191.72  169.09 2236.66   169.7 2266.61  169.26
  2276.6  170.37 2316.54   169.4 2376.45  169.89 2441.35  169.15 2526.23  169.16
  2541.2  169.62 2561.17  169.03 2581.14   169.5 2587.15  169.04 2595.02  167.13
 2597.15  166.02 2603.17  165.27 2616.07  169.07  2624.7  170.03 2643.58  170.29
#Mann= 3 ,-1 , 0
       0     .07       0 2581.14     .04       0  2624.7     .05       0
#XS Ineff= 4 ,-1
       0 1362.96  169.35 1362.96 2581.14   169.1 2581.14 2600.42   168.9
 2606.82 2643.58   168.9
Permanent Ineff=
       F       F       F       F
Bank Sta=2581.14,2624.7
XS Rating Curve= 0 ,0
Exp/Cntr=0.5,0.3

Type RM Length L Ch R = 2 ,99574.6 ,,,
BEGIN DESCRIPTION:
DRIVEWAY #11
END DESCRIPTION:
Node Name=DRIVEWAY #11
Bridge Culvert--1,0,-1,-1, 0
Deck Dist Width WeirC Skew NumUp NumDn MinLoCord MaxHiCord MaxSubmerge Is_Ogee
13.5,18,2.6,0, 11, 11, , , 0.98, 0, 0,0,,
  2541.2 2551.19 2556.18 2561.17 2566.17 2601.11 2605.83 2619.99 2629.42 2638.86
 2643.58
  169.07  169.12  169.12  169.15  169.24  169.65  169.69  169.63   169.6  170.18
  170.22
       0       0       0       0       0       0       0       0       0       0
       0
  2541.2 2551.19 2556.18 2561.17 2566.17 2601.11 2605.83 2619.99 2629.42 2638.86
 2643.58
  169.07  169.12  169.12  169.15  169.24  169.65  169.69  169.63   169.6  170.18
  170.22
       0       0       0       0       0       0       0       0       0       0
       0
BR Coef=-1 , 0 , 0 ,, 0 ,,,0.8,0,,0,
WSPro=,,,, 1 ,,,, 0 ,,,, 0 ,,,,-1 ,-1 ,-1 , 0 , 0 , 0 , 0 , 0
Culvert=1,2.5,,32.5,0.013,0.5,1,1,3,165.56,2601.67,165.44,2598.66,Culvert #1  , 0 ,6
Culvert Bottom n=0.013
Culvert=1,2.5,,32.5,0.013,0.5,1,1,3,165.48,2605.57,165.82,2602.56,Culvert #2  , 0 ,6
Culvert Bottom n=0.013
BC Design=,, 0 ,, 0 ,,,,,,
BC Use User HTab Curves=0
BC User HTab FreeFlow(D)= 0

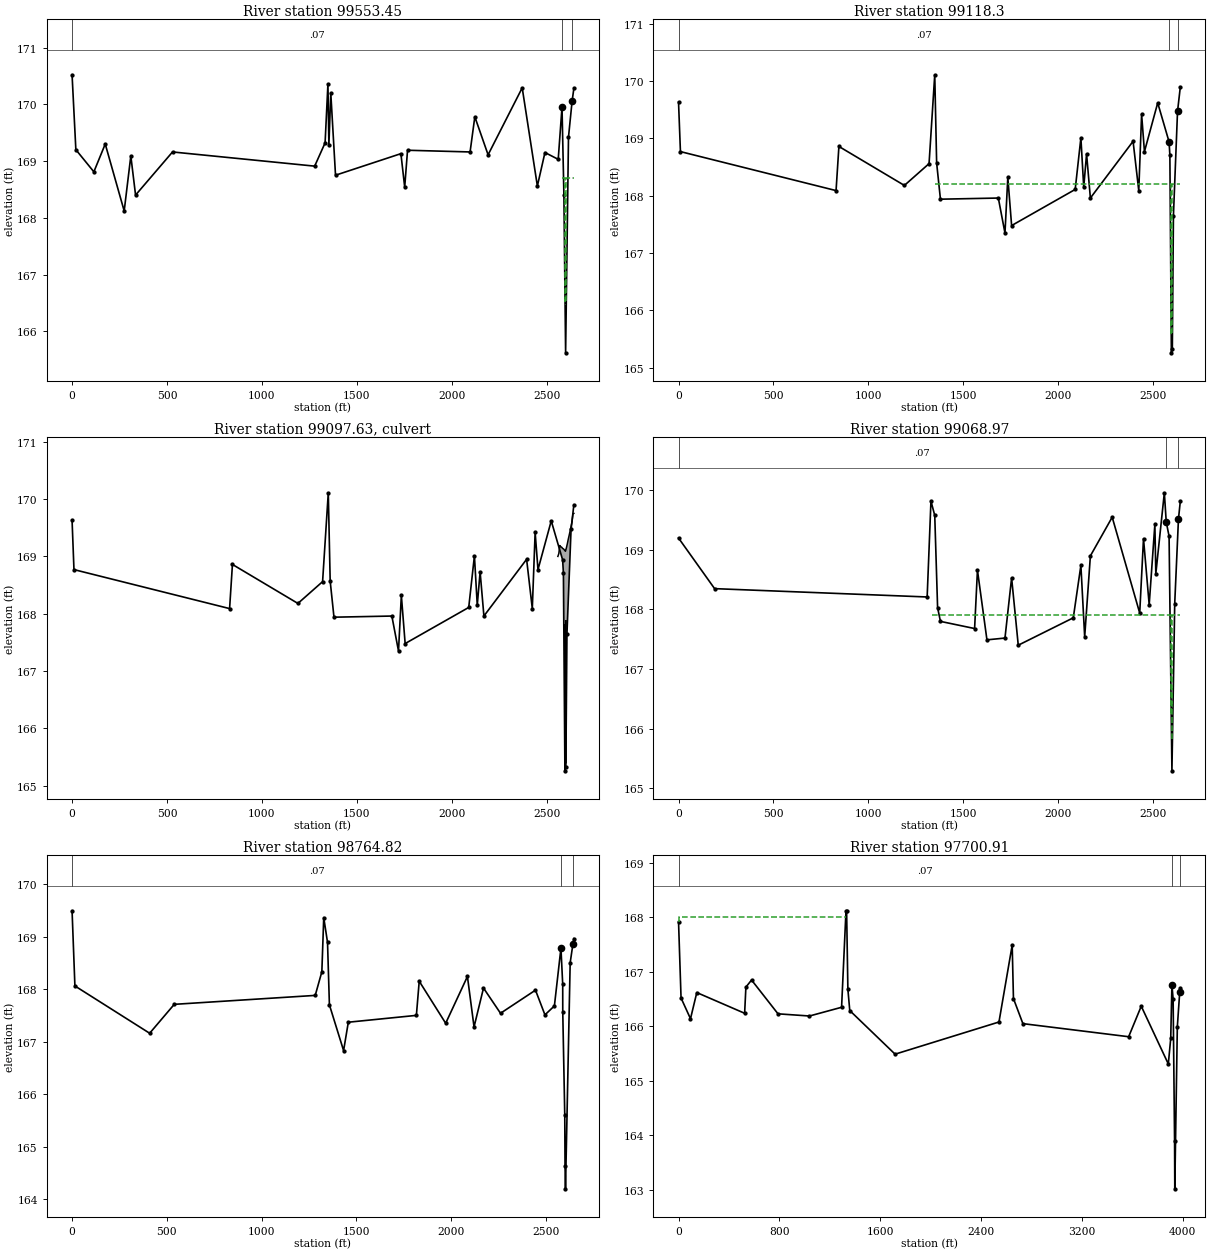
Type RM Length L Ch R = 1 ,99553.45,435.38,435.15,435.2
BEGIN DESCRIPTION:
Downstream Section - DRIVEWAY #11
END DESCRIPTION:
Node Name=BH
XS GIS Cut Line= 3
2964879.7738335313881584.42597722965024.4448040313878987.3484942
2965026.5573326113878944.9371617
#Sta/Elev= 30
       0  170.52   19.97   169.2  114.83  168.81  174.74   169.3  274.59  168.12
  309.54  169.09   334.5   168.4  529.21  169.16 1278.09  168.91 1333.01  169.32
 1347.98  170.36 1352.98  169.28 1362.96   170.2 1387.92  168.75 1732.41  169.13
 1752.38  168.54 1767.36  169.19 2096.87  169.16 2121.83  169.78 2191.72  169.11
 2371.46  170.29 2451.34  168.56 2491.28  169.15 2561.17  169.03 2581.14  169.95
 2591.13   168.4 2600.16  165.62 2615.27  169.42 2634.14  170.05 2643.58  170.28
#Mann= 3 ,-1 , 0
       0     .07       0 2581.14     .04       0 2634.14     .05       0
#XS Ineff= 4 ,-1
       0 1362.96   169.3 1362.96 2581.14     169 2581.14 2597.41   168.7
 2603.81 2643.58   168.7
Permanent Ineff=
       F       F       F       F
Bank Sta=2581.14,2634.14
XS Rating Curve= 0 ,0
Exp/Cntr=0.5,0.3

Type RM Length L Ch R = 1 ,99118.3 ,49.33,49.33,49.36
BEGIN DESCRIPTION:
Upstream Section - ACCESS RD #5
END DESCRIPTION:
XS GIS Cut Line= 4
2965353.7551690313881602.06668992965450.0837165313879199.6692638
2965459.1001026913879005.25232982965461.1509516113878961.0339143
#Sta/Elev= 30
       0  169.63      10  168.77  829.77  168.09  844.76  168.86 1189.67  168.18
 1319.63  168.56 1349.62  170.11 1359.62  168.57 1379.61  167.94 1684.53  167.96
 1719.52  167.35 1734.51  168.32 1754.51  167.48 2089.42  168.11 2119.41  169.01
  2134.4  168.15  2149.4  168.73  2169.4  167.96 2394.34  168.95 2424.29  168.09
 2439.26  169.42 2454.24  168.77  2524.1  169.62 2583.99  168.94 2588.15  168.71
 2596.09  165.26 2601.09  165.33 2606.85  167.65 2628.47  169.47 2643.22   169.9
#Mann= 3 ,-1 , 0
       0     .07       0 2583.99     .04       0 2628.47     .05       0
#XS Ineff= 3 ,-1
       0 1349.62   168.6 1349.62 2595.38   168.2 2601.78 2643.22   168.2
Permanent Ineff=
       F       F       F
Bank Sta=2583.99,2628.47
XS Rating Curve= 0 ,0
Exp/Cntr=0.5,0.3

Type RM Length L Ch R = 2 ,99097.63,,,
BEGIN DESCRIPTION:
ACCESS RD #5
END DESCRIPTION:
Node Name=ACCESS RD #5
Bridge Culvert--1,0,-1,-1, 0
Deck Dist Width WeirC Skew NumUp NumDn MinLoCord MaxHiCord MaxSubmerge Is_Ogee
16.5,15,2.6,0, 16, 16, , , 0.98, 0, 0,0,,
 2559.03 2564.02 2569.01    2574 2578.99 2583.99 2588.98 2593.97 2598.96 2603.87
 2608.79 2613.71 2618.63 2633.39  2638.3 2643.22
     169  169.05  169.19  169.17  169.16  169.14  169.13  169.11  169.09  169.15
  169.22   169.3  169.37   169.6  169.74  169.75
       0       0       0       0       0       0       0       0       0       0
       0       0       0       0       0       0
 2559.03 2564.02 2569.01    2574 2578.99 2583.99 2588.98 2593.97 2598.96 2603.87
 2608.79 2613.71 2618.63 2633.39  2638.3 2643.22
     169  169.05  169.19  169.17  169.16  169.14  169.13  169.11  169.09  169.15
  169.22   169.3  169.37   169.6  169.74  169.75
       0       0       0       0       0       0       0       0       0       0
       0       0       0       0       0       0
BR Coef=-1 , 0 , 0 ,, 0 ,,,0.8,0,,0,
WSPro=,,,, 1 ,,,, 0 ,,,, 0 ,,,,-1 ,-1 ,-1 , 0 , 0 , 0 , 0 , 0
Culvert=1,2.5,,15,0.013,0.5,1,1,3,165.32,2596.63,165.58,2596.63,Culvert #1  , 0 ,16.5
Culvert Bottom n=0.013
Culvert=1,2.5,,15,0.013,0.5,1,1,3,165.39,2600.53,165.43,2600.53,Culvert #2  , 0 ,16.5
Culvert Bottom n=0.013
BC Design=,, 0 ,, 0 ,,,,,,
BC Use User HTab Curves=0
BC User HTab FreeFlow(D)= 0

Type RM Length L Ch R = 1 ,99068.97,332.71,304.15,303.75
BEGIN DESCRIPTION:
Downstream Section - ACCESS RD #5
END DESCRIPTION:
XS GIS Cut Line= 4
2965403.04378437 13881604.0276442965499.3723318613879201.6302179
2965508.3887180213879007.21328392965510.4395669413878962.9948684
#Sta/Elev= 30
       0   169.2  189.95  168.35 1309.63  168.21 1329.63  169.82 1349.62  169.58
 1364.62  168.03 1379.61   167.8 1559.56  167.68 1574.56  168.66 1624.55  167.49
 1719.52  167.52 1754.51  168.53  1789.5   167.4 2079.42  167.86 2119.41  168.74
  2139.4  167.54  2169.4   168.9 2284.36  169.55 2429.28  167.94 2449.25  169.19
 2479.19  168.08 2509.13  169.43 2514.12   168.6 2559.03  169.96 2569.01  169.47
 2583.99  169.23 2598.96  165.29 2613.71   168.1 2633.39  169.52 2643.22  169.82
#Mann= 3 ,-1 , 0
       0     .07       0 2569.01     .04       0 2633.39     .05       0
#XS Ineff= 3 ,-1
       0 1334.63   168.8 1334.63 2595.38   167.9 2601.78 2643.22   167.9
Permanent Ineff=
       F       F       F
Bank Sta=2569.01,2633.39
XS Rating Curve= 0 ,0
Exp/Cntr=0.5,0.3

Type RM Length L Ch R = 1 ,98764.82,1360.92,1063.91,1063.42
Node Name=BG
XS GIS Cut Line= 4
2965700.9726504413881616.73135882965723.66781503 13880289.392478
2965811.3999230313879055.84999762965813.3487380313878973.1598743
#Sta/Elev= 30
       0  169.49   14.97  168.06  409.24  167.16     539  167.71 1282.62  167.88
 1317.55  168.33 1327.53  169.36 1347.48  168.89 1357.45   167.7 1432.25  166.83
 1457.18  167.37 1816.21   167.5 1831.17  168.15 1970.79  167.35 2085.48  168.24
 2120.39  167.28 2170.25  168.02 2260.01  167.54 2444.51  167.98 2494.38  167.51
 2544.24  167.68 2578.78  168.78 2588.09  168.09 2588.33  167.57 2598.93   165.6
 2600.35  164.63 2602.78   164.2 2627.44   168.5 2642.03  168.86  2646.9  168.96
#Mann= 3 ,-1 , 0
       0     .07       0 2578.78     .04       0 2642.03     .05       0
#XS Ineff= 2 ,-1
       0 1332.52   168.1 1332.52 2339.79   167.5
Permanent Ineff=
       F       F
Bank Sta=2578.78,2642.03
XS Rating Curve= 0 ,0
Exp/Cntr=0.3,0.1

Type RM Length L Ch R = 1 ,97700.91,27.74,14.22,14.31
XS GIS Cut Line= 3
2966641.0098123613882983.89988432966873.8600684413879105.1399253
2966875.9325708613879009.9019268
#Sta/Elev= 30
       0  167.92   19.98  166.52    94.9  166.14  144.84  166.62  524.43  166.24
  534.41  166.72  579.37  166.85  789.14  166.23 1038.86  166.19 1293.58  166.35
 1328.54  168.12 1333.54  168.11 1343.53  166.68 1358.51  166.29 1718.11  165.49
 2542.22  166.08 2647.11  167.49  2657.1  166.51 2732.01  166.05 3571.11  165.81
    3671  166.37 3885.77  165.31 3904.83  165.78 3914.35  166.76 3923.89   166.5
 3935.44  163.89 3937.11  163.02 3957.22  165.99 3976.27  166.63 3981.03   166.7
#Mann= 3 ,-1 , 0
       0     .07       0 3914.35     .04       0 3976.27     .05       0
#XS Ineff= 2 ,-1
       0 1328.54     168 1328.54 3760.91   165.9
Permanent Ineff=
       F       F
Bank Sta=3914.35,3976.27
XS Rating Curve= 0 ,0
Exp/Cntr=0.3,0.1