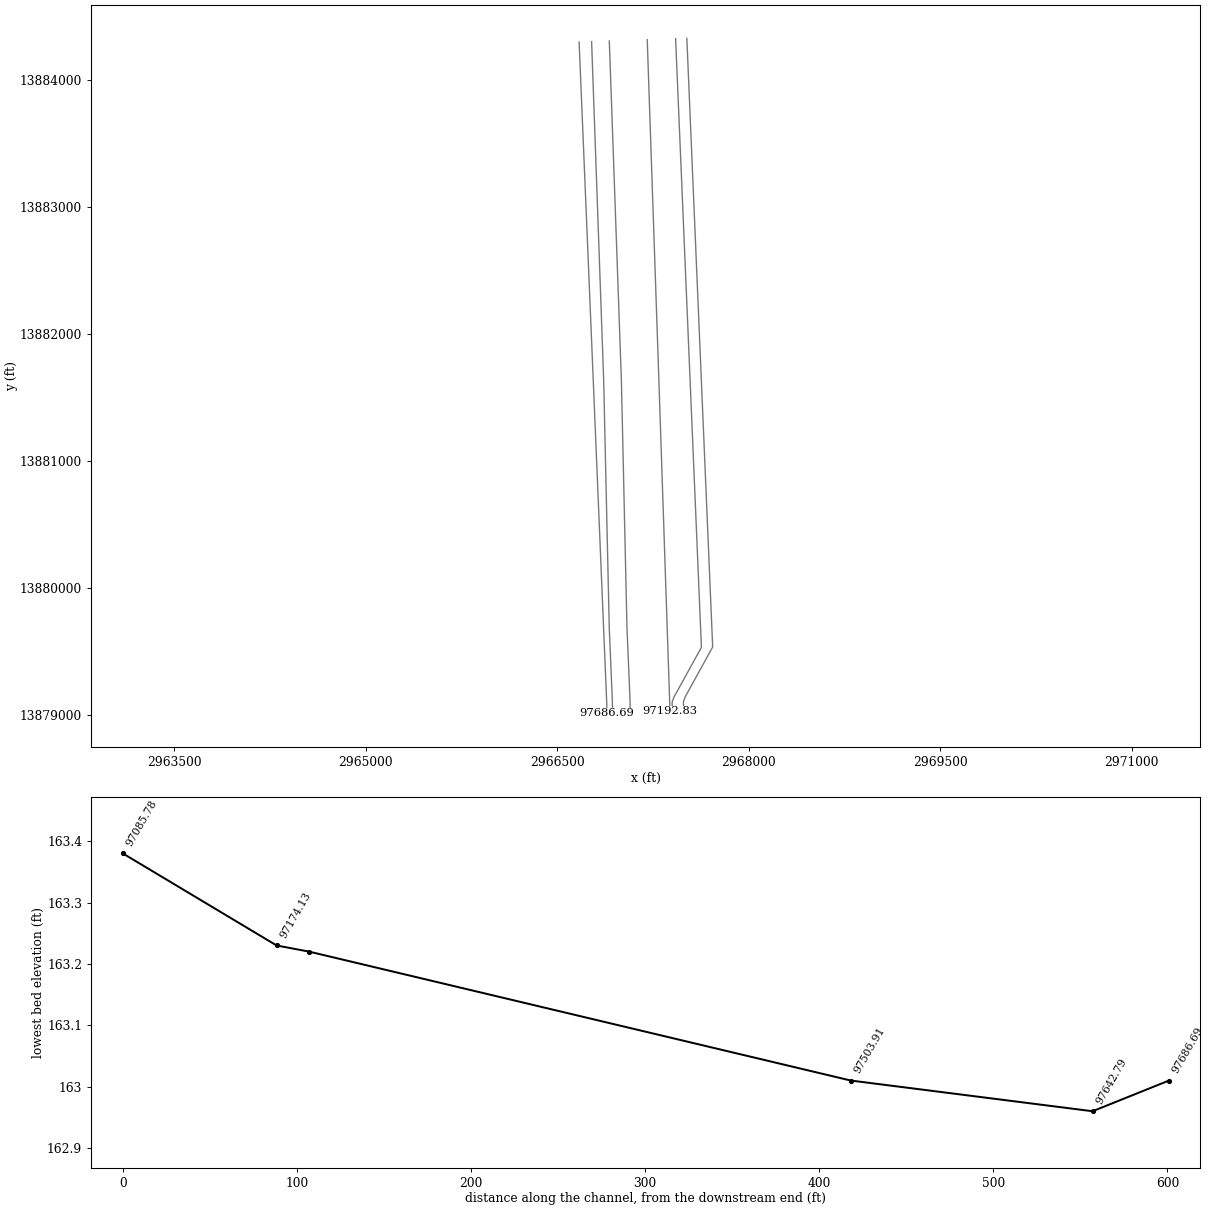
HEC-RAS study U101-00-00.prj: U101-00-00 2019 (Re-Study)

--- U101-00-00.g01 (geometry) --- (continued)

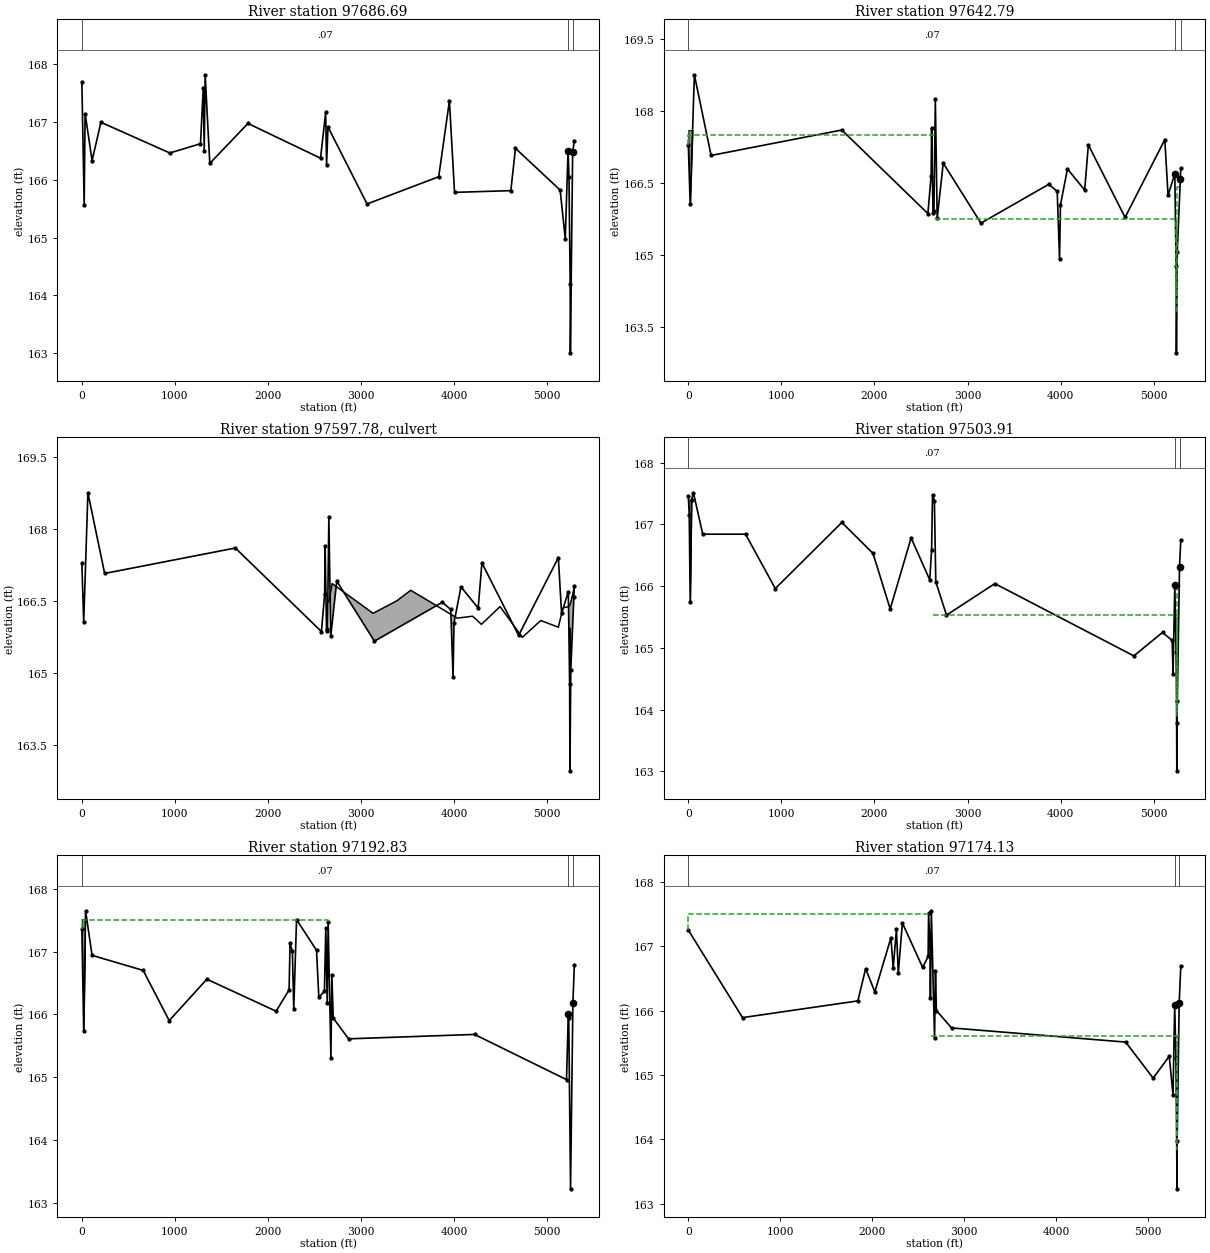
Type RM Length L Ch R = 1 ,97686.69,48.08,43.89,43.56
XS GIS Cut Line= 4
 2966671.550433713884296.77193042966888.5998683613879077.7400457
2966889.82985277 13879028.4501182966890.0296555313879010.3894586
#Sta/Elev= 30
       0  167.69   24.99  165.57   34.99  167.14  109.97  166.33  204.94  166.99
  944.74  166.46 1274.65  166.62 1304.64  167.59 1314.64   166.5 1324.63  167.81
 1374.62  166.28 1784.51  166.97 2564.29  166.37 2619.28  167.16 2629.27  166.25
 2644.27  166.91 3064.15  165.58 3833.94  166.05  3948.9  167.36 4003.89  165.78
 4608.71  165.81  4658.7  166.54 5138.56  165.82 5193.54  164.98 5223.53   166.5
 5233.39  166.05 5246.36  164.19 5248.58  163.01 5272.84  166.47  5290.9  166.67
#Mann= 3 ,-1 , 0
       0     .07       0 5223.53     .04       0 5272.84     .05       0
#XS Ineff= 2 ,-1
       0 2619.28  167.16 2619.31 5138.59   165.8
Permanent Ineff=
       F       F
Bank Sta=5223.53,5272.84
XS Rating Curve= 0 ,0
Exp/Cntr=0.5,0.3

Type RM Length L Ch R = 1 ,97642.79,138.72,138.88,139.09
BEGIN DESCRIPTION:
Upstream Section - ACCESS RD #4
END DESCRIPTION:
Node Name=BF
XS GIS Cut Line= 6
2966769.4577181913884300.35164772966864.17176761 13881628.255942
2966907.9039636113879679.57447192966932.05155312 13879109.288539
2966933.12307328  13879053.040622966933.3205794413879012.0479199
#Sta/Elev= 30
       0  167.28   19.99  166.05   64.97  168.75  244.89  167.07 1649.25   167.6
 2573.82  165.86 2608.81  166.65  2613.8  167.64  2628.8  165.88 2638.79  165.91
 2653.78  168.25 2673.78  165.76 2738.75  166.91 3143.58  165.66 3873.27  166.47
 3963.24  166.32 3988.23  164.91 3998.22  166.04 4073.19  166.79 4258.11  166.35
  4298.1  167.29 4692.45  165.78  5119.3   167.4 5154.05  166.24 5226.57  166.69
 5240.62  164.77 5243.89  162.96 5253.11  165.07 5286.45  166.59    5291  166.81
#Mann= 3 ,-1 , 0
       0     .07       0 5226.57     .04       0    5291     .05       0
#XS Ineff= 3 ,-1
       0 2653.78   167.5 2653.78 5241.74  165.74 5247.64    5291  166.42
Permanent Ineff=
       F       F       F
#Block Obstruct= 2 , 0
       0   64.97   167.6               0
Bank Sta=5226.57,5286.45
XS Rating Curve= 0 ,0
Exp/Cntr=0.5,0.3

Type RM Length L Ch R = 2 ,97597.78,,,
BEGIN DESCRIPTION:
ACCESS RD #4
END DESCRIPTION:
Node Name=ACCESS RD #4
Bridge Culvert--1,0,-1,-1, 0
Deck Dist Width WeirC Skew NumUp NumDn MinLoCord MaxHiCord MaxSubmerge Is_Ogee
35,25,2.6,0, 20, 20, , , 0.98, 0, 0,0,,
 2653.78 2688.77 3128.59 3383.48 3533.42 4033.21 4198.14  4293.1 4493.02 4732.16
 4930.69  5119.3 5168.94 5178.86 5212.51 5221.88 5226.57 5240.63 5254.57    5291
  166.48  166.86  166.24   166.5  166.72  166.14  166.18  166.01  166.38  165.74
  166.09  165.95  166.35  166.36  166.37  166.38  166.38   166.4  166.48  166.78
       0       0       0       0       0       0       0       0       0       0
       0       0       0       0       0       0       0       0       0       0
 2653.78 2688.77 3128.59 3383.48 3533.42 4033.21 4198.14  4293.1 4493.02 4732.16
 4930.69  5119.3 5168.94 5178.86 5212.51 5221.88 5226.57 5240.63 5254.57    5291
  166.48  166.86  166.24   166.5  166.72  166.14  166.18  166.01  166.38  165.74
  166.09  165.95  166.17  166.35  166.37  166.38  166.38  166.39  166.43  166.78
       0       0       0       0       0       0       0       0       0       0
       0       0       0       0       0       0       0       0       0       0
BR Coef=-1 , 0 , 0 ,, 0 ,,,0.8,-1,,0,
WSPro=,,,, 1 ,,,, 0 ,,,, 0 ,,,,-1 ,-1 ,-1 , 0 , 0 , 0 , 0 , 0
Culvert=1,2.5,,25,0.013,0.5,1,1,3,163.44,5242.99,163.35,5247.34,Culvert #1  , 0 ,35
Culvert Bottom n=0.013
Culvert=1,2.5,,25,0.013,0.5,1,1,3,163.4,5246.39,163.18,5250.74,Culvert #2  , 0 ,35
Culvert Bottom n=0.013
BC Design=,, 0 ,, 0 ,,,,,,
BC Use User HTab Curves=0
BC User HTab FreeFlow(D)= 0

Type RM Length L Ch R = 1 ,97503.91,312.99,311.08,311.66
BEGIN DESCRIPTION:
Downstream Section - ACCESS RD #4
END DESCRIPTION:
XS GIS Cut Line= 6
2966908.1011416913884304.87066752967002.8151911113881632.7749619
2967046.5473871113879684.09349182967070.6949766113879113.8075588
2967071.7664967813879057.55963992967071.9640029413879016.5669397
#Sta/Elev= 30
       0  167.45      10  167.15   19.99  165.74   34.98   167.4   54.97  167.51
  154.93  166.84  614.72  166.84  934.57  165.96 1649.25  167.03  1984.1  166.53
 2169.01  165.63 2393.91  166.78 2593.81   166.1  2613.8  166.59  2623.8  167.48
 2643.79  167.38 2658.78  166.07 2773.73  165.53 3293.52  166.04 4786.75  164.87
 5094.49  165.25 5198.44  165.12 5207.82  164.58 5226.57  166.01 5240.64  164.94
 5245.32  164.14 5248.24  163.01 5250.01  163.78 5277.34  166.31    5291  166.75
#Mann= 3 ,-1 , 0
       0     .07       0 5226.57     .04       0 5277.34     .05       0
#XS Ineff= 3 ,-1
       0  2623.8   167.3  2623.8 5246.09  165.54 5251.99    5291     166
Permanent Ineff=
       F       F       F
#Block Obstruct= 2 , 0
       0   34.98   167.4               0
Bank Sta=5226.57,5277.34
XS Rating Curve= 0 ,0
Exp/Cntr=0.5,0.3

Type RM Length L Ch R = 1 ,97192.83,259.95,18.7,18.98
XS GIS Cut Line= 6
2967205.3807308713884315.35161772967298.5101377813881576.1399045
2967381.1900905213879101.44012952967382.5644316113879068.7377671
2967383.6500593613879042.91006282967383.8767649413879027.4655399
#Sta/Elev= 30
       0  167.36   19.97  165.74   39.94  167.65  109.83  166.94  658.99   166.7
  938.56   165.9 1342.94  166.56 2086.81  166.05  2226.6  166.39 2236.58  167.13
 2261.54  167.01 2276.52  166.08 2306.47  167.51 2521.15  167.02 2546.11  166.27
 2606.02  166.37 2620.99  167.38 2635.97  166.18 2645.96  167.47 2675.91   165.3
 2685.89  166.62 2700.87  165.94 2865.61  165.61 4218.46  165.68 5206.92  164.96
 5226.25     166 5230.93  165.94 5250.31  163.22 5275.48  166.18 5290.93  166.78
#Mann= 3 ,-1 , 0
       0     .07       0 5226.25     .04       0 5275.48     .05       0
#XS Ineff= 2 ,-1
       0 2645.96   167.5 2645.96 5226.25   165.5
Permanent Ineff=
       F       F
#Block Obstruct= 2 , 0
       0   34.95  167.52               0
Bank Sta=5226.25,5275.48
XS Rating Curve= 0 ,0
Exp/Cntr=0.5,0.3

Type RM Length L Ch R = 1 ,97174.13,88.21,88.35,88.1
BEGIN DESCRIPTION:
Upstream Section - DRIVEWAY #10
END DESCRIPTION:
XS GIS Cut Line= 6
2967427.6063362813884323.38080112967629.9697766913879530.5265417
2967416.3970411113879141.37705752967403.2602563613879108.0257463
2967400.1795538713879090.15898412967403.9758061213879028.4438844
#Sta/Elev= 30
       0  167.25  589.65  165.89 1843.89  166.15 1928.84  166.65 2028.78  166.29
 2203.68  167.13 2228.66  166.66 2263.64  167.26 2283.63  166.58  2328.6  167.36
 2548.47  166.67 2608.43  166.84 2613.43  167.51 2628.42     167 2633.42  166.19
 2643.41  167.55 2678.39  165.57 2688.38  166.62 2698.38     166 2863.28  165.73
 4757.15  165.51 5056.49  164.95 5231.06  165.29  5272.4  164.69 5290.48  166.08
 5303.99  165.27 5316.16  163.23 5317.46  163.97 5339.33  166.12 5356.85  166.69
#Mann= 3 ,-1 , 0
       0     .07       0 5290.48     .04       0 5339.33     .05       0
#XS Ineff= 3 ,-1
       0 2643.41   167.5  2643.5 5312.55   165.6 5318.26 5356.85   165.6
Permanent Ineff=
       F       F       F
Bank Sta=5290.48,5339.33
XS Rating Curve= 0 ,0
Exp/Cntr=0.5,0.3

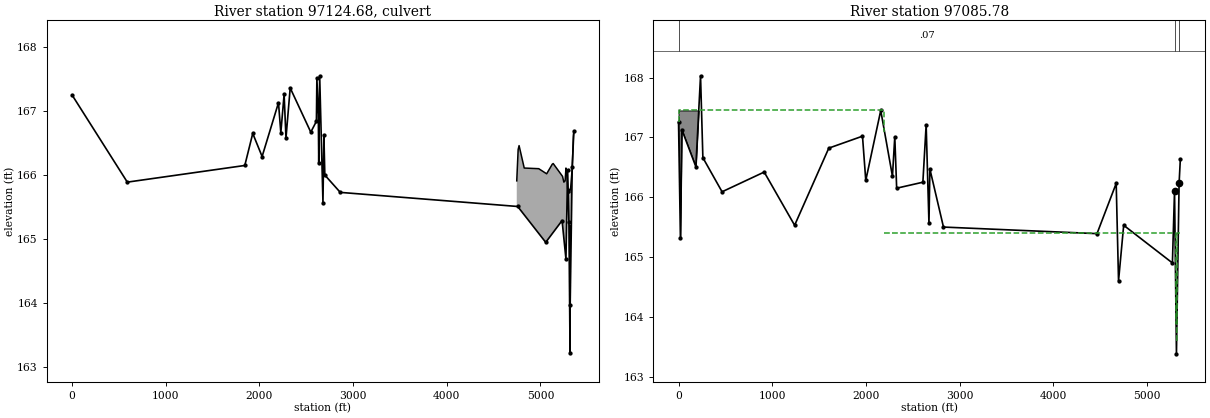
Type RM Length L Ch R = 2 ,97124.68,,,
BEGIN DESCRIPTION:
DRIVEWAY #10
END DESCRIPTION:
Node Name=DRIVEWAY #10
Bridge Culvert--1,0,-1,-1, 0
Deck Dist Width WeirC Skew NumUp NumDn MinLoCord MaxHiCord MaxSubmerge Is_Ogee
40,15,2.6,0, 21, 21, , , 0.98, 0, 0,0,,
 4747.16 4762.15 4772.14 4827.05 4981.67 5066.47 5126.32  5136.3 5236.05    5250
 5263.44  5272.4 5281.42 5290.48 5303.19 5311.37 5323.12 5335.06 5339.33 5352.14
 5356.85
  165.91   166.4  166.46  166.11   166.1  166.02  166.17  166.18  165.98  165.89
  165.91  166.11  166.05  165.79  165.78  165.72  165.81  166.03   166.1  166.61
  166.69
       0       0       0       0       0       0       0       0       0       0
       0       0       0       0       0       0       0       0       0       0
       0
 4747.16 4762.15 4772.14 4827.05 4981.67 5066.47 5126.32  5136.3 5236.05    5250
 5263.44  5272.4 5281.42 5290.48 5303.19 5311.37 5323.12 5335.06 5339.33 5352.14
 5356.85
  165.91   166.4  166.46  166.11   166.1  166.02  166.17  166.18  165.98  165.89
  165.91  166.11  166.05  165.79  165.78  165.72  165.81  166.03   166.1  166.61
  166.69
       0       0       0       0       0       0       0       0       0       0
       0       0       0       0       0       0       0       0       0       0
       0
BR Coef=-1 , 0 , 0 ,, 0 ,,,0.8,-1,,0,
WSPro=,,,, 1 ,,,, 0 ,,,, 0 ,,,,-1 ,-1 ,-1 , 0 , 0 , 0 , 0 , 0
Culvert=1,2,,25,0.013,0.5,1,1,3,163.22,5313.46,163.24,5312.76,Culvert #1  , 0 ,35
Culvert Bottom n=0.013
Culvert=1,2,,25,0.013,0.5,1,1,3,163.21,5317.26,163.22,5316.56,Culvert #2  , 0 ,35
Culvert Bottom n=0.013
BC Design=,, 0 ,, 0 ,,,,,,
BC Use User HTab Curves=0
BC User HTab FreeFlow(D)= 0

Type RM Length L Ch R = 1 ,97085.78,257.59,494.12,493.02
BEGIN DESCRIPTION:
Downstream Section - DRIVEWAY #10
END DESCRIPTION:
XS GIS Cut Line= 6
2967515.7419867813884325.86275152967718.1054271913879533.0084921
2967504.5326916113879143.85900792967491.3959068713879110.5076967
2967488.3152043713879092.6409345 2967492.111456613879030.9258348
#Sta/Elev= 30
       0  167.25   19.99  165.32   34.98  167.13  184.89  166.51  234.86  168.03
  259.84  166.66  464.72  166.09  914.45  166.42 1239.26  165.53 1604.04  166.82
 1963.82  167.02  1998.8  166.28  2158.7  167.45 2283.63  166.35 2308.61  167.01
  2328.6  166.15 2608.43  166.25 2643.41  167.21 2673.39  165.56 2683.39  166.47
  2828.3   165.5 4467.32  165.39  4672.2  166.23 4697.19   164.6 4752.15  165.53
  5272.4   164.9 5295.01  166.11 5315.46  163.38  5343.6  166.23 5356.85  166.63
#Mann= 3 ,-1 , 0
       0     .07       0 5295.01     .04       0  5343.6     .05       0
#XS Ineff= 3 ,-1
       0 2198.68  167.45 2198.68 5311.76   165.4 5317.56 5356.85   165.4
Permanent Ineff=
       F       F       F
#Block Obstruct= 2 , 0
       0  234.86  167.45               0
Bank Sta=5295.01,5343.6
XS Rating Curve= 0 ,0
Exp/Cntr=0.5,0.3