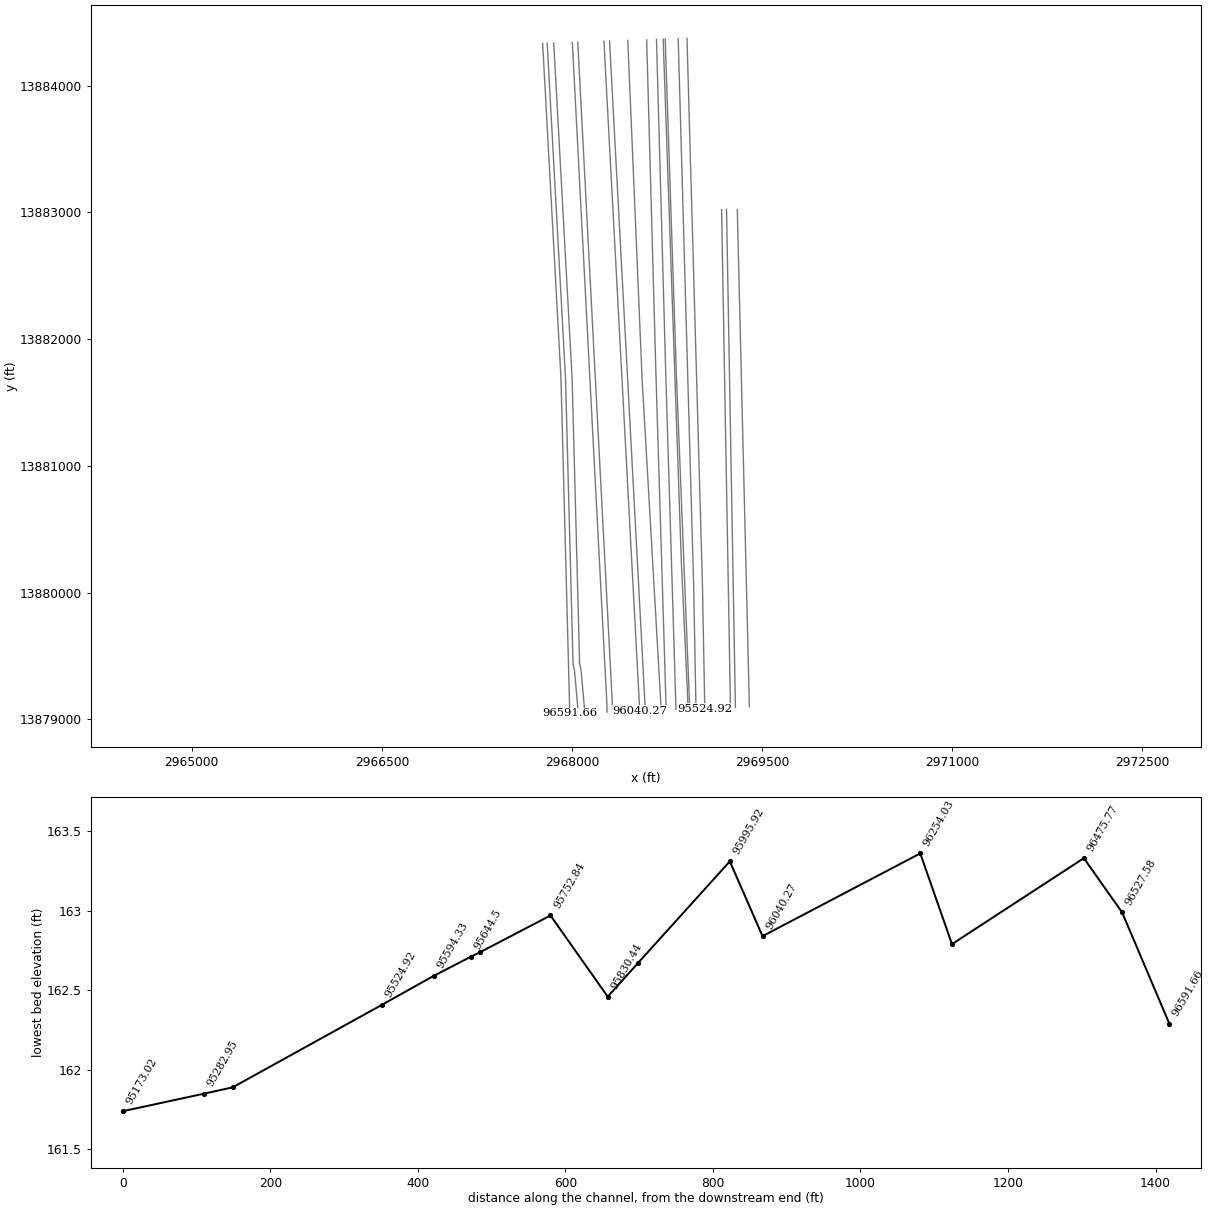
HEC-RAS study U101-00-00.prj: U101-00-00 2019 (Re-Study)

--- U101-00-00.g01 (geometry) --- (continued)

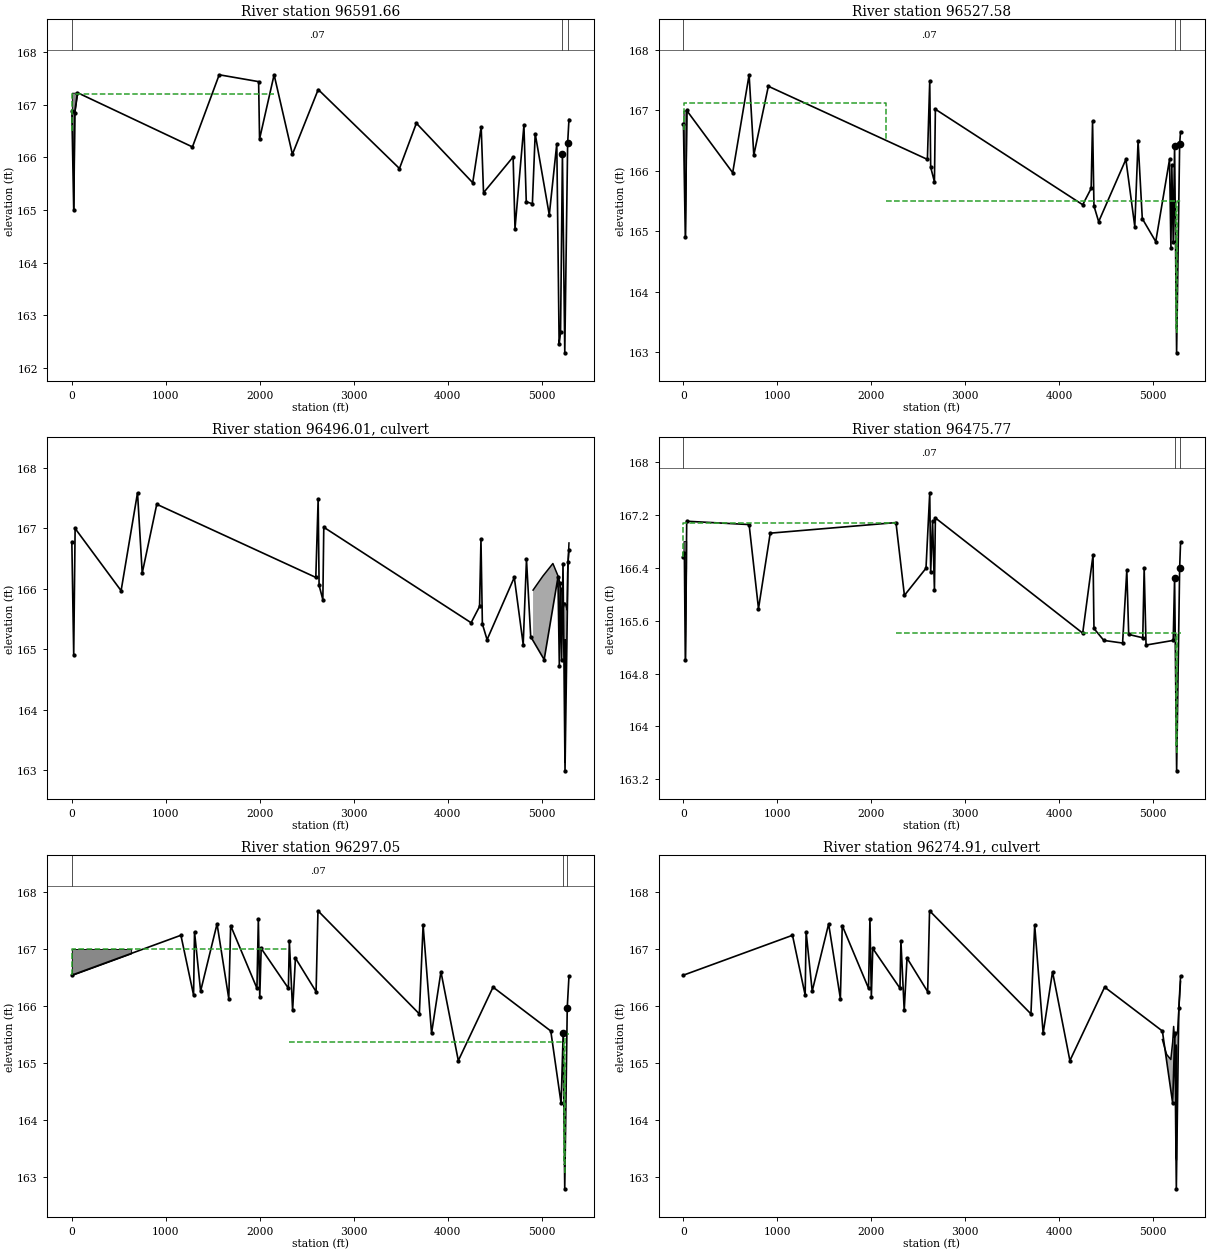
Type RM Length L Ch R = 1 ,96591.66,36.2,64.08,63.14
XS GIS Cut Line= 5
2967768.83203177 13884334.199349 2967913.282202213881695.2768054
 2967981.410018713879106.36990972967983.1400021213879065.5399389
2967983.2203825313879046.8001469
#Sta/Elev= 30
       0  166.89   19.98  165.01   29.98  166.85   59.95  167.23 1283.97   166.2
 1568.74  167.57  1988.4  167.44 1998.39  166.35 2153.27  167.57 2348.11  166.06
 2622.88  167.29 3487.81  165.79  3667.8  166.65 4267.75  165.52 4357.74  166.58
 4382.74  165.33 4697.71  166.01 4717.71  164.65  4812.7  166.61 4837.69  165.16
 4902.69  165.12 4932.69  166.45 5082.67  164.91 5162.66  166.26 5187.66  162.45
 5202.66  162.68 5222.66  166.06 5247.63  162.29 5278.21  166.27 5292.26  166.72
#Mann= 3 ,-1 , 0
       0     .07       0 5222.66     .04       0 5278.21     .05       0
#XS Ineff= 2 ,-1
     4.1 2149.01   167.2 2153.27 5162.66   165.5
Permanent Ineff=
       F       F
#Block Obstruct= 2 , 0
       0   59.95  167.23               0
Bank Sta=5222.66,5278.21
XS Rating Curve= 0 ,0
Exp/Cntr=0.5,0.3

Type RM Length L Ch R = 1 ,96527.58,51.77,51.81,51.75
BEGIN DESCRIPTION:
Upstream Section - DRIVEWAY #9
END DESCRIPTION:
Node Name=BE
XS GIS Cut Line= 6
2967804.7515793613884335.38241752967949.6991241113881687.3768868
2968008.95523919  13879435.598912968020.0890751913879386.9280756
2968045.9748501913879094.58745292968045.8557559413879050.6869502
#Sta/Elev= 30
       0  166.78   19.98  164.91   34.96     167   524.4  165.97   699.2  167.59
  749.14  166.26  903.97   167.4 2597.05  166.19 2622.02  167.49 2632.01  166.06
 2671.96  165.82 2681.95  167.02 4250.23  165.44 4340.13  165.71 4355.12  166.82
  4370.1  165.42 4420.05  165.16 4709.74  166.19 4804.63  165.08  4839.6  166.49
 4884.55  165.21  5027.8  164.83 5174.57  166.19 5189.25  164.73 5199.04  166.09
 5213.72  164.82 5228.39  166.42 5249.83  162.99  5282.1  166.44 5291.86  166.65
#Mann= 3 ,-1 , 0
       0     .07       0 5228.39     .04       0  5282.1     .05       0
#XS Ineff= 3 ,-1
    1.03 2152.55  167.13 2152.55 5247.33   165.5 5252.83 5291.86   165.5
Permanent Ineff=
       F       F       F
#Block Obstruct= 2 , 0
       0   34.96     167               0
Bank Sta=5228.39,5282.1
XS Rating Curve= 0 ,0
Exp/Cntr=0.5,0.3

Type RM Length L Ch R = 2 ,96496.01,,,
BEGIN DESCRIPTION:
DRIVEWAY #9
END DESCRIPTION:
Node Name=DRIVEWAY #9
Bridge Culvert--1,0,-1,-1, 0
Deck Dist Width WeirC Skew NumUp NumDn MinLoCord MaxHiCord MaxSubmerge Is_Ogee
23,14,2.6,0, 14, 14, , , 0.98, 0, 0,0,,
 4909.52 5013.13 5120.74 5184.36 5199.04 5213.72 5228.39 5238.18 5247.96 5252.84
 5262.59 5272.35 5277.23 5291.86
  165.98  166.21  166.42  166.18  166.03     166  165.68  165.72  165.77  165.76
  165.71  165.65  166.26  166.76
       0       0       0       0       0       0       0       0       0       0
       0       0       0       0
 4909.52 5013.13 5120.74 5184.36 5199.04 5213.72 5228.39 5238.18 5247.96 5252.84
 5262.59 5272.35 5277.23 5291.86
  165.98  166.21  166.42  166.18  166.03     166  165.68  165.72  165.77  165.76
  165.71  165.65  166.26  166.76
       0       0       0       0       0       0       0       0       0       0
       0       0       0       0
BR Coef=-1 , 0 , 0 ,, 0 ,,,0.8,-1,,0,
WSPro=,,,, 1 ,,,, 0 ,,,, 0 ,,,,-1 ,-1 ,-1 , 0 , 0 , 0 , 0 , 0
Culvert=1,2,,22,0.013,0.5,1,1,3,163.12,5248.33,163.24,5248.33,Culvert #1  , 0 ,17.5
Culvert Bottom n=0.013
Culvert=1,2,,22,0.013,0.5,1,1,3,163.17,5251.83,163.22,5251.83,Culvert #2  , 0 ,17.5
Culvert Bottom n=0.013
BC Design=,, 0 ,, 0 ,,,,,,
BC Use User HTab Curves=0
BC User HTab FreeFlow(D)= 0

Type RM Length L Ch R = 1 ,96475.77,187,178.71,179.21
BEGIN DESCRIPTION:
Downstream Section - DRIVEWAY #9
END DESCRIPTION:
XS GIS Cut Line= 6
2967856.4447174413884338.51659762968001.3922621913881690.5110669
2968060.6483772713879438.73309012968071.7822132713879390.0622557
2968097.66798827 13879097.7216332968097.5488940313879053.8211303
#Sta/Elev= 30
       0  166.56    9.99  166.62   19.98     165   34.96   167.1   699.2  167.05
  799.09  165.78  923.94  166.92 2262.43  167.08 2352.32  165.98 2582.06  166.39
 2622.02  167.53 2632.01  166.33 2651.98  167.11 2671.96  166.06 2681.95  167.15
 4250.23  165.41 4360.11  166.59  4370.1  165.48 4474.99   165.3 4674.77  165.26
 4719.73  166.36  4739.7  165.39 4889.54  165.34 4904.53  166.39  4924.5  165.23
 5213.72   165.3 5228.39  166.25 5250.08  163.33  5282.1  166.39 5291.86  166.78
#Mann= 3 ,-1 , 0
       0     .07       0 5228.39     .04       0  5282.1     .05       0
#XS Ineff= 3 ,-1
       0 2262.43  167.08 2262.43 5247.33  165.41 5252.83 5291.86  165.41
Permanent Ineff=
       F       F       F
#Block Obstruct= 2 , 0
       0   29.97   166.8               0
Bank Sta=5228.39,5282.1
XS Rating Curve= 0 ,0
Exp/Cntr=0.5,0.3

Type RM Length L Ch R = 1 ,96297.05,43.04,43.02,42.98
BEGIN DESCRIPTION:
Upstream Section - ACCESS RD #3
END DESCRIPTION:
XS GIS Cut Line= 5
2968003.1068256913884342.52544782968003.1990171113884340.7626561
2968275.5898765313879126.44828162968276.1951902813879103.4516084
2968277.3972876113879057.7660043
#Sta/Elev= 30
       0  166.54 1160.97  167.24 1295.88  166.19 1305.87   167.3 1370.83  166.26
 1545.71  167.44 1670.62  166.13 1690.61  167.41 1970.41  166.31  1985.4  167.53
 2000.39  166.15 2015.38  167.01 2305.18  166.31 2315.18  167.14 2350.15  165.92
 2380.13  166.84 2599.98  166.25 2619.96  167.67 3699.22  165.86 3739.19  167.42
 3829.13  165.52 3929.06   166.6 4113.93  165.04 4483.67  166.33 5098.25  165.56
 5208.17  164.29 5230.13  165.52 5246.85  162.79 5273.58  165.97 5291.87  166.52
#Mann= 3 ,-1 , 0
       0     .07       0 5230.13     .04       0 5273.58     .05       0
#XS Ineff= 3 ,-1
       0 2315.18     167 2315.18 5244.25  165.36 5249.25 5291.87  165.51
Permanent Ineff=
       F       F       F
#Block Obstruct= 2 , 0
       0  631.33     167               0
Bank Sta=5230.13,5273.58
XS Rating Curve= 0 ,0
Exp/Cntr=0.5,0.3

Type RM Length L Ch R = 2 ,96274.91,,,
BEGIN DESCRIPTION:
ACCESS RD #3
END DESCRIPTION:
Node Name=ACCESS RD #3
Bridge Culvert--1,0,-1,-1, 0
Deck Dist Width WeirC Skew NumUp NumDn MinLoCord MaxHiCord MaxSubmerge Is_Ogee
17,11,2.6,0, 10, 10, , , 0.98, 0, 0,0,,
 5098.25 5143.21 5188.18 5208.17 5218.16 5227.76 5259.87 5264.44 5278.16 5291.87
  165.41  165.15  165.06  165.37  165.64  165.44  165.55  165.67  166.06  166.43
       0       0       0       0       0       0       0       0       0       0
 5098.25 5143.21 5188.18 5208.17 5218.16 5227.76 5259.87 5264.44 5278.16 5291.87
  165.41  165.15  165.06  165.37  165.64  165.44  165.55  165.67  166.06  166.43
       0       0       0       0       0       0       0       0       0       0
BR Coef=-1 , 0 , 0 ,, 0 ,,,0.8,-1,,0,
WSPro=,,,, 1 ,,,, 0 ,,,, 0 ,,,,-1 ,-1 ,-1 , 0 , 0 , 0 , 0 , 0
Culvert=1,2,,20.5,0.013,0.5,1,1,3,163.32,5245.25,163.29,5245.25,Culvert #1  , 0 ,11
Culvert Bottom n=0.013
Culvert=1,2,,20.5,0.013,0.5,1,1,3,163.29,5248.25,163.14,5248.25,Culvert #2  , 0 ,11
Culvert Bottom n=0.013
BC Design=,, 0 ,, 0 ,,,,,,
BC Use User HTab Curves=0
BC User HTab FreeFlow(D)= 0

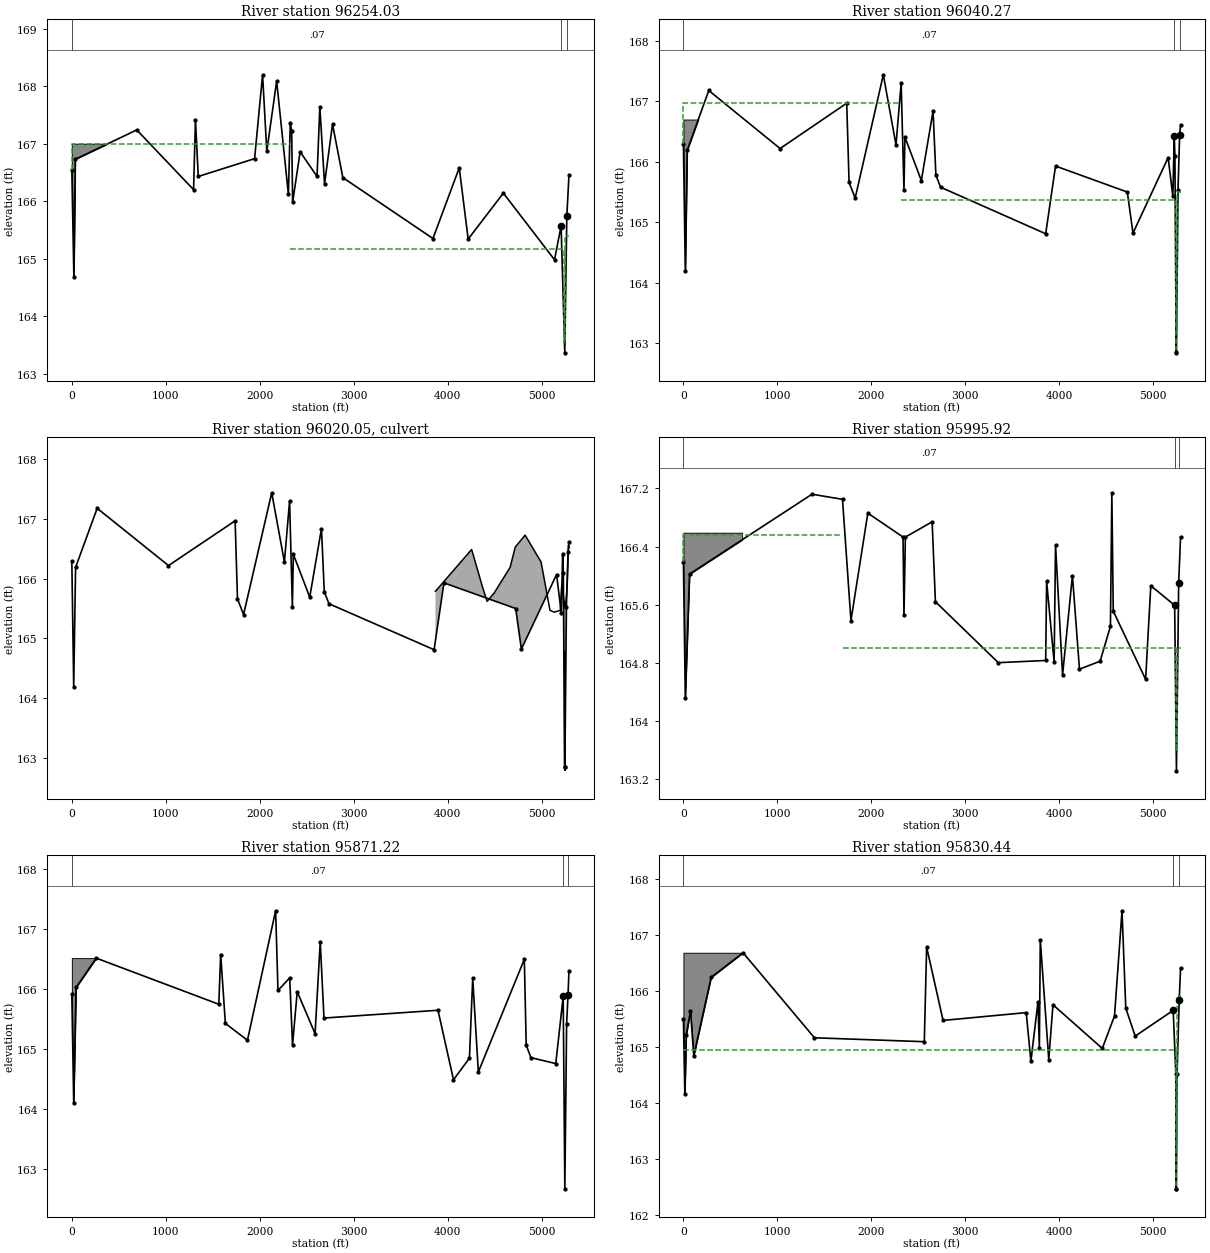
Type RM Length L Ch R = 1 ,96254.03,212.31,213.76,213.9
BEGIN DESCRIPTION:
Downstream Section - ACCESS RD #3
END DESCRIPTION:
XS GIS Cut Line= 5
2968046.0234065213884345.16651872968046.1155979513884343.4037269
2968318.5064573613879129.08935242968319.1117711113879106.0926793
2968320.3138684513879060.4070751
#Sta/Elev= 30
       0  166.55   21.75  164.68   36.74  166.73  691.29  167.24 1295.88   166.2
 1315.87  167.42 1345.84  166.43 1945.43  166.74 2030.37   168.2 2075.34  166.87
 2180.27  168.09 2305.18  166.12 2325.17  167.36 2340.16  167.23 2350.15  165.98
  2430.1  166.86 2609.97  166.43 2639.95  167.64 2689.92   166.3 2774.86  167.34
 2884.78  166.41 3844.12  165.35 4123.93  166.58 4218.86  165.34  4593.6  166.14
 5138.22  164.98 5208.17  165.57 5247.24  163.36 5269.01  165.74 5291.87  166.45
#Mann= 3 ,-1 , 0
       0     .07       0 5208.17     .04       0 5269.01     .05       0
#XS Ineff= 3 ,-1
       0 2325.17     167 2325.17 5244.25  165.17 5249.25 5291.87   165.4
Permanent Ineff=
       F       F       F
#Block Obstruct= 2 , 0
       0  621.34     167               0
Bank Sta=5208.17,5269.01
XS Rating Curve= 0 ,0
Exp/Cntr=0.5,0.3

Type RM Length L Ch R = 1 ,96040.27,44.38,44.35,44.31
BEGIN DESCRIPTION:
Upstream Section - DRIVEWAY #8
END DESCRIPTION:
XS GIS Cut Line= 4
2968252.6053424513884351.11138872968531.5972385313879133.3875722
2968532.7845721113879111.18322032968534.1569446913879066.2830476
#Sta/Elev= 30
       0  166.29   19.98  164.19   39.96  166.19  269.75  167.18 1029.05  166.22
  1738.4  166.97 1763.38  165.66 1828.32   165.4 2128.04  167.44 2262.92  166.28
 2317.87   167.3 2347.84  165.53 2357.83  166.41 2532.67  165.69 2657.56  166.84
 2687.53  165.78 2737.48  165.58 3856.46  164.81 3961.36  165.93 4725.64   165.5
 4785.58  164.82 5160.23  166.07 5210.18  165.43 5225.16  166.42 5232.34   166.1
 5245.77  162.85 5248.75  162.84 5265.21  165.53 5282.34  166.44 5292.32  166.61
#Mann= 3 ,-1 , 0
       0     .07       0 5225.16     .04       0 5282.34     .05       0
#XS Ineff= 3 ,-1
     -.1 2317.77  166.97 2317.87 5245.65  165.37 5251.05 5292.32   165.5
Permanent Ineff=
       F       F       F
#Block Obstruct= 2 , 0
       0  269.75   166.7               0
Bank Sta=5225.16,5282.34
XS Rating Curve= 0 ,0
Exp/Cntr=0.5,0.3

Type RM Length L Ch R = 2 ,96020.05,,,
BEGIN DESCRIPTION:
DRIVEWAY #8
END DESCRIPTION:
Node Name=DRIVEWAY #8
Bridge Culvert--1,0,-1,-1, 0
Deck Dist Width WeirC Skew NumUp NumDn MinLoCord MaxHiCord MaxSubmerge Is_Ogee
9.5,22,2.6,0, 18, 18, , , 0.98, 0, 0,0,,
 3871.45 4256.09 4375.97 4420.93 4495.86  4665.7 4720.64 4825.54 4995.38 5090.29
 5135.25 5200.19 5215.17 5252.39 5267.37 5272.36 5287.32 5292.32
  165.79  166.49  165.84  165.62  165.76  166.19  166.53  166.73  166.28  165.47
  165.44  165.47  165.89   165.5  165.75  165.84  166.56  166.52
       0       0       0       0       0       0       0       0       0       0
       0       0       0       0       0       0       0       0
 3871.45 4256.09 4375.97 4420.93 4495.86  4665.7 4720.64 4825.54 4995.38 5090.29
 5135.25 5200.19 5215.17 5252.39 5267.37 5272.36 5287.32 5292.32
  165.79  166.49  165.84  165.62  165.76  166.19  166.53  166.73  166.28  165.47
  165.44  165.47  165.89   165.5  165.75  165.84  166.56  166.52
       0       0       0       0       0       0       0       0       0       0
       0       0       0       0       0       0       0       0
BR Coef=-1 , 0 , 0 ,, 0 ,,,0.8,-1,,0,
WSPro=,,,, 1 ,,,, 0 ,,,, 0 ,,,,-1 ,-1 ,-1 , 0 , 0 , 0 , 0 , 0
Culvert=1,2,,22,0.013,0.5,1,1,3,162.78,5246.65,162.88,5246.65,Culvert #1  , 0 ,9.5
Culvert Bottom n=0.013
Culvert=1,2,,22,0.013,0.5,1,1,3,162.78,5250.05,162.88,5250.05,Culvert #2  , 0 ,9.5
Culvert Bottom n=0.013
BC Design=,, 0 ,, 0 ,,,,,,
BC Use User HTab Curves=0
BC User HTab FreeFlow(D)= 0

Type RM Length L Ch R = 1 ,95995.92,121.85,124.7,124.79
BEGIN DESCRIPTION:
Downstream Section - DRIVEWAY #8
END DESCRIPTION:
XS GIS Cut Line= 4
2968296.8513169413884353.93323342968575.8432130213879136.2094169
2968577.03054661 13879114.0050652968578.4029191913879069.1048924
#Sta/Elev= 30
       0  166.19   19.98  164.32   64.94  166.02 1368.74  167.12 1693.44  167.05
 1783.36  165.38 1963.19  166.86 2337.85  166.53 2347.84  165.45 2362.83  166.53
 2647.57  166.74 2682.53  165.64 3351.92   164.8 3856.46  164.83 3866.45  165.92
 3946.38  164.81 3961.36  166.42 4036.29  164.63  4141.2     166 4216.12  164.71
 4435.92  164.82 4545.81   165.3  4560.8  167.14 4575.78  165.51 4920.45  164.57
  4975.4  165.86 5229.61  165.59  5248.5  163.31 5272.36   165.9 5292.32  166.53
#Mann= 3 ,-1 , 0
       0     .07       0 5229.61     .04       0 5272.36     .05       0
#XS Ineff= 3 ,-1
    -.67 1692.78166.5602 1693.44 5245.66     165 5251.05 5292.32     165
Permanent Ineff=
       F       F       F
#Block Obstruct= 2 , 0
       0  624.42  166.59               0
Bank Sta=5229.61,5272.36
XS Rating Curve= 0 ,0
Exp/Cntr=0.5,0.3

Type RM Length L Ch R = 1 ,95871.22,61.41,40.78,40.6
XS GIS Cut Line= 5
2968440.8677611913884358.35251592968554.0000808513881681.6098379
2968700.5099584513879143.65001892968702.3600203513879098.0598869
2968703.3731416913879073.0911049
#Sta/Elev= 30
       0  165.92   19.99  164.11   44.99  166.03  259.92  166.52 1564.49  165.75
 1584.48  166.58 1634.47  165.43 1869.39  165.15 2169.29  167.31 2194.29  165.98
 2319.25  166.19 2349.24  165.07 2399.22  165.96 2589.16  165.26 2644.14  166.79
 2684.13  165.52 3897.77  165.65 4062.59  164.49  4232.4  164.85 4267.36  166.18
  4327.3  164.62 4816.77   166.5 4836.74  165.07 4886.69  164.86  5151.4  164.76
 5230.45  165.88 5247.93  162.67 5266.95  165.42 5281.95  165.91 5291.94   166.3
#Mann= 3 ,-1 , 0
       0     .07       0 5230.45     .04       0 5281.95     .05       0
#XS Ineff= 1 ,-1
       0 5177.25  164.95
Permanent Ineff=
       F
#Block Obstruct= 2 , 0
       0  259.92  166.52               0
Bank Sta=5230.45,5281.95
XS Rating Curve= 0 ,0
Exp/Cntr=0.5,0.3

Type RM Length L Ch R = 1 ,95830.44,77.55,77.59,77.53
BEGIN DESCRIPTION:
Upstream Section - DRIVEWAY #7
END DESCRIPTION:
XS GIS Cut Line= 4
2968589.8805865213884362.19601222968662.4024231113881744.5060376
2968742.4275255213879116.2809791 2968743.741171213879073.1360523
#Sta/Elev= 30
       0  165.49   14.99  164.15   29.99  165.21   74.96  165.64  109.95  164.84
  294.85  166.24  634.68  166.68 1394.31  165.16 2563.72  165.09 2588.71  166.78
 2763.66  165.47 3648.48  165.61 3698.47  164.74 3773.45   165.8 3788.45  164.98
 3798.45  166.91 3888.43  164.77 3933.42  165.75 4458.31  164.97 4588.28  165.55
 4668.26  167.43 4708.25  165.69 4808.23  165.19 5213.14  165.65 5240.84  164.52
 5243.76  162.46 5247.28  162.46    5254  164.52 5276.91  165.84  5291.3   166.4
#Mann= 3 ,-1 , 0
       0     .07       0 5213.14     .04       0 5276.91     .05       0
#XS Ineff= 2 ,-1
       0 5243.83  164.95 5249.63  5291.3   165.9
Permanent Ineff=
       F       F
#Block Obstruct= 2 , 0
       0  634.68  166.68               0
Bank Sta=5213.14,5276.91
XS Rating Curve= 0 ,0
Exp/Cntr=0.5,0.3

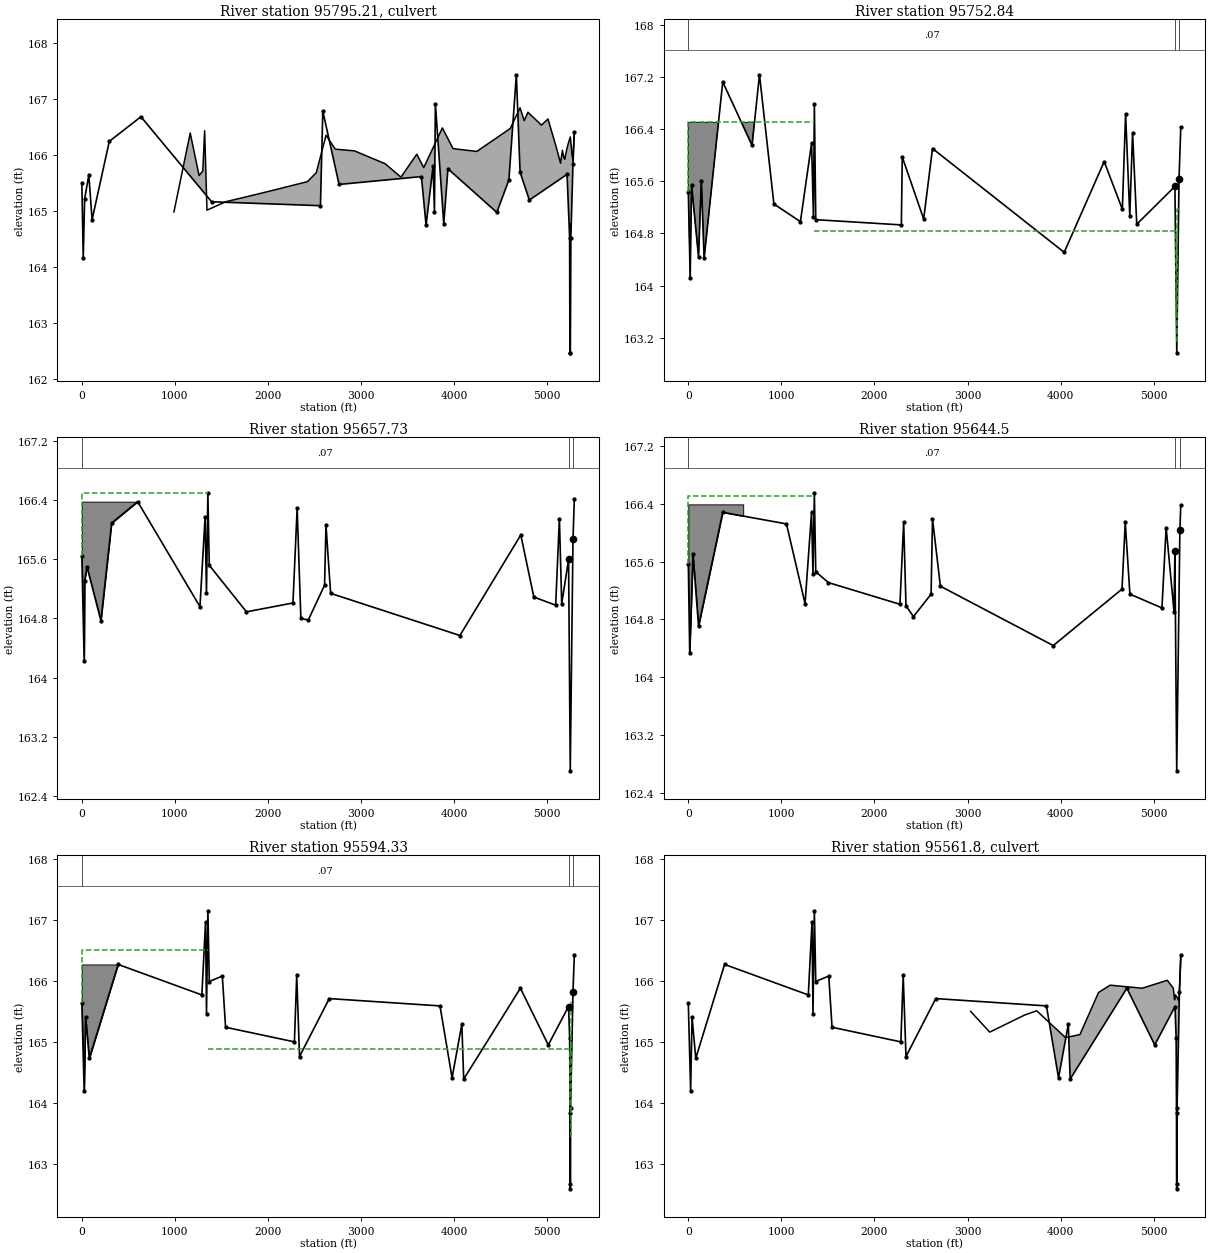
Type RM Length L Ch R = 2 ,95795.21,,,
BEGIN DESCRIPTION:
DRIVEWAY #7
END DESCRIPTION:
Node Name=DRIVEWAY #7
Bridge Culvert--1,0,-1,-1, 0
Deck Dist Width WeirC Skew NumUp NumDn MinLoCord MaxHiCord MaxSubmerge Is_Ogee
28.5,12.5,2.6,0, 40, 40, , , 0.98, 0, 0,0,,
  989.51 1164.42 1259.37 1299.35 1319.34 1344.33 1544.23 1944.03 2423.79 2518.74
 2623.69 2723.67 2928.63 3258.56 3428.52 3598.49 3673.47 3873.43 3988.41 4243.35
 4603.27 4708.25 4753.24 4793.23  4938.2 5008.18 5098.16 5143.15 5163.15 5178.15
 5188.14 5213.14 5223.14 5233.13 5248.13 5252.93 5267.32 5276.91  5286.5  5291.3
  164.98  166.39  165.63  165.71  166.43  165.01  165.16  165.32  165.52  165.68
  166.35   166.1  166.07  165.84   165.6  166.01  165.77  166.48  166.11  166.06
  166.47  166.84  166.61  166.76  166.53  166.64  166.13  165.85  166.08  165.95
  165.92  166.12  166.18  166.24  166.32  166.24  165.99   165.9  166.29  166.38
       0       0       0       0       0       0       0       0       0       0
       0       0       0       0       0       0       0       0       0       0
       0       0       0       0       0       0       0       0       0       0
       0       0       0       0       0       0       0       0       0       0
  989.51 1164.42 1259.37 1299.35 1319.34 1344.33 1544.23 1944.03 2423.79 2518.74
 2623.69 2723.67 2928.63 3258.56 3428.52 3598.49 3673.47 3873.43 3988.41 4243.35
 4603.27 4708.25 4753.24 4793.23  4938.2 5008.18 5098.16 5143.15 5163.15 5178.15
 5188.14 5213.14 5223.14 5233.13 5248.13 5252.93 5267.32 5276.91  5286.5  5291.3
  164.98  166.39  165.63  165.71  166.43  165.01  165.16  165.32  165.52  165.68
  166.35   166.1  166.07  165.84   165.6  166.01  165.77  166.48  166.11  166.06
  166.47  166.84  166.61  166.76  166.53  166.64  166.13  165.85  166.08  165.95
  165.92  166.12  166.18  166.24  166.32  166.24  165.99   165.9  166.29  166.38
       0       0       0       0       0       0       0       0       0       0
       0       0       0       0       0       0       0       0       0       0
       0       0       0       0       0       0       0       0       0       0
       0       0       0       0       0       0       0       0       0       0
BR Coef=-1 , 0 , 0 ,, 0 ,,,0.8,-1,,0,
WSPro=,,,, 1 ,,,, 0 ,,,, 0 ,,,,-1 ,-1 ,-1 , 0 , 0 , 0 , 0 , 0
Culvert=1,2,,25.8,0.013,0.5,1,1,3,162.78,5244.83,162.54,5244.83,Culvert #1  , 0 ,22
Culvert Bottom n=0.013
Culvert=1,2,,25.8,0.013,0.5,1,1,3,162.48,5248.63,162.54,5248.63,Culvert #2  , 0 ,22
Culvert Bottom n=0.013
BC Design=,, 0 ,, 0 ,,,,,,
BC Use User HTab Curves=0
BC User HTab FreeFlow(D)= 0

Type RM Length L Ch R = 1 ,95752.84,83.38,95.11,95.07
BEGIN DESCRIPTION:
Downstream Section - DRIVEWAY #7
END DESCRIPTION:
XS GIS Cut Line= 4
2968667.3194080313884366.35085952968739.8412446113881748.6608849
2968819.8663470313879120.43582642968821.1799926913879077.2908996
#Sta/Elev= 30
       0  165.44   19.99  164.12   34.98  165.54  109.95  164.44  139.93  165.61
  169.92  164.42  369.82  167.12  684.66  166.15  764.62  167.23  919.54  165.25
  1204.4  164.98 1324.34  166.18 1344.33  165.05 1354.33  166.78 1369.32  165.01
 2288.86  164.93 2298.85  165.97 2528.74  165.02 2623.69   166.1  4038.4  164.51
  4468.3   165.9 4663.26  165.17 4698.25  166.63 4743.24  165.07 4773.24  166.34
 4818.23  164.94 5228.14  165.52 5248.13  162.97 5272.11  165.63  5291.3  166.43
#Mann= 3 ,-1 , 0
       0     .07       0 5228.14     .04       0 5272.11     .05       0
#XS Ineff= 3 ,-1
       0 1354.33   166.5 1354.33 5243.83  164.84 5249.63  5291.3  165.17
Permanent Ineff=
       F       F       F
#Block Obstruct= 2 , 0
       0  764.62   166.5               0
Bank Sta=5228.14,5272.11
XS Rating Curve= 0 ,0
Exp/Cntr=0.5,0.3

Type RM Length L Ch R = 1 ,95657.73,17.56,13.23,13.53
XS GIS Cut Line= 4
2968720.1168746113884368.07165662968864.5998533713880213.8499782
2968913.6000834413879170.89012182968916.1141860313879080.4473893
#Sta/Elev= 30
       0  165.64   24.98  164.22   29.98  165.31   54.96   165.5  204.84  164.77
  319.75  166.09  599.53  166.38    1269  164.96 1323.96  166.17 1338.95  165.15
 1353.93   166.5 1368.92  165.52 1768.61  164.89 2268.21  165.01 2313.17  166.29
 2353.14   164.8 2433.08  164.78 2607.94  165.25 2622.93  166.06 2672.89  165.14
  4061.8  164.57 4716.24  165.93 4856.12  165.09 5090.92  164.98 5130.89  166.15
 5155.87     165  5229.4   165.6 5247.63  162.74 5277.02  165.88 5291.31  166.41
#Mann= 3 ,-1 , 0
       0     .07       0  5229.4     .04       0 5277.02     .05       0
#XS Ineff= 1 ,-1
       0 1353.93   166.5
Permanent Ineff=
       F
#Block Obstruct= 2 , 0
       0  599.53  166.38               0
Bank Sta=5229.4,5277.02
XS Rating Curve= 0 ,0
Exp/Cntr=0.3,0.1

Type RM Length L Ch R = 1 ,95644.5 ,66.58,50.18,49.76
XS GIS Cut Line= 6
2968736.0207141913884368.62513322968824.48018295 13881716.566789
2968925.9301112713879173.45015612968929.0101576113879105.0700435
2968929.1899472813879080.97986862968929.1906034513879080.8994882
#Sta/Elev= 30
       0  165.56   14.99  164.34   49.97   165.7  109.94  164.71   369.8  166.28
 1054.42  166.12 1254.31  165.02 1324.27  166.28 1339.26  165.43 1354.25  166.55
 1369.24  165.46 1504.17  165.31 2273.75  165.01 2313.73  166.14 2338.71  164.99
 2418.67  164.84 2608.57  165.15 2623.56  166.19 2708.44  165.26 3921.12  164.44
 4659.73  165.22 4694.66  166.14 4744.57  165.15 5088.93  164.96 5133.84  166.07
 5218.28  164.91 5228.06  165.74 5247.56  162.71 5281.63  166.04 5291.34  166.38
#Mann= 3 ,-1 , 0
       0     .07       0 5228.06     .04       0 5281.63     .05       0
#XS Ineff= 2 ,-1
       0 1354.25   166.5 1354.25 5165.36  164.89
Permanent Ineff=
       F       F
#Block Obstruct= 2 , 0
       0  589.67  166.39               0
Bank Sta=5228.06,5281.63
XS Rating Curve= 0 ,0
Exp/Cntr=0.5,0.3

Type RM Length L Ch R = 1 ,95594.33,69.48,69.4,69.4
BEGIN DESCRIPTION:
Upstream Section - DRIVEWAY #6
END DESCRIPTION:
XS GIS Cut Line= 5
2968838.6937371913884372.22420742968961.0182956913880041.1856254
2968977.4234466113879167.74642742968978.2616995313879126.5060243
2968979.1534300313879082.6452196
#Sta/Elev= 30
       0  165.63   24.99  164.19   39.98  165.41   79.96  164.73   389.8  166.27
 1289.34  165.77 1329.32  166.97 1339.31  165.46  1354.3  167.15 1369.29  165.99
 1509.22  166.08 1544.21  165.24 2283.83     165 2308.81  166.09  2338.8  164.76
 2658.63  165.71    3848  165.59 3977.93  164.41 4082.88  165.29 4102.87  164.39
 4712.16  165.88 5011.68  164.95 5229.29  165.58 5241.24  165.07 5246.34  163.84
  5247.3  162.59 5250.21  162.67 5251.48  163.91 5276.87  165.81 5291.49  166.43
#Mann= 3 ,-1 , 0
       0     .07       0 5229.29     .04       0 5276.87     .05       0
#XS Ineff= 3 ,-1
       0  1354.3   166.5  1354.3  5246.1  164.89    5251 5291.49  165.66
Permanent Ineff=
       F       F       F
#Block Obstruct= 2 , 0
       0   389.8  166.27               0
Bank Sta=5229.29,5276.87
XS Rating Curve= 0 ,0
Exp/Cntr=0.5,0.3

Type RM Length L Ch R = 2 ,95561.8 ,,,
BEGIN DESCRIPTION:
DRIVEWAY #6
END DESCRIPTION:
Node Name=DRIVEWAY #6
Bridge Culvert--1,0,-1,-1, 0
Deck Dist Width WeirC Skew NumUp NumDn MinLoCord MaxHiCord MaxSubmerge Is_Ogee
30,14,2.6,0, 17, 17, , , 0.98, 0, 2,1.5,,
 3033.43 3238.32 3613.12 3743.06 4052.89 4207.82 4407.64 4532.44  4876.9 5146.47
 5210.96 5224.71 5233.88  5252.5 5267.12    5272  5291.5
   165.5  165.16  165.44  165.51  165.07  165.12  165.81  165.93  165.88  166.01
  165.88  165.69  165.77  165.73  165.68  165.67  166.36
       0       0       0       0       0       0       0       0       0       0
       0       0       0       0       0       0       0
 3033.43 3238.32 3613.12 3743.06 4052.89 4207.82 4407.64 4532.44  4876.9 5146.47
 5210.96 5224.71 5233.88  5252.5 5267.12    5272  5291.5
   165.5  165.16  165.44  165.51  165.07  165.12  165.81  165.93  165.88  166.01
  165.88  165.69  165.77  165.73  165.68  165.67  166.36
       0       0       0       0       0       0       0       0       0       0
       0       0       0       0       0       0       0
BR Coef=-1 , 0 , 0 ,, 0 ,,,0.8,-1,,0,
WSPro=,,,, 1 ,,,, 0 ,,,, 0 ,,,,-1 ,-1 ,-1 , 0 , 0 , 0 , 0 , 0
Culvert=1,2,,25,0.013,0.5,1,1,3,162.6,5247.1,162.36,5247.1,Culvert #1  , 0 ,22
Culvert Bottom n=0.013
Culvert=1,2,,25,0.013,0.5,1,1,3,162.61,5250,162.37,5250,Culvert #2  , 0 ,22
Culvert Bottom n=0.013
BC Design=,, 0 ,, 0 ,,,,,,
BC Use User HTab Curves=0
BC User HTab FreeFlow(D)= 0

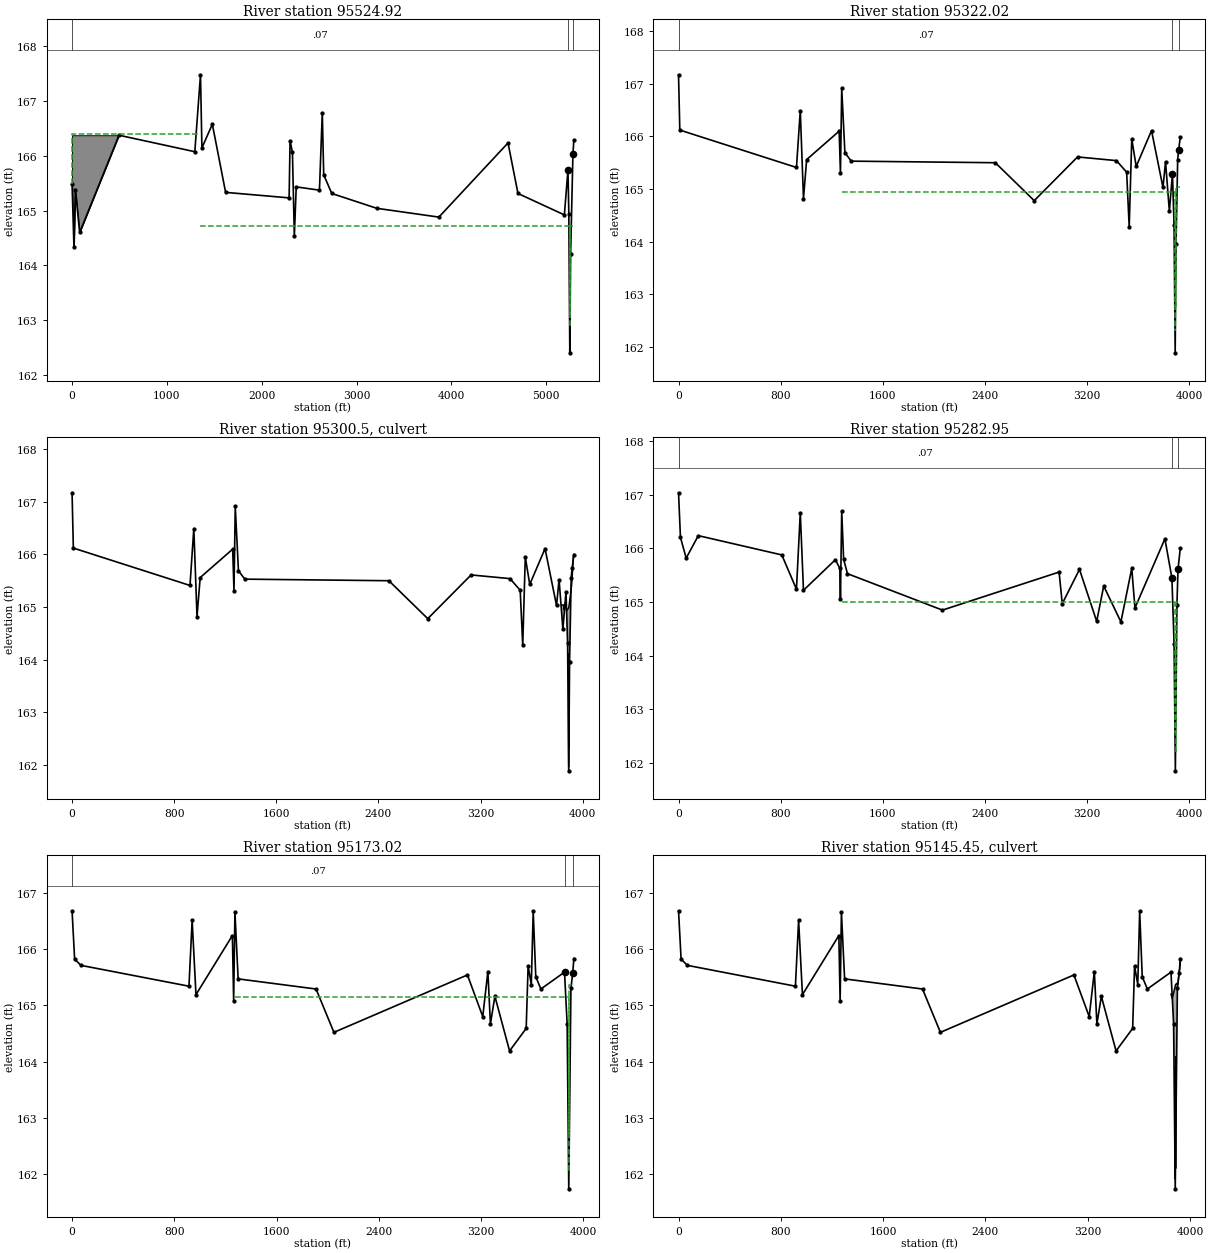
Type RM Length L Ch R = 1 ,95524.92,203.96,202.91,202.89
BEGIN DESCRIPTION:
Downstream Section - DRIVEWAY #6
END DESCRIPTION:
Node Name=BD
XS GIS Cut Line= 5
2968908.0551470213884374.31508242969030.3797055313880043.2765004
2969046.7848564413879169.83730242969047.6231093613879128.5968993
2969048.5148398613879084.7360947
#Sta/Elev= 30
       0  165.49   19.99  164.33   34.98  165.38   79.96   164.6  494.74  166.37
 1294.33  166.07  1354.3  167.47 1369.29  166.14 1479.24  166.57 1619.17  165.33
 2288.82  165.23 2298.82  166.27  2323.8  166.06 2343.79  164.53 2363.78  165.43
 2608.65  165.37 2638.64  166.78 2653.63  165.65 2738.59  165.31 3213.34  165.04
 3867.99  164.88 4597.34  166.23 4702.17  165.31  5191.4  164.92 5229.29  165.74
 5238.46  164.93 5248.66  162.41 5257.37  164.21 5281.75  166.03  5291.5  166.28
#Mann= 3 ,-1 , 0
       0     .07       0 5229.29     .04       0 5281.75     .05       0
#XS Ineff= 3 ,-1
       0  1354.3   166.4  1354.3  5246.1  164.72    5251  5291.5  164.72
Permanent Ineff=
       F       F       F
#Block Obstruct= 2 , 0
       0  494.74  166.37               0
Bank Sta=5229.29,5281.75
XS Rating Curve= 0 ,0
Exp/Cntr=0.5,0.3

Type RM Length L Ch R = 1 ,95322.02,39.04,39.07,39.11
BEGIN DESCRIPTION:
Upstream Section - ACCESS RD #2
END DESCRIPTION:
XS GIS Cut Line= 4
 2969181.191083713883021.9654249 2969250.053150713879157.1345719
2969250.5131235313879131.40004342969251.2312979413879091.2285358
#Sta/Elev= 30
       0  167.17    9.99  166.12  923.91  165.41  953.88  166.49  978.85  164.82
 1003.82  165.56 1258.52   166.1 1268.51   165.3 1278.49  166.91 1303.46  165.69
 1353.41  165.53 2482.08   165.5 2786.71  164.78 3126.31  165.61 3430.95  165.54
 3510.85  165.32 3530.83  164.28  3550.8  165.95 3585.76  165.43 3705.62  166.11
 3795.51  165.03 3815.49  165.52 3845.45  164.58 3869.72  165.29 3882.23  164.32
 3891.07  161.89 3897.68  163.96 3910.59  165.56 3917.95  165.74 3931.35  165.99
#Mann= 3 ,-1 , 0
       0     .07       0 3869.72     .04       0 3917.95     .05       0
#XS Ineff= 3 ,-1
       0 1278.49   166.4 1278.49 3889.57  164.94 3893.87 3931.35  165.03
Permanent Ineff=
       F       F       F
Bank Sta=3869.72,3917.95
XS Rating Curve= 0 ,0
Exp/Cntr=0.5,0.3

Type RM Length L Ch R = 2 ,95300.5 ,,,
BEGIN DESCRIPTION:
ACCESS RD #2
END DESCRIPTION:
Node Name=ACCESS RD #2
Bridge Culvert--1,0,-1,-1, 0
Deck Dist Width WeirC Skew NumUp NumDn MinLoCord MaxHiCord MaxSubmerge Is_Ogee
17,12,2.6,0, 15, 15, , , 0.98, 0, 0,0,,
 3835.47 3850.45 3855.44 3865.43 3874.01 3882.59 3886.88 3891.17 3895.63  3900.1
 3909.03 3913.49 3917.95 3926.88 3931.35
  165.04  165.04  164.95  165.09  164.93  164.96  164.97  164.99  165.06  165.15
  165.32  165.41  165.56  165.94     166
       0       0       0       0       0       0       0       0       0       0
       0       0       0       0       0
 3835.47 3850.45 3855.44 3865.43 3874.01 3882.59 3886.88 3891.17 3895.63  3900.1
 3909.03 3913.49 3917.95 3926.88 3931.35
  165.04  165.04  164.95  165.09  164.93  164.96  164.97  164.99  165.06  165.15
  165.32  165.41  165.56  165.94     166
       0       0       0       0       0       0       0       0       0       0
       0       0       0       0       0
BR Coef=-1 , 0 , 0 ,, 0 ,,,0.8,-1,,0,
WSPro=,,,, 1 ,,,, 0 ,,,, 0 ,,,,-1 ,-1 ,-1 , 0 , 0 , 0 , 0 , 0
Culvert=1,1.8,,18.5,0.013,0.5,1,1,3,161.96,3890.47,162.16,3890.47,Culvert #1  , 0 ,13.5
Culvert Bottom n=0.013
Culvert=1,1.8,,18.5,0.013,0.5,1,1,3,162.32,3892.97,162.22,3892.97,Culvert #2  , 0 ,13.5
Culvert Bottom n=0.013
BC Design=,, 0 ,, 0 ,,,,,,
BC Use User HTab Curves=0
BC User HTab FreeFlow(D)= 0

Type RM Length L Ch R = 1 ,95282.95,105.43,109.92,110.21
BEGIN DESCRIPTION:
Downstream Section - ACCESS RD #2
END DESCRIPTION:
XS GIS Cut Line= 4
 2969220.137856213883024.9716525 2969288.999923213879160.1407995
2969289.4598960313879134.40627092969290.1780704413879094.2347634
#Sta/Elev= 30
       0  167.04   14.98  166.21   59.93  165.82  154.82  166.24  809.05  165.88
  923.91  165.24  953.88  166.67  978.85  165.22 1228.55  165.79 1263.51  165.63
 1268.51  165.06 1278.49   166.7 1293.48   165.8 1323.44  165.53 2067.57  164.85
 2981.48  165.56 3006.45  164.97 3141.29  165.61 3276.13  164.64 3331.07   165.3
 3465.91  164.63  3550.8  165.63 3575.77  164.89  3810.5  166.18 3865.43  165.45
 3882.59  164.21  3892.5  161.85 3904.56  164.94 3913.49  165.62 3931.35  166.01
#Mann= 3 ,-1 , 0
       0     .07       0 3865.43     .04       0 3913.49     .05       0
#XS Ineff= 3 ,-1
       0 1278.49   166.4 1278.49 3889.57     165 3893.87 3931.35     165
Permanent Ineff=
       F       F       F
Bank Sta=3865.43,3913.49
XS Rating Curve= 0 ,0
Exp/Cntr=0.5,0.3

Type RM Length L Ch R = 1 ,95173.02,53.67,53.6,53.58
BEGIN DESCRIPTION:
Upstream Section - DRIVEWAY #5
END DESCRIPTION:
XS GIS Cut Line= 5
2969305.1265313613883021.84206562969399.0279183513879156.2395606
2969399.2480622813879139.73828132969399.8307382813879121.1123343
2969400.5502250213879098.1182858
#Sta/Elev= 30
       0  166.68   19.98  165.82   69.94  165.71  914.23  165.34  939.21  166.51
  969.18  165.19 1253.94  166.24 1263.93  165.08 1273.93  166.66  1298.9  165.47
 1908.39  165.29 2048.27  164.52 3092.39  165.54 3212.29   164.8 3252.25   165.6
 3272.24  164.67 3307.21  165.16 3422.11  164.19    3552  164.59 3566.99   165.7
 3591.97  165.37 3606.96  166.67 3626.94  165.51  3666.9  165.29 3851.75  165.59
 3872.35  164.67 3885.08  161.74 3901.87   165.3 3915.68  165.57 3924.88  165.83
#Mann= 3 ,-1 , 0
       0     .07       0 3851.75     .04       0 3915.68     .05       0
#XS Ineff= 3 ,-1
       0 1273.93   166.3 1273.93 3883.88  165.15 3889.68 3924.88  165.37
Permanent Ineff=
       F       F       F
Bank Sta=3851.75,3915.68
XS Rating Curve= 0 ,0
Exp/Cntr=0.5,0.3

Type RM Length L Ch R = 2 ,95145.45,,,
BEGIN DESCRIPTION:
DRIVEWAY #5
END DESCRIPTION:
Node Name=DRIVEWAY #5
Bridge Culvert--1,0,-1,-1, 0
Deck Dist Width WeirC Skew NumUp NumDn MinLoCord MaxHiCord MaxSubmerge Is_Ogee
11.5,32.5,2.6,0, 11, 11, , , 0.98, 0, 0,0,,
 3851.75 3861.74 3870.86 3874.99  3887.9 3897.21 3901.87 3906.47 3915.68 3920.28
 3924.88
   165.2  165.12  165.21  165.25  165.37  165.39  165.38  165.38  165.61  165.64
  165.77
       0       0       0       0       0       0       0       0       0       0
       0
 3851.75 3861.74 3870.86 3874.99  3887.9 3897.21 3901.87 3906.47 3915.68 3920.28
 3924.88
   165.2  165.12  165.21  165.25  165.37  165.39  165.38  165.38  165.61  165.64
  165.77
       0       0       0       0       0       0       0       0       0       0
       0
BR Coef=-1 , 0 , 0 ,, 0 ,,,0.8,-1,,0,
WSPro=,,,, 1 ,,,, 0 ,,,, 0 ,,,,-1 ,-1 ,-1 , 0 , 0 , 0 , 0 , 0
Culvert=1,2,,43,0.013,0.5,1,1,3,161.91,3884.88,161.79,3883.41,Culvert #1  , 0 ,6
Culvert Bottom n=0.013
Culvert=1,2,,43,0.013,0.5,1,1,3,162.1,3888.68,162.21,3887.21,Culvert #2  , 0 ,6
Culvert Bottom n=0.013
BC Design=,, 0 ,, 0 ,,,,,,
BC Use User HTab Curves=0
BC User HTab FreeFlow(D)= 0