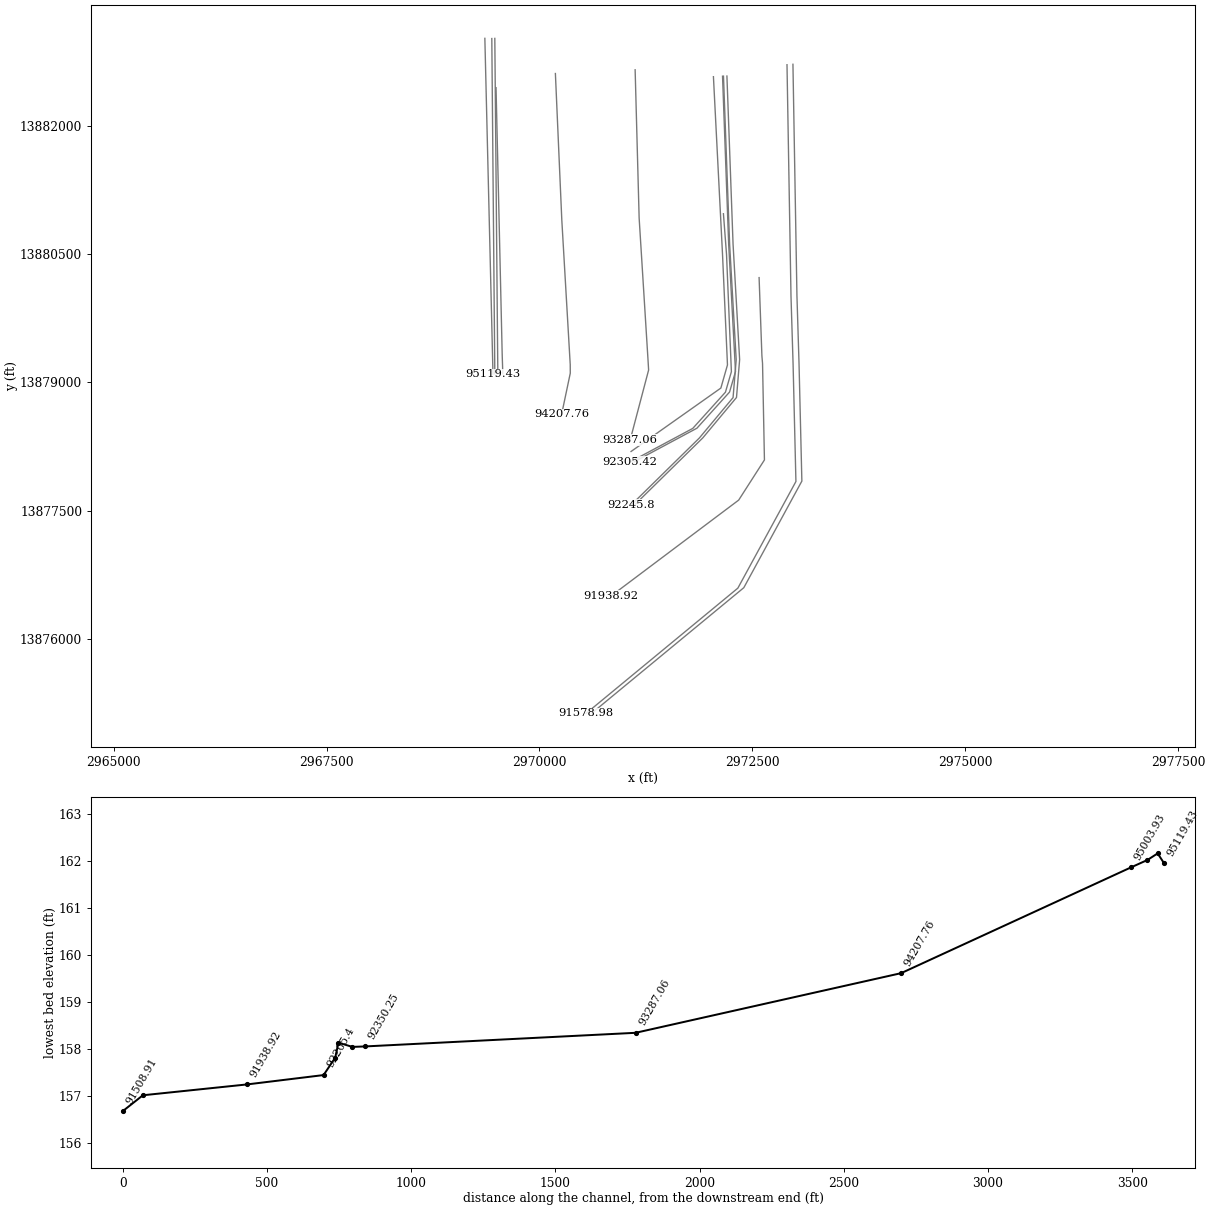
HEC-RAS study U101-00-00.prj: U101-00-00 2019 (Re-Study)

--- U101-00-00.g01 (geometry) --- (continued)

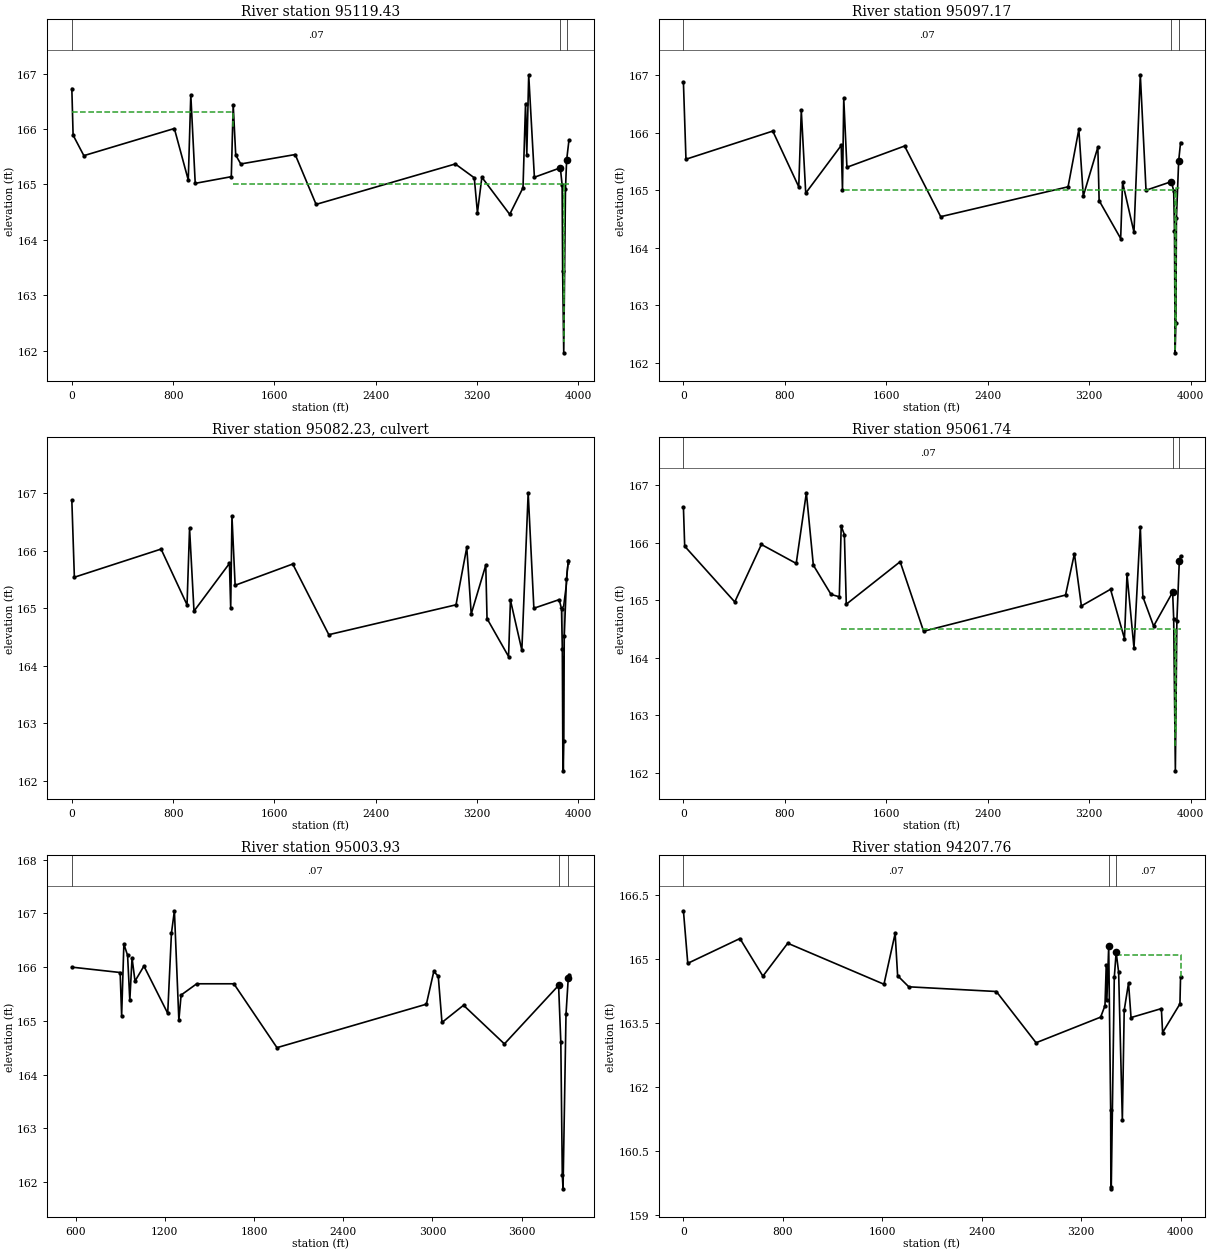
Type RM Length L Ch R = 1 ,95119.43,33.48,22.26,21.81
BEGIN DESCRIPTION:
Downstream Section - DRIVEWAY #5
END DESCRIPTION:
XS GIS Cut Line= 5
2969358.7169753613883022.08550342969452.6183623713879156.4829984
2969452.8385062813879139.98171912969453.4211822713879121.3557721
2969454.1406690313879098.3617236
#Sta/Elev= 30
       0  166.73    9.99  165.89   94.92  165.52  809.32  166.01  919.23  165.08
  939.21  166.62  974.18  165.02 1258.94  165.14 1273.93  166.44 1293.91  165.53
 1333.88  165.37 1763.51  165.54 1928.37  164.64 3027.44  165.37 3177.32  165.12
  3202.3  164.49 3237.27  165.13 3457.08  164.46 3561.99  164.94 3581.98  166.46
 3591.97  165.54 3606.96  166.98 3651.92  165.13 3856.74   165.3 3870.86  164.99
 3874.99  163.43 3883.61  161.96 3897.21  164.91 3906.47  165.44 3924.88   165.8
#Mann= 3 ,-1 , 0
       0     .07       0 3856.74     .04       0 3906.47     .05       0
#XS Ineff= 3 ,-1
       0 1268.93   166.3 1268.93 3882.41     165 3888.21 3924.88     165
Permanent Ineff=
       F       F       F
Bank Sta=3856.74,3906.47
XS Rating Curve= 0 ,0
Exp/Cntr=0.5,0.3

Type RM Length L Ch R = 1 ,95097.17,35.43,35.43,35.49
BEGIN DESCRIPTION:
Upstream Section - DRIVEWAY #4
END DESCRIPTION:
XS GIS Cut Line= 5
2969440.2588070313883019.62750312969475.0940391913879162.0968323
 2969475.062543213879141.21629672969475.0372807813879124.4482856
2969475.0002073613879099.5835059
#Sta/Elev= 30
       0  166.88   19.99  165.54  704.58  166.03  909.45  165.06  929.44  166.39
  964.42  164.95 1244.25  165.78 1254.25     165 1264.24   166.6 1289.23   165.4
 1743.96  165.77 2028.79  164.54 3033.18  165.06 3118.12  166.06  3153.1   164.9
 3268.03  165.75 3278.03  164.82 3447.92  164.16 3462.91  165.14 3552.86  164.27
 3602.83  167.01  3647.8     165 3847.68  165.15 3866.03  164.99 3872.36  164.29
 3877.19  162.17 3883.22  162.69 3887.62  164.51 3905.27  165.51 3920.19  165.83
#Mann= 3 ,-1 , 0
       0     .07       0 3847.68     .04       0 3905.27     .05       0
#XS Ineff= 3 ,-1
       0 1264.24   166.2 1264.24 3877.09     165 3882.29 3920.19  165.04
Permanent Ineff=
       F       F       F
Bank Sta=3847.68,3905.27
XS Rating Curve= 0 ,0
Exp/Cntr=0.5,0.3

Type RM Length L Ch R = 2 ,95082.23,,,
BEGIN DESCRIPTION:
DRIVEWAY #4
END DESCRIPTION:
Node Name=DRIVEWAY #4
Bridge Culvert--1,0,-1,-1, 0
Deck Dist Width WeirC Skew NumUp NumDn MinLoCord MaxHiCord MaxSubmerge Is_Ogee
10,18,2.6,0, 9, 9, , , 0.98, 0, 0,0,,
 3857.67  3870.2 3882.75 3891.13 3895.32 3905.27 3910.24 3920.19 3924.88
     165     165  165.04  165.19  165.26  165.43  165.63  165.84  165.77
       0       0       0       0       0       0       0       0       0
 3857.67  3870.2 3882.75 3891.13 3895.32 3905.27 3910.24 3920.19 3924.88
     165     165  165.04  165.19  165.26  165.43  165.63  165.84  165.77
       0       0       0       0       0       0       0       0       0
BR Coef=-1 , 0 , 0 ,, 0 ,,,0.8,-1,,0,
WSPro=,,,, 1 ,,,, 0 ,,,, 0 ,,,,-1 ,-1 ,-1 , 0 , 0 , 0 , 0 , 0
Culvert=1,2,,28.5,0.013,0.5,1,1,3,162.17,3878.09,162.01,3878.09,Culvert #1  , 0 ,4
Culvert Bottom n=0.013
Culvert=1,2,,28.5,0.013,0.5,1,1,3,162.17,3881.29,162.01,3881.29,Culvert #2  , 0 ,4
Culvert Bottom n=0.013
BC Design=,, 0 ,, 0 ,,,,,,
BC Use User HTab Curves=0
BC User HTab FreeFlow(D)= 0

Type RM Length L Ch R = 1 ,95061.74,45.65,57.82,58.33
BEGIN DESCRIPTION:
Downstream Section - DRIVEWAY #4
END DESCRIPTION:
XS GIS Cut Line= 5
 2969475.641282213883021.35420572969510.4765143513879163.8235349
2969510.4450183713879142.94299932969510.4197559513879126.1749882
2969510.3826825313879101.3102085
#Sta/Elev= 30
       0  166.62    9.99  165.94  404.76  164.97  614.63  165.97  889.47  165.64
  969.42  166.87 1024.39  165.61  1164.3   165.1 1229.26  165.06 1244.25  166.29
 1269.24  166.14 1284.23  164.93 1708.98  165.67 1893.87  164.46 3013.19  165.09
 3083.14  165.81 3138.11   164.9 3367.97  165.19 3477.91  164.33 3497.89  165.45
 3552.86  164.17 3602.83  166.28 3622.82  165.06 3707.77  164.55 3857.67  165.14
 3866.03  164.68 3879.19  162.03 3891.13  164.64 3910.24  165.68 3920.19  165.77
#Mann= 3 ,-1 , 0
       0     .07       0 3857.67     .04       0 3910.24     .05       0
#XS Ineff= 3 ,-1
       0 1244.25   166.2 1244.25 3877.09   164.5 3882.29 3920.19   164.5
Permanent Ineff=
       F       F       F
Bank Sta=3857.67,3910.24
XS Rating Curve= 0 ,0
Exp/Cntr=0.5,0.3

Type RM Length L Ch R = 1 ,95003.93,786.39,796.17,788.64
Node Name=BC
XS GIS Cut Line= 3
2969489.9539587813882445.38710462969562.5157803613879317.1585301
2969569.5361075313879103.0411762
#Sta/Elev= 30
  574.83     166  899.73   165.9  909.73  165.09  924.73  166.43  949.72  166.22
  964.71  165.38  979.71  166.17   999.7  165.74 1059.69  166.02 1219.64  165.14
 1244.63  166.63 1264.62  167.05 1294.62  165.01 1309.61  165.48 1414.58  165.69
 1664.51  165.69 1954.42   164.5 2959.12  165.31  3009.1  165.92 3039.09  165.83
 3064.08  164.97 3209.04  165.29 3483.96  164.57 3848.37  165.66 3863.32   164.6
 3873.28  162.13 3878.27  161.87  3898.2  165.12 3913.14  165.79 3918.12  165.86
#Mann= 3 ,-1 , 0
  574.83     .07       0 3848.37     .04       0 3913.14     .05       0
#XS Ineff= 1 ,-1
  574.83 1264.62     166
Permanent Ineff=
       F
Bank Sta=3848.37,3913.14
XS Rating Curve= 0 ,0
Exp/Cntr=0.3,0.1

Type RM Length L Ch R = 1 ,94207.76,934.16,920.7,889.48
Node Name=BB
XS GIS Cut Line= 5
2970186.9764736913882610.95771682970262.2633966113880899.1622559
2970361.1998785313879208.64004642970361.8199560213879108.8298785
2970259.8198319413878626.2386521
#Sta/Elev= 30
       0  166.13   34.97   164.9  454.59  165.48  639.42   164.6  839.24  165.37
 1613.54  164.41 1703.45   165.6 1723.43  164.61 1813.35  164.35 2517.69  164.24
 2837.39  163.04  3356.9  163.64 3391.87  163.91 3401.86  164.86 3406.85  164.03
 3421.82   165.3 3437.54  161.46 3439.35  159.66 3442.32  159.62 3466.74  164.57
 3481.71  165.16 3501.67  164.69 3531.58  161.22 3546.52   163.8  3581.4  164.44
 3601.33  163.63 3845.47  163.84 3855.43  163.28 3994.94  163.95 3999.92  164.59
#Mann= 3 ,-1 , 0
       0     .07       0 3421.82     .04       0 3481.71     .07       0
#XS Ineff= 3 ,-1
       0 1703.45   165.1 1703.45 3421.82     164    3481 3999.92   165.1
Permanent Ineff=
       F       F       F
Bank Sta=3421.82,3481.71
XS Rating Curve= 0 ,0
Exp/Cntr=0.3,0.1

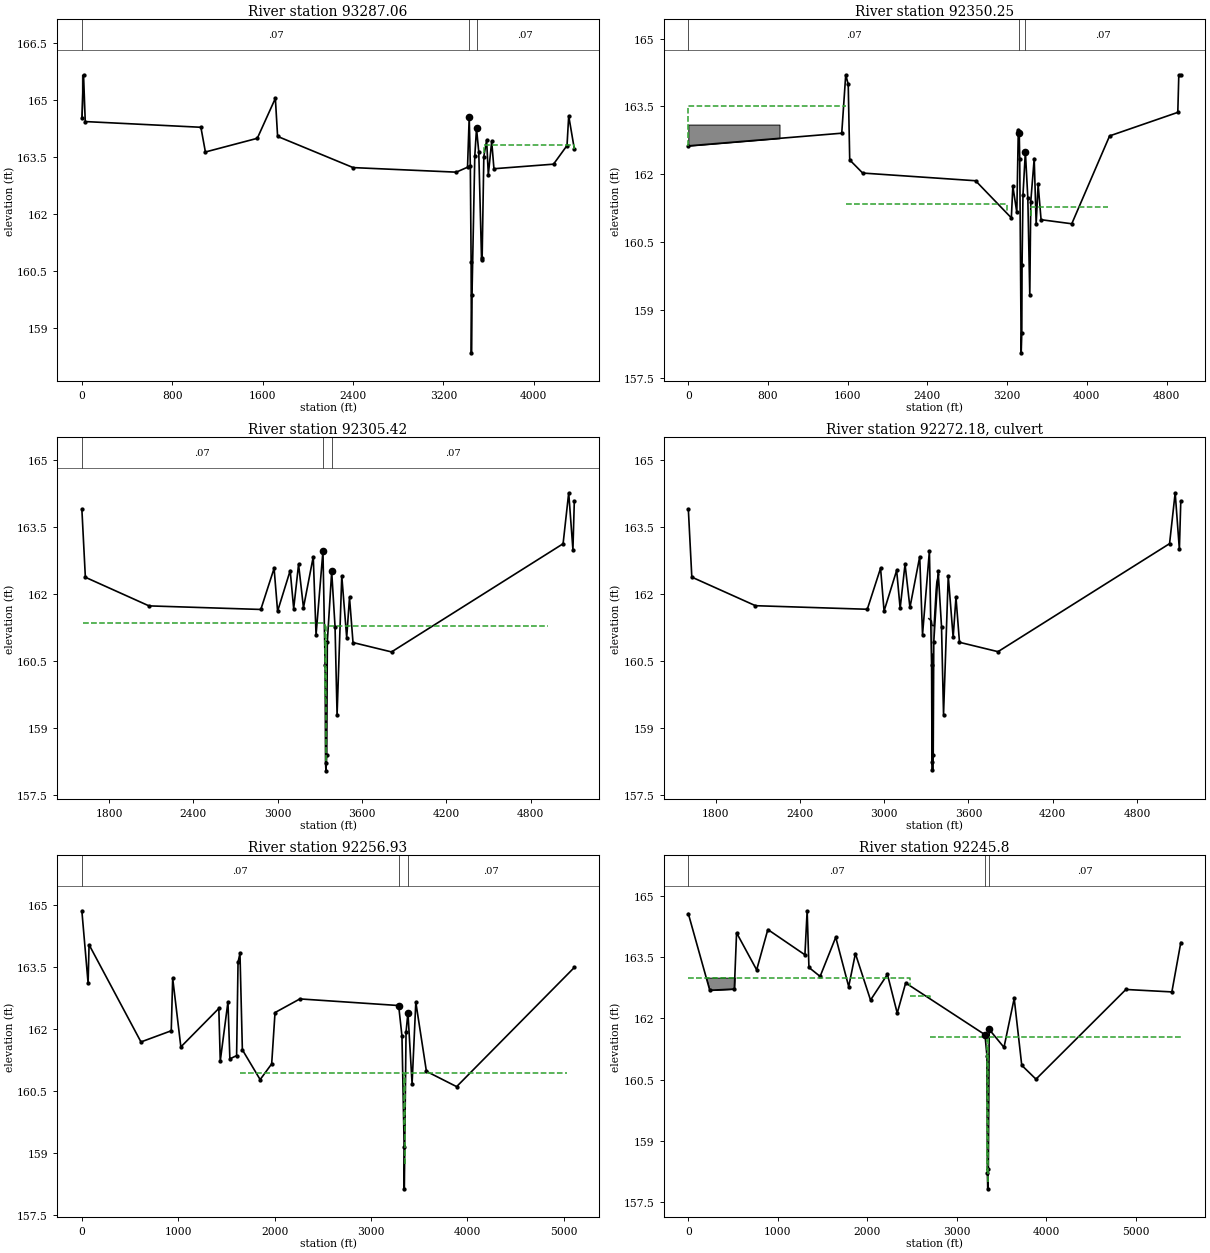
Type RM Length L Ch R = 1 ,93287.06,1052.58,936.81,345.76
XS GIS Cut Line= 5
2971123.3679736113882654.49831212971170.3616460313880922.6349779
2971276.09010911 13879240.0599312971281.6399667713879145.7999489
2971065.2355439413878328.2208754
#Sta/Elev= 30
       0  164.53   14.98  165.66   29.96  164.43 1053.48  164.28 1093.42  163.63
 1552.76  163.99 1712.53  165.04  1732.5  164.04 2400.87  163.22 3313.64   163.1
 3413.39  163.23 3428.32  164.56 3438.16  163.26 3445.14  160.74 3447.63  158.35
 3452.85  159.87 3477.54  163.52 3492.93  164.25 3512.81  163.63 3537.68  160.78
 3542.66  160.85 3557.58  163.51 3582.46  163.94 3597.38  163.03 3627.23  163.91
 3647.13  163.19 4174.48  163.31 4293.88   163.8  4308.8  164.58 4358.55  163.71
#Mann= 3 ,-1 , 0
       0     .07       0 3428.32     .04       0 3492.93     .07       0
#XS Ineff= 4 ,-1
       0 1712.53   164.2 1712.53 3428.32   163.5 3492.93 3562.56   163.5
 3562.56 4358.55  163.82
Permanent Ineff=
       F       F       F       T
#Block Obstruct= 2 , 0
       0    9.99  165.66  4308.8       0  164.58
Bank Sta=3428.32,3492.93
XS Rating Curve= 0 ,0
Exp/Cntr=0.3,0.1

Type RM Length L Ch R = 1 ,92350.25,45.52,44.83,140.39
XS GIS Cut Line= 6
2972042.7066861113882573.8006389 2972149.230095113880501.6099014
2972204.9501280313879265.69012912972207.4100968513879204.7000936
2972130.11563203 13878934.9384942971075.4477938613878193.5787563
#Sta/Elev= 30
       0  162.63 1539.94  162.91 1579.94   164.2 1604.94  163.99 1619.94  162.32
 1749.94  162.03 2883.09  161.86 3242.27  161.04 3257.24  161.74 3297.15  161.16
 3312.11  162.99  3321.5  162.91  3326.2  162.35 3341.03  158.06 3347.15   158.5
 3349.68  160.01 3359.07  161.55    3383   162.5 3407.61  161.48 3427.31  159.33
 3437.15   161.4 3471.61  162.35 3491.31  160.91    3511  161.78 3540.54     161
 3848.64  160.91  4228.4  162.85 4912.95  163.37 4922.94  164.19 4942.93  164.19
#Mann= 3 ,-1 , 0
       0     .07       0  3321.5     .04       0    3383     .07       0
#XS Ineff= 3 ,-1
       0 1579.94   163.5 1579.94 3198.22  161.35 3435.62 4215.98  161.29
Permanent Ineff=
       F       F       F
#Block Obstruct= 2 , 0
       0  914.97   163.1               0
Bank Sta=3321.5,3383
XS Rating Curve= 0 ,0
Exp/Cntr=0.5,0.3

Type RM Length L Ch R = 1 ,92305.42,49.06,48.49,21.12
BEGIN DESCRIPTION:
Upstream Section - ACCESS RD #1
END DESCRIPTION:
Node Name=BA
XS GIS Cut Line= 6
2972160.1184925313880972.29256052972196.4878746113880496.9301207
2972253.6144007713879126.11429282972183.5613912813878886.2932501
2971800.1694415213878463.48700912971063.73882778 13878070.944159
#Sta/Elev= 30
 1606.11  163.91 1631.05  162.38    2084  161.74 2879.85  161.66  2974.4  162.58
 2999.28  161.62 3088.86  162.53 3113.74  161.68 3148.57  162.67 3183.41   161.7
 3253.08  162.84 3272.98  161.09 3322.09  162.97 3337.58  160.41 3340.57  158.23
 3343.26  158.05 3349.15   158.4 3353.09  160.93 3384.26  162.51  3408.2  161.27
 3422.56   159.3 3456.08  162.41 3491.06  161.03 3511.05  161.93 3536.03  160.92
 3810.15  160.71 5031.23  163.13 5071.21  164.27 5101.19     163 5111.19  164.09
#Mann= 3 ,-1 , 0
 1606.11     .07       0 3322.09     .04       0 3384.26     .07       0
#XS Ineff= 3 ,-1
 1606.11 1616.08   163.2 1616.08 3338.62  161.35 3346.91 4924.86  161.29
Permanent Ineff=
       F       F       F
#Block Obstruct= 2 , 0
       0                 5071.21       0  164.27
Bank Sta=3322.09,3384.26
XS Rating Curve= 0 ,0
Exp/Cntr=0.5,0.3

Type RM Length L Ch R = 2 ,92272.18,,,
BEGIN DESCRIPTION:
ACCESS RD #1
END DESCRIPTION:
Node Name=ACCESS RD #1
Bridge Culvert--1,0,-1,-1, 0
Deck Dist Width WeirC Skew NumUp NumDn MinLoCord MaxHiCord MaxSubmerge Is_Ogee
27.5,14,2.6,0, 7, 7, , , 0.98, 0, 0,0,,
 3317.77 3336.15 3340.74 3355.07 3369.66 3374.53 3389.05
  161.45   161.4   161.3  161.29  162.09  162.27  162.44
       0       0       0       0       0       0       0
 3317.77 3336.15 3340.74 3355.07 3369.66 3374.53 3389.05
  161.45   161.4   161.3  161.29  162.09  162.27  162.44
       0       0       0       0       0       0       0
BR Coef=-1 , 0 , 0 ,, 0 ,,,0.8,-1,,0,
WSPro=,,,, 1 ,,,, 0 ,,,, 0 ,,,,-1 ,-1 ,-1 , 0 , 0 , 0 , 0 , 0
Culvert=1,2.5,,21,0.013,0.5,1,1,3,158.17,3339.86,158.04,3341.94,Culvert #1  , 0 ,23
Culvert Bottom n=0.013
Culvert=1,2.5,,21,0.013,0.5,1,1,3,158.04,3345.66,158.06,3347.74,Culvert #2  , 0 ,23
Culvert Bottom n=0.013
BC Design=,, 0 ,, 0 ,,,,,,
BC Use User HTab Curves=0
BC User HTab FreeFlow(D)= 0

Type RM Length L Ch R = 1 ,92256.93,11.24,11.12,299.7
BEGIN DESCRIPTION:
Downstream Section - ACCESS RD #1
END DESCRIPTION:
XS GIS Cut Line= 6
2972149.6224827813882579.25633662972221.7437296113880615.3416293
2972302.0601700213879128.04998442972232.0071605313878888.2289418
2971848.6152107713878465.42270082971112.1845970313878072.8798507
#Sta/Elev= 30
       0  164.86   64.84  163.11   74.82  164.04  613.51  161.69  927.75  161.96
  942.72  163.23 1027.51  161.57 1421.55   162.5 1436.52  161.23 1516.32  162.66
 1536.28  161.28 1606.11  161.36 1621.07  163.62 1641.02  163.83 1665.96   161.5
 1850.51  160.78 1970.18  161.16 2004.82   162.4 2263.01  162.73 3287.91  162.57
 3322.36  161.83 3345.34  159.14 3346.01  158.14  3364.8  161.93 3384.26   162.4
 3427.35  160.68 3466.08  162.65 3576.01  160.98 3889.56  160.61 5111.19  163.49
#Mann= 3 ,-1 , 0
       0     .07       0 3287.91     .04       0 3384.26     .07       0
#XS Ineff= 3 ,-1
       0 1641.02     163 1641.02  3340.7  160.95 3348.99 5034.78  160.95
Permanent Ineff=
       F       F       F
Bank Sta=3287.91,3384.26
XS Rating Curve= 0 ,0
Exp/Cntr=0.5,0.3

Type RM Length L Ch R = 1 ,92245.8 ,40.83,40.4,37.79
BEGIN DESCRIPTION:
Upstream Section - DRIVEWAY #3
END DESCRIPTION:
XS GIS Cut Line= 6
2972160.7176049513882580.03586262972232.8673950313880615.3416293
2972310.0873849413879266.32201762972273.2823404413878823.4731658
2971877.9261757713878351.78644512971076.4084218613877567.7319109
#Sta/Elev= 30
       0  164.57  239.51  162.69  513.96  162.72  538.91   164.1  763.45  163.19
   888.2  164.18 1302.36  163.56 1327.31  164.64 1347.27  163.25 1472.01  163.03
 1646.66  163.99 1791.37  162.78 1866.21  163.59 2035.29  162.45 2224.01  163.08
 2333.41  162.13 2427.89  162.87 3313.57   161.6 3335.53  161.08 3340.27  158.21
 3344.73  157.82 3351.15   158.3 3360.74  161.73 3525.88  161.29 3639.99  162.49
 3724.33  160.85 3883.15  160.51  4887.8  162.71 5401.09  162.65 5500.75  163.86
#Mann= 3 ,-1 , 0
       0     .07       0 3313.57     .04       0 3360.74     .07       0
#XS Ineff= 4 ,-1
       0 2477.62     163 2477.62 2701.48  162.55 2701.48 3340.38  161.54
 3347.08 5500.75  161.54
Permanent Ineff=
       F       F       F       F
#Block Obstruct= 2 , 0
       0   543.9     163               0
Bank Sta=3313.57,3360.74
XS Rating Curve= 0 ,0
Exp/Cntr=0.5,0.3

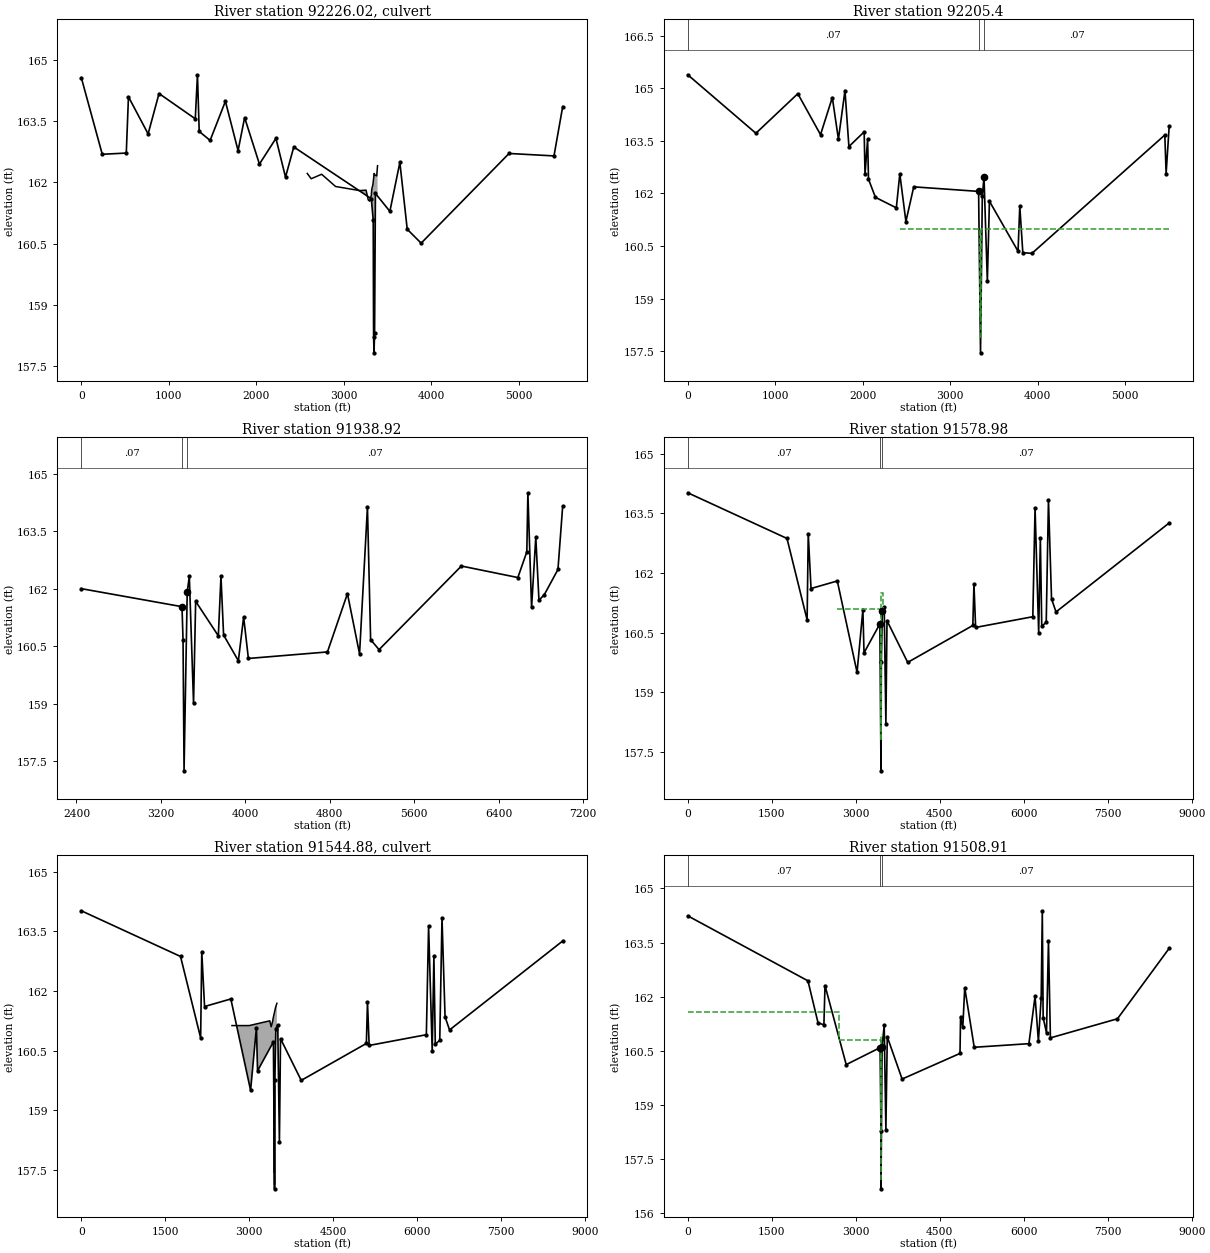
Type RM Length L Ch R = 2 ,92226.02,,,
BEGIN DESCRIPTION:
DRIVEWAY #3
END DESCRIPTION:
Node Name=DRIVEWAY #3
Bridge Culvert--1,0,-1,-1, 0
Deck Dist Width WeirC Skew NumUp NumDn MinLoCord MaxHiCord MaxSubmerge Is_Ogee
12,10,2.6,0, 15, 15, , , 0.98, 0, 2,2,,
 2582.04 2626.83 2746.26 2905.51 3179.21 3253.85 3278.74 3293.66 3313.57 3318.55
 3332.33 3346.11 3355.84 3375.31 3385.04
  162.22  162.09   162.2   161.9   161.8  161.81  161.57  161.54  161.68  161.83
  161.95  162.22  162.18  162.16  162.41
       0       0       0       0       0       0       0       0       0       0
       0       0       0       0       0
 2582.04 2626.83 2746.26 2905.51 3179.21 3253.85 3278.74 3293.66 3313.57 3318.55
 3332.33 3346.11 3355.84 3375.31 3385.04
  162.22  162.09   162.2   161.9   161.8  161.81  161.57  161.54  161.68  161.83
  161.95  162.22  162.18  162.16  162.41
       0       0       0       0       0       0       0       0       0       0
       0       0       0       0       0
BR Coef=-1 , 0 , 0 ,, 0 ,,,0.8,-1,,0,
WSPro=,,,, 1 ,,,, 0 ,,,, 0 ,,,,-1 ,-1 ,-1 , 0 , 0 , 0 , 0 , 0
Culvert=1,2.5,,24.8,0.013,0.5,1,1,3,157.85,3341.63,157.84,3341.63,Culvert #1  , 0 ,3
Culvert Bottom n=0.013
Culvert=1,2.5,,24.8,0.013,0.5,1,1,3,157.84,3345.83,157.83,3345.83,Culvert #2  , 0 ,3
Culvert Bottom n=0.013
BC Design=,, 0 ,, 0 ,,,,,,
BC Use User HTab Curves=0
BC User HTab FreeFlow(D)= 0

Type RM Length L Ch R = 1 ,92205.4 ,273.95,266.48,907.74
BEGIN DESCRIPTION:
Downstream Section - DRIVEWAY #3
END DESCRIPTION:
XS GIS Cut Line= 6
2972201.1026947813882581.24484972972273.2524848613880616.5506164
2972350.4724747813879267.53100472972313.6674302813878824.6821529
2971918.3112656213878352.99543222971116.7935116913877568.9408979
#Sta/Elev= 30
       0  165.39  778.42  163.72 1257.45  164.85 1516.92  163.68 1651.65  164.74
 1721.51  163.55 1796.36  164.94 1841.26  163.34 2015.49  163.76 2025.39  162.55
 2055.08  163.55 2064.98  162.41 2144.44  161.89 2383.13  161.59 2422.92  162.56
 2492.53   161.2 2582.04  162.19 3323.14  162.06 3345.18  157.45 3365.57  161.92
 3385.04  162.47 3423.11  159.49  3446.9  161.78 3773.95  160.35 3793.81  161.64
 3828.55  160.31 3932.79  160.29 5450.92  163.67 5465.87  162.57 5500.76  163.92
#Mann= 3 ,-1 , 0
       0     .07       0 3323.14     .04       0 3385.04     .07       0
#XS Ineff= 3 ,-1
       0 2422.92  162.56 2422.92 3340.39     161 3347.08 5500.76     161
Permanent Ineff=
       F       F       F
Bank Sta=3323.14,3385.04
XS Rating Curve= 0 ,0
Exp/Cntr=0.5,0.3

Type RM Length L Ch R = 1 ,91938.92,607.73,359.95,366.74
Node Name=AZ
XS GIS Cut Line= 6
2972578.9796079713880225.71796022972611.8800884513879312.0499445
2972619.3699028613879223.37000382972641.6500420313878094.8401086
2972339.2605549413877625.46145422970841.9210299413876506.1188766
#Sta/Elev= 30
 2445.97     162 3399.79  161.53 3409.67  160.66 3419.24  157.25 3449.23  161.92
 3469.21  162.32 3509.16  159.01 3529.14  161.67  3743.9  160.77 3768.87  162.32
 3793.84  160.79 3933.69  160.12 3983.63  161.26 4028.58  160.18  4777.4  160.35
 4966.84  161.87  5081.5   160.3 5156.33  164.13 5186.32  160.67  5266.3  160.41
 6046.07  162.59 6580.91  162.29 6665.89  162.96 6675.88   164.5 6710.87  161.51
 6750.86  163.34 6780.85   161.7 6830.84  161.84  6960.8   162.5 7005.78  164.16
#Mann= 3 ,-1 , 0
 2445.97     .07       0 3399.79     .04       0 3449.23     .07       0
#XS Ineff= 1 ,-1
 5156.33 7005.78   162.3
Permanent Ineff=
       F
Bank Sta=3399.79,3449.23
XS Rating Curve= 0 ,0
Exp/Cntr=0.5,0.3

Type RM Length L Ch R = 1 ,91578.98,83.77,70.07,71.55
BEGIN DESCRIPTION:
Upstream Section - DRIVEWAY #2
END DESCRIPTION:
XS GIS Cut Line= 6
2972906.5848796113882713.69209132972953.5378696913880008.3284076
2972978.0233850313879215.9756616 2973011.368462713877842.6299831
2972329.6349180313876596.6928424 2970548.014793613875132.9710324
#Sta/Elev= 30
       0  164.02 1772.23  162.87 2131.66  160.82 2151.63  162.99 2201.55  161.61
 2670.82   161.8 3023.67   159.5 3127.98  161.08 3147.85  159.99 3430.98  160.72
 3451.28  157.02 3457.28  159.75 3474.89  161.05 3508.49  161.15 3538.46   158.2
 3558.44   160.8 3928.11  159.75 5091.52  160.68 5111.45  161.73 5141.35  160.63
 6162.95   160.9 6202.82  163.64  6267.6  160.49 6297.51  162.88 6322.46  160.66
 6402.31  160.76 6442.24  163.84 6497.14  161.35 6576.99  161.02 8598.27  163.26
#Mann= 3 ,-1 , 0
       0     .07       0 3430.98     .04       0 3474.89     .07       0
#XS Ineff= 6 ,-1
       0 2670.82   161.8 2670.82 3447.03   161.1 3453.03 3493.78   161.5
 3493.78 5111.45   160.6 5111.45 6202.82  160.92 6202.82 8598.27  162.01
Permanent Ineff=
       F       F       F       F       F       F
Bank Sta=3430.98,3474.89
XS Rating Curve= 0 ,0
Exp/Cntr=0.5,0.3

Type RM Length L Ch R = 2 ,91544.88,,,
BEGIN DESCRIPTION:
DRIVEWAY #2
END DESCRIPTION:
Node Name=DRIVEWAY #2
Bridge Culvert--1,0,-1,-1, 0
Deck Dist Width WeirC Skew NumUp NumDn MinLoCord MaxHiCord MaxSubmerge Is_Ogee
29,12,2.6,0, 8, 8, , , 0.98, 0, 0,0,,
 2690.79 2998.83 3366.41 3391.24 3416.08 3426.01 3470.17 3493.78
  161.13  161.13  161.25   161.1  161.23  161.31  161.59  161.69
       0       0       0       0       0       0       0       0
 2690.79 2998.83 3366.41 3391.24 3416.08 3426.01 3470.17 3493.78
  161.13  161.13  161.25   161.1  161.23  161.31  161.59  161.69
       0       0       0       0       0       0       0       0
BR Coef=-1 , 0 , 0 ,, 0 ,,,0.8,-1,,0,
WSPro=,,,, 1 ,,,, 0 ,,,, 0 ,,,,-1 ,-1 ,-1 , 0 , 0 , 0 , 0 , 0
Culvert=1,2.5,,24.6,0.013,0.5,1,1,3,157.42,3448.28,157.66,3448.28,Culvert #1  , 0 ,22.5
Culvert Bottom n=0.013
Culvert=1,2.5,,24.6,0.013,0.5,1,1,3,157.12,3451.78,157.16,3451.78,Culvert #2  , 0 ,22.5
Culvert Bottom n=0.013
BC Design=,, 0 ,, 0 ,,,,,,
BC Use User HTab Curves=0
BC User HTab FreeFlow(D)= 0

Type RM Length L Ch R = 1 ,91508.91,93.02,90.99,80.86
BEGIN DESCRIPTION:
Downstream Section - DRIVEWAY #2
END DESCRIPTION:
XS GIS Cut Line= 6
 2972976.423650713882718.84135932973023.3766407813880013.4776755
2973047.8621561113879221.12492952973081.20723377 13877847.779251
2972399.4736891113876601.84211042970617.8535646913875138.1203003
#Sta/Elev= 30
       0  164.24 2146.64  162.44 2326.36  161.28 2431.19  161.22 2451.16  162.31
 2829.94  160.12 3435.04  160.59 3451.28  158.29 3451.85  156.68 3470.17  160.62
 3508.49  161.21 3538.46  158.31 3563.44  160.89  3828.2  159.72 4862.26  160.43
 4872.25  161.45 4912.12  161.15    4947  162.25 5116.44   160.6 6093.18   160.7
 6202.82  162.01 6262.62  160.77 6312.48  161.97 6332.44  164.38 6347.42  161.42
 6407.31     161 6442.24  163.53 6477.18  160.86 7674.96  161.39 8598.27  163.34
#Mann= 3 ,-1 , 0
       0     .07       0 3435.04     .04       0 3470.17     .07       0
#XS Ineff= 6 ,-1
       0 2695.78  161.58 2695.78 3447.03   160.8 3453.03 3493.78  160.95
 3493.78    4947   160.5    4947 6202.82     161 6202.82 8598.38  162.01
Permanent Ineff=
       F       F       F       F       F       F
Bank Sta=3435.04,3470.17
XS Rating Curve= 0 ,0
Exp/Cntr=0.5,0.3