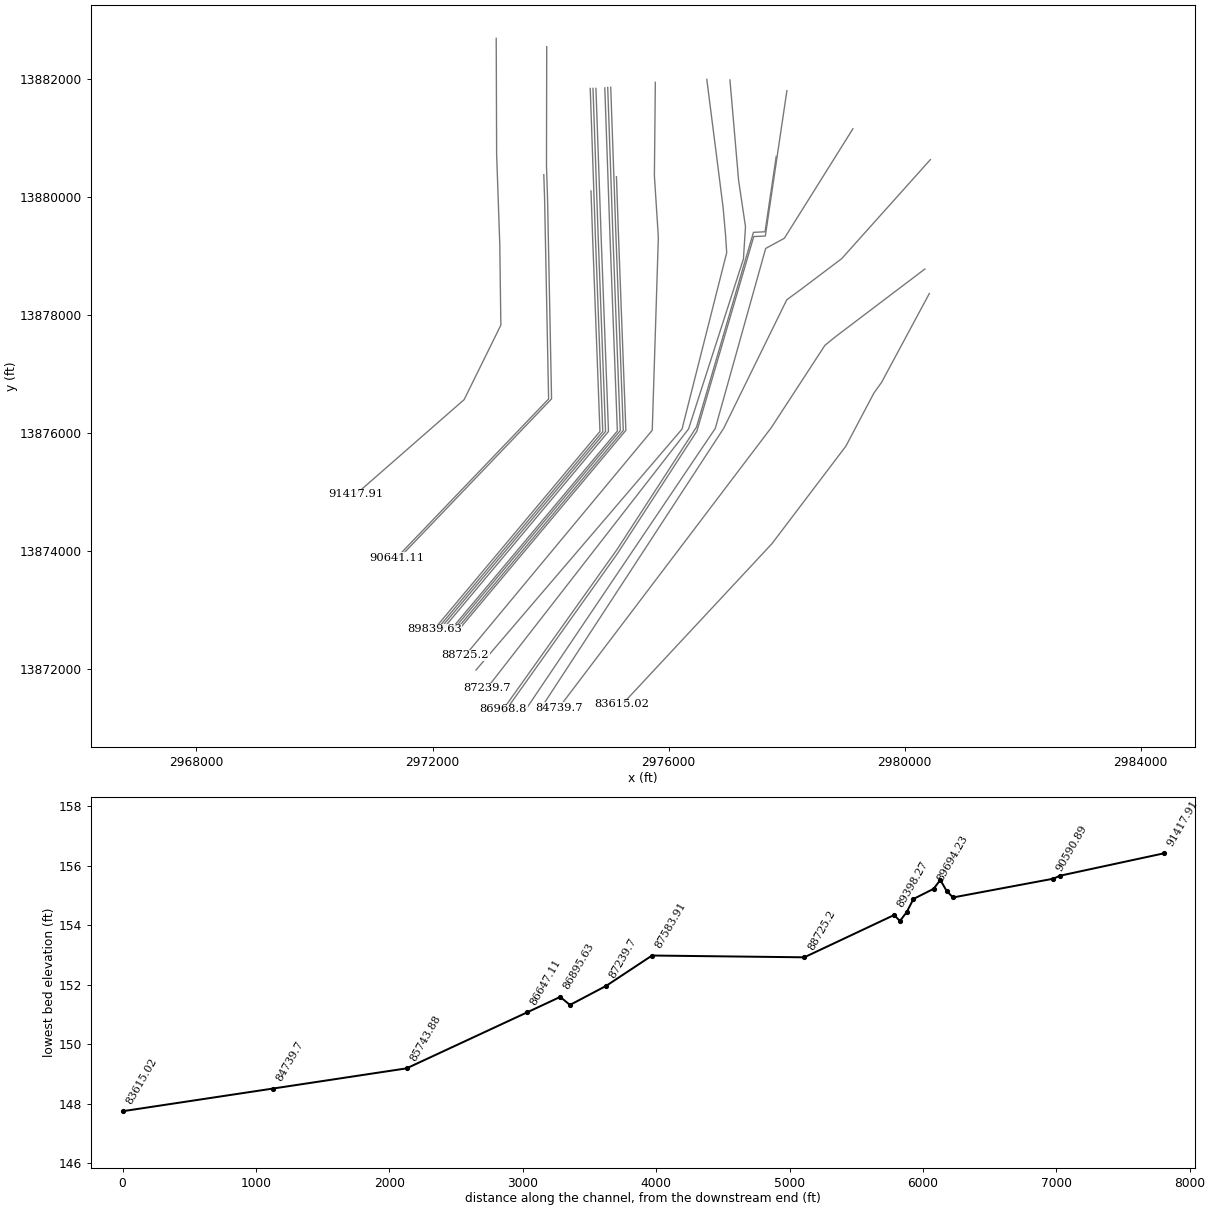
HEC-RAS study U101-00-00.prj: U101-00-00 2019 (Re-Study)

--- U101-00-00.g01 (geometry) --- (continued)

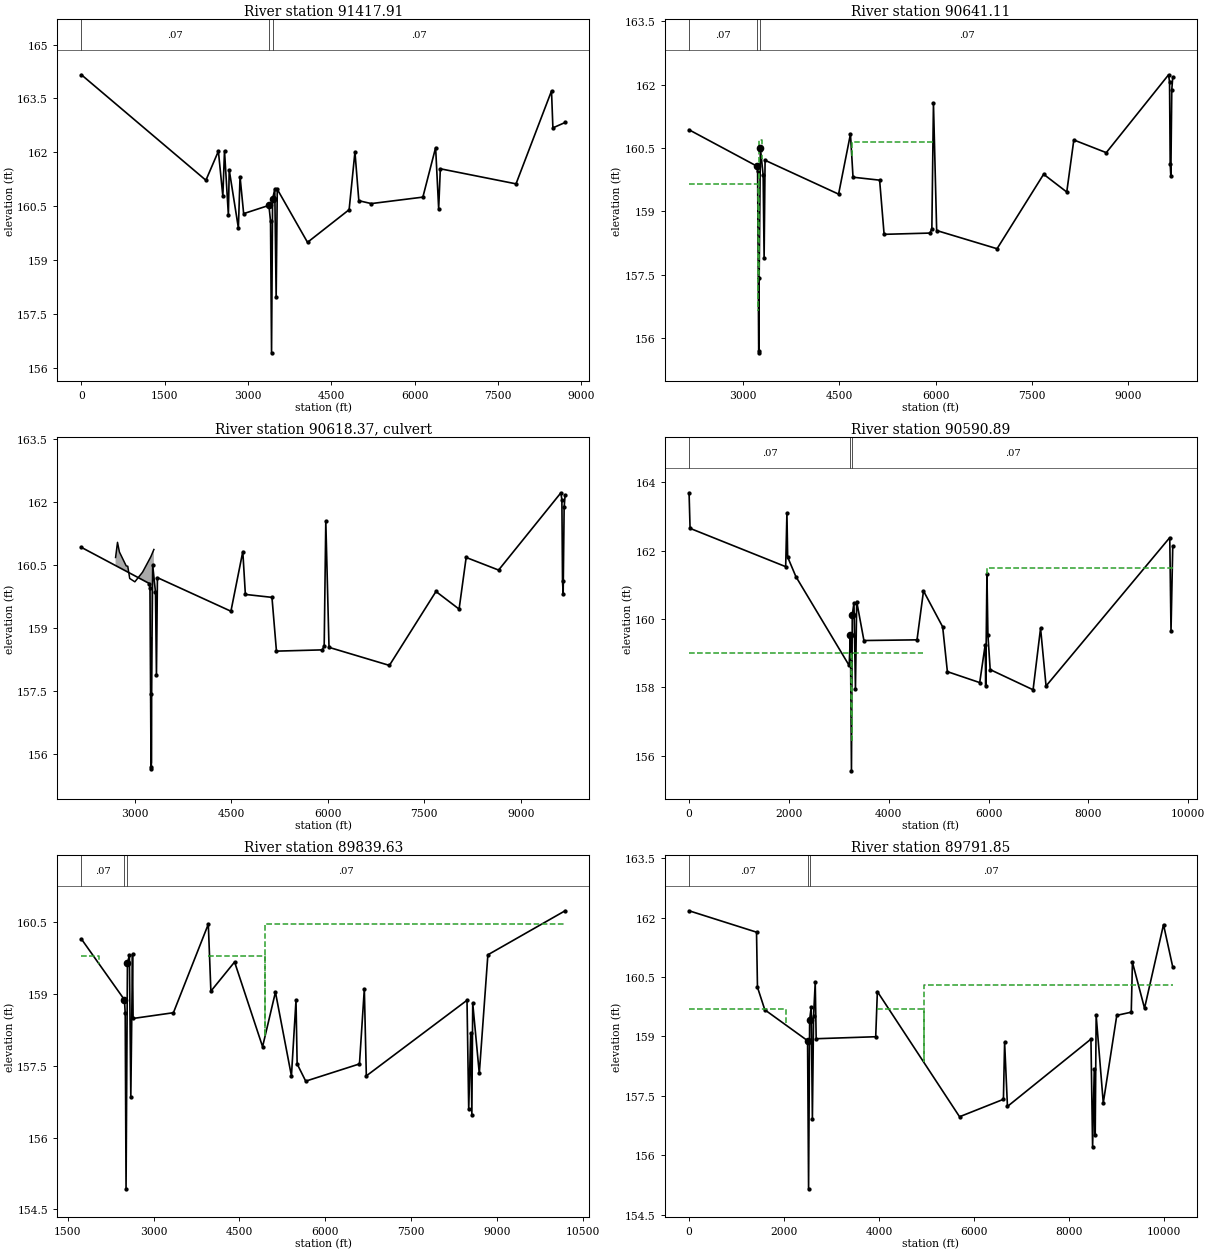
Type RM Length L Ch R = 1 ,91417.91,821.73,776.81,797.44
XS GIS Cut Line= 6
2973079.0192460313882690.57894862973086.0720534513880728.8440269
2973139.1398606913879209.87003082973157.7051122813877831.1972632
2972535.4973671913876568.61907972970697.9508454513874961.5957189
#Sta/Elev= 30
       0  164.16 2241.62  161.22 2466.51  162.03 2546.47  160.78 2576.45  162.04
 2646.42  160.25 2661.41  161.51 2826.33  159.89 2856.31  161.32 2921.28  160.29
 3376.05  160.52 3405.17  160.08 3423.66  156.41 3442.12   160.7 3481.64  160.97
 3506.62  157.96 3526.61  160.97 4071.14  159.49 4820.49   160.4 4925.34  162.01
 4995.22  160.65 5219.84  160.57 6148.26  160.75 6377.88  162.13  6432.8  160.43
 6462.75  161.54 7825.61  161.12 8464.61  163.71 8489.57  162.68 8709.22  162.83
#Mann= 3 ,-1 , 0
       0     .07       0 3376.05     .04       0 3442.12     .07       0
#XS Ineff= 5 ,-1
       0 2856.31  161.32 2856.31 3376.05  160.52 3462.52 4875.43  160.52
 4875.43 6307.99  161.15 6307.99 8709.22   161.5
Permanent Ineff=
       F       F       F       F       F
Bank Sta=3376.05,3442.12
XS Rating Curve= 0 ,0
Exp/Cntr=0.5,0.3

Type RM Length L Ch R = 1 ,90641.11,50.38,50.22,51.48
BEGIN DESCRIPTION:
Upstream Section - DRIVEWAY #1
END DESCRIPTION:
Node Name=AY
XS GIS Cut Line= 6
 2973885.230045113880380.42326322973898.78368261 13879974.145077
2973912.2058998613879295.30850822973912.8997961113879263.3410524
2973966.6326282813876579.52719442971392.3073963713873890.5522574
#Sta/Elev= 30
    2166  160.93 3222.24  160.07 3232.24  159.96 3249.04  155.71 3253.89  155.66
 3256.29  157.44 3275.27   160.5  3318.4  159.86 3333.38  157.89 3348.36  160.21
 4491.93  159.41 4676.69  160.83 4716.57  159.81 5130.32  159.74  5200.1  158.46
 5912.94  158.49 5942.85  158.59 5967.77  161.56 6017.74  158.55 6957.15  158.12
 7681.69  159.88 8041.46  159.46  8151.4  160.69  8656.1  160.39 9625.53  162.23
 9640.52  162.06 9650.51  160.13 9660.51  159.83  9675.5  161.88 9690.49  162.17
#Mann= 3 ,-1 , 0
    2166     .07       0 3222.24     .04       0 3275.27     .07       0
#XS Ineff= 4 ,-1
    2166 3245.36  159.65 3256.56 3293.43   160.7 4696.63 5967.77  160.65
 5967.77 9690.49  161.56
Permanent Ineff=
       F       F       T       T
#Block Obstruct= 2 , 0
       0                 9625.53       0  162.23
Bank Sta=3222.24,3275.27
XS Rating Curve= 0 ,0
Exp/Cntr=0.5,0.3

Type RM Length L Ch R = 2 ,90618.37,,,
BEGIN DESCRIPTION:
DRIVEWAY #1
END DESCRIPTION:
Node Name=DRIVEWAY #1
Bridge Culvert--1,0,-1,-1, 0
Deck Dist Width WeirC Skew NumUp NumDn MinLoCord MaxHiCord MaxSubmerge Is_Ogee
21,14,2.6,0, 10, 10, , , 0.98, 0, 0,0,,
 2697.44 2727.43 2757.42 2862.38 2887.37 2917.36 2997.33 3117.28 3246.66 3293.43
  160.69  161.05  160.82  160.49  160.48  160.19  160.11  160.34  160.71  160.88
       0       0       0       0       0       0       0       0       0       0
 2697.44 2727.43 2757.42 2862.38 2887.37 2917.36 2997.33 3117.28 3246.66 3293.43
  160.69  161.05  160.82  160.49  160.48  160.19  160.11  160.34  160.71  160.88
       0       0       0       0       0       0       0       0       0       0
BR Coef=-1 , 0 , 0 ,, 0 ,,,0.8,-1,,0,
WSPro=,,,, 1 ,,,, 0 ,,,, 0 ,,,,-1 ,-1 ,-1 , 0 , 0 , 0 , 0 , 0
Culvert=1,3,,23.8,0.013,0.5,1,1,3,155.61,3246.86,156.43,3246.86,Culvert #1  , 0 ,18.5
Culvert Bottom n=0.013
Culvert=1,3,,23.8,0.013,0.5,1,1,3,155.62,3250.96,156.04,3250.96,Culvert #2  , 0 ,18.5
Culvert Bottom n=0.013
Culvert=1,3,,23.8,0.013,0.5,1,1,3,155.79,3255.06,156.19,3255.06,Culvert #3  , 0 ,18.5
Culvert Bottom n=0.013
BC Design=,, 0 ,, 0 ,,,,,,
BC Use User HTab Curves=0
BC User HTab FreeFlow(D)= 0

Type RM Length L Ch R = 1 ,90590.89,811.68,751.27,788.88
BEGIN DESCRIPTION:
Downstream Section - DRIVEWAY #1
END DESCRIPTION:
XS GIS Cut Line= 6
2973934.9679934413882548.94832632973930.6484482713880523.7177968
2973948.8954590313879976.75301142973962.3176762813879297.9164426
2974016.7444046913876582.13512882971442.4191727813873893.1601918
#Sta/Elev= 30
       0  163.69   19.95  162.65 1935.44  161.53 1960.39   163.1 1975.35  161.81
 2139.66  161.24 3207.25  158.64 3232.24  159.53 3253.41  155.56 3269.74  160.12
 3303.42  160.47 3333.38  157.96 3358.35  160.51 3503.17  159.37 4566.83  159.39
 4696.63  160.82 5080.47  159.77 5175.18  158.46 5823.21  158.14 5932.88  159.25
 5942.85  158.04 5967.77  161.31 5987.76  159.52 6032.73  158.52 6892.19  157.93
 7042.09  159.73 7152.03  158.04 9630.53  162.38 9655.51  159.64 9690.49  162.12
#Mann= 3 ,-1 , 0
       0     .07       0 3232.24     .04       0 3269.74     .07       0
#XS Ineff= 4 ,-1
       0 3245.36     159 3256.56 4696.63     159 4696.63 5967.77   160.6
 5967.77 9690.49   161.5
Permanent Ineff=
       F       F       T       F
#Block Obstruct= 2 , 0
       0                 9630.53       0  162.38
Bank Sta=3232.24,3269.74
XS Rating Curve= 0 ,0
Exp/Cntr=0.5,0.3

Type RM Length L Ch R = 1 ,89839.63,55.03,47.77,47.63
Node Name=AX
XS GIS Cut Line= 6
2974685.0791871713880104.47260282974710.8585020313879362.3569305
2974715.2872989513879242.22331252974765.9981555313877899.3483736
2974836.8671082713876029.66805792972029.3051381113872679.4237741
#Sta/Elev= 30
 1739.67  160.15 2491.42  158.88 2504.68   158.6 2519.37  154.93 2543.53  159.65
  2577.9  159.81 2602.45  156.84 2632.42  159.83 2642.41  158.49 3346.79  158.61
 3956.24  160.46 4001.15  159.06 4415.26  159.67 4904.21   157.9 5128.72  159.04
 5408.12  157.29 5487.95  158.87 5507.91  157.54 5657.58  157.18 6596.55  157.54
 6681.48  159.11 6716.45  157.29 8474.89  158.87 8504.86  156.59 8539.83  158.19
 8559.81  156.48  8574.8  158.81 8689.69  157.34 8839.55  159.8210188.33  160.74
#Mann= 3 ,-1 , 0
 1739.67     .07       0 2491.42     .04       0 2543.53     .07       0
#XS Ineff= 3 ,-1
       0 2043.67   159.8 3956.24    4950   159.8    495010188.33  160.46
Permanent Ineff=
       F       T       F
Bank Sta=2491.42,2543.53
XS Rating Curve= 0 ,0
Exp/Cntr=0.3,0.1

Type RM Length L Ch R = 1 ,89791.85,57.85,47.12,47.08
XS GIS Cut Line= 6
2974671.7683571113881841.27782572974713.4293630313880660.5016439
2974758.5860968513879360.56329892974813.72575036 13877897.554742
2974884.5947031113876027.87442632972077.0327329513872677.6301425
#Sta/Elev= 30
       0  162.17 1420.72  161.63 1440.66  160.24 1595.15  159.67 2496.02  158.89
 2517.35  155.15  2539.8  159.42 2572.99  159.74 2597.54  156.92 2622.43  159.51
  2657.4  160.36 2677.38  158.94 3931.28  158.99 3966.22  160.13  5697.5  156.97
 6621.53  157.41 6646.51  158.85 6706.46  157.23  8464.9  158.93 8499.86   156.2
 8534.83  158.17 8554.81  156.51  8574.8  159.53 8724.66  157.32  9009.4  159.53
 9314.12  159.61  9339.1  160.87 9593.87  159.71  9993.5  161.8210188.33  160.75
#Mann= 3 ,-1 , 0
       0     .07       0 2496.02     .04       0  2539.8     .07       0
#XS Ineff= 3 ,-1
       0 2038.69   159.7 3966.22 4944.12   159.7 4944.1210188.33   160.3
Permanent Ineff=
       F       T       F
Bank Sta=2496.02,2539.8
XS Rating Curve= 0 ,0
Exp/Cntr=0.3,0.1

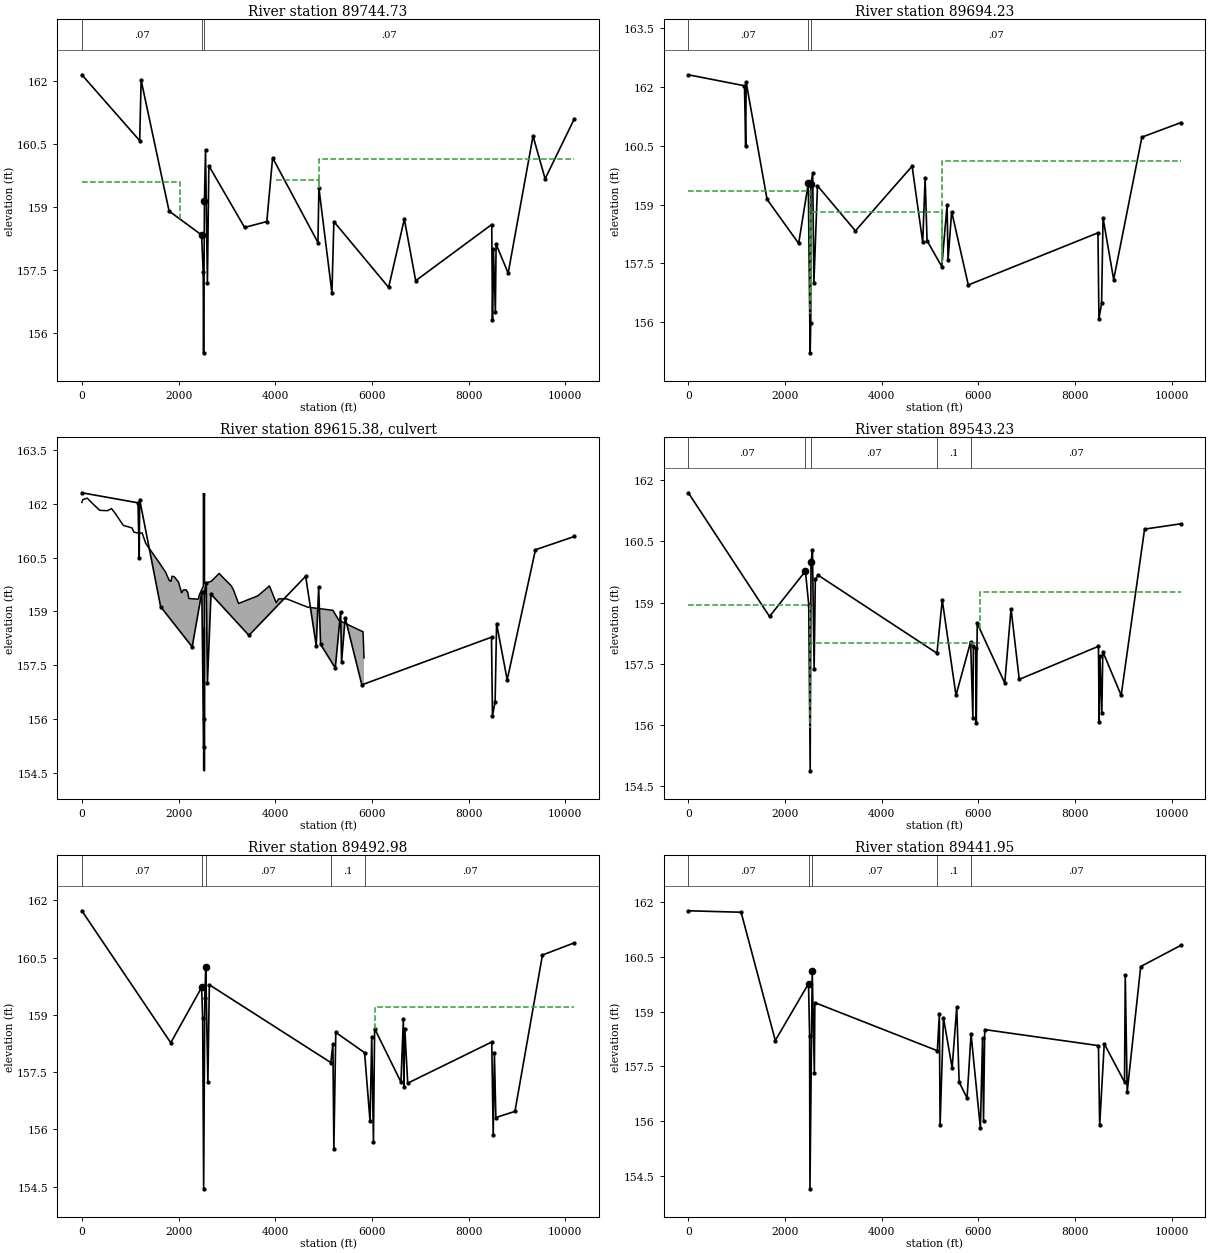
Type RM Length L Ch R = 1 ,89744.73,60.84,50.49,49.88
XS GIS Cut Line= 6
2974718.80435228 13881842.594096 2974760.465358213880661.8179143
2974805.6220920213879361.87956932974860.7617455313877898.8710123
2974931.6306982813876029.1906966 2972124.068728113872678.9464128
#Sta/Elev= 30
       0  162.15 1196.46  160.58 1226.36  162.02 1804.46   158.9 2477.25  158.33
 2510.38  157.45  2518.5  155.52 2536.38  159.15 2558.26  160.36 2597.54  157.18
 2627.43  159.98 3366.77  158.51 3826.37  158.65 3946.26  160.17 4884.25  158.15
  4904.2  159.45 5173.62  156.95 5213.54  158.65 6346.77  157.08 6671.49  158.71
 6906.28  157.24 8479.88  158.58 8494.87  156.31 8514.85  157.99 8554.81  156.49
  8569.8  158.11 8819.57  157.42  9334.1  160.69 9583.88  159.6710188.33   161.1
#Mann= 3 , 0 , 0
       0     .07       0 2477.25     .04       0 2536.38     .07       0
#XS Ineff= 3 ,-1
       0 2038.69   159.6 4026.09  4904.2  159.65  4904.210188.33  160.15
Permanent Ineff=
       F       T       F
Bank Sta=2477.25,2536.38
XS Rating Curve= 0 ,0
Exp/Cntr=0.5,0.3

Type RM Length L Ch R = 1 ,89694.23,169.1,151,150.5
BEGIN DESCRIPTION:
Upstream Section - KATY HOCKLEY RD
END DESCRIPTION:
XS GIS Cut Line= 6
2974768.6897511913881842.42382082974810.35075711 13880661.647639
2974855.50749095 13879361.7092942974910.6471444413877898.7007371
2974981.5160971913876029.02042142972173.9541270313872678.7761376
#Sta/Elev= 30
       0  162.31 1161.57  162.03 1186.49  160.49 1196.46  162.12 1630.03  159.13
 2282.89  158.01 2482.23  159.54 2520.22  155.22 2533.13  155.99 2535.74  159.53
 2572.99   159.8 2597.54     157 2672.39  159.48  3456.7  158.33  4629.8  159.98
 4849.32  158.04 4899.22  159.67 4939.13  158.08 5243.47  157.42 5353.24  158.99
  5373.2  157.59 5448.03  158.82 5792.29  156.95 8474.89  158.28 8494.87  156.09
 8549.82  156.48 8579.79  158.66 8799.59  157.09 9384.06  160.7210188.33  161.09
#Mann= 3 ,-1 , 0
       0     .07       0 2482.23     .04       0 2535.74     .07       0
#XS Ineff= 3 ,-1
       0  2511.4  159.34 2533.55    5250   158.8    525010188.33   160.1
Permanent Ineff=
       F       F       F
#Block Obstruct= 2 , 0
       0                10143.37       0  161.55
Bank Sta=2482.23,2535.74
XS Rating Curve= 0 ,0
Exp/Cntr=0.5,0.3

Type RM Length L Ch R = 2 ,89615.38,,,
BEGIN DESCRIPTION:
KATY HOCKLEY RD
END DESCRIPTION:
Node Name=KATY HOCKLEY RD
Bridge Culvert--1,0,-1,-1, 0
Deck Dist Width WeirC Skew NumUp NumDn MinLoCord MaxHiCord MaxSubmerge Is_Ogee
60,41.2,2.6,0, 52, 52, , , 0.98, 0, 0,0,,
       0   19.94  109.68  244.28  368.91  533.42  613.19  697.94  857.47 1036.94
 1076.82 1201.44  1246.3 1321.05 1585.18 1729.71 1809.44 1844.33 1864.26 1909.12
 1998.82 2063.61 2103.48  2158.3 2193.18 2213.12  2402.5 2417.45 2427.41 2513.64
 2513.74 2530.21 2538.21 2538.31 2677.38 2842.24  2887.2 3087.02 3136.98 3241.88
 3426.72 3636.54 3881.32 3911.29  4021.1    4071 4235.64 4664.72 5193.58 5318.31
 5817.24 5837.22
  162.04  162.12  162.16  161.98  161.82  161.81  161.87  161.72   161.4  161.33
  161.21  161.18  161.19   160.9  160.39   160.1  159.86  159.84  159.98  159.97
  159.82  159.52   159.6   159.6  159.52  159.36  159.34  159.37  159.45  159.71
  162.29  162.18  162.28  159.78  159.84  160.06  159.99  159.72   159.6  159.22
  159.32  159.43  159.71  159.61  159.24  159.35  159.35  159.12  159.03  158.75
  158.43   157.7
       0       0       0       0       0       0       0       0       0       0
       0       0       0       0       0       0       0       0       0       0
       0       0       0       0       0       0       0       0       0       0
       0       0       0       0       0       0       0       0       0       0
       0       0       0       0       0       0       0       0       0       0
       0       0
       0   19.94  109.68  244.28  368.91  533.42  613.19  697.94  857.47 1036.94
 1076.82 1201.44  1246.3 1321.05 1585.18 1729.71 1809.44 1844.33 1864.26 1909.12
 1998.82 2063.61 2103.48  2158.3 2193.18 2213.12  2402.5 2417.45 2427.41 2513.64
 2513.74 2530.21 2538.21 2538.31 2677.38 2842.24  2887.2 3087.02 3136.98 3241.88
 3426.72 3636.54 3881.32 3911.29  4021.1    4071 4235.64 4664.72 5193.58 5318.31
 5817.24 5837.22
  162.04  162.12  162.16  161.98  161.82  161.81  161.87  161.72   161.4  161.33
  161.21  161.18  161.19   160.9  160.39   160.1  159.86  159.84  159.98  159.97
  159.82  159.52   159.6   159.6  159.52  159.36  159.34  159.37  159.45  159.71
  162.29  162.18  162.28  159.78  159.84  160.06  159.99  159.72   159.6  159.22
  159.32  159.43  159.71  159.61  159.24  159.35  159.35  159.12  159.03  158.75
  158.43   157.7
       0       0       0       0       0       0       0       0       0       0
       0       0       0       0       0       0       0       0       0       0
       0       0       0       0       0       0       0       0       0       0
       0       0       0       0       0       0       0       0       0       0
       0       0       0       0       0       0       0       0       0       0
       0       0
BR Coef=-1 , 0 , 0 ,, 0 ,,,0.8,-1,,0,
WSPro=,,,, 1 ,,,, 0 ,,,, 0 ,,,,-1 ,-1 ,-1 , 0 , 0 , 0 , 0 , 0
Culvert=2,4,8,41.2,0.015,0.5,1,10,1,154.56,2518.4,154.41,2518.4,Culvert #1  , 0 ,60
Culvert Bottom n=0.015
Culvert=2,4,8,41.2,0.015,0.5,1,10,1,154.55,2527.55,154.42,2527.55,Culvert #2  , 0 ,60
Culvert Bottom n=0.015
BC Design=,, 0 ,, 0 ,,,,,,
BC Use User HTab Curves=0
BC User HTab FreeFlow(D)= 0

Type RM Length L Ch R = 1 ,89543.23,50.06,50.26,49.83
BEGIN DESCRIPTION:
Downstream Section - KATY HOCKLEY RD
END DESCRIPTION:
XS GIS Cut Line= 6
2974918.8938471113881850.11835922974960.5548530213880669.3421774
2975005.7115868613879369.40383242975060.8512403713877906.3952755
 2975131.720193113876036.71495982972324.15822294 13872686.470676
#Sta/Elev= 30
       0  161.69 1679.87  158.66 2422.43  159.77 2491.42  158.95    2521  154.88
 2538.62     160 2568.08  160.28 2602.45  157.38 2627.43  159.57 2687.37  159.67
 5144.25  157.76 5253.45  159.06 5537.84  156.73 5840.46  158.04 5887.18  156.17
 5897.17  157.94 5942.13  157.88 5957.12  156.04  5977.1  158.49  6546.6  157.03
 6676.48  158.85 6846.33  157.12 8484.88  157.93 8499.86  156.08 8514.85   157.7
 8554.81  156.29  8574.8   157.8 8954.45  156.73 9439.01   160.810188.33  160.93
#Mann= 5 ,-1 , 0
       0     .07       0 2422.43     .04       0 2538.62     .07       0
 5144.25      .1       0 5840.46     .07       0
#XS Ineff= 3 ,-1
       0  2513.4  158.93 2531.55 6027.05     158 6027.0510188.33  159.25
Permanent Ineff=
       F       F       T
Bank Sta=2422.43,2538.62
XS Rating Curve= 0 ,0
Exp/Cntr=0.5,0.3

Type RM Length L Ch R = 1 ,89492.98,53.22,51.02,51.04
XS GIS Cut Line= 6
2974968.40063787 13881858.5586312975010.0616437813880677.7824493
2975055.2183776113879377.84410432975110.3580311113877914.8355474
2975181.2269838613876045.1552316 2972373.665013713872694.9109479
#Sta/Elev= 30
       0  161.73 1839.35  158.27 2477.25  159.72 2499.43  158.93 2519.86  154.44
 2543.53  159.44 2563.17  160.26 2607.44  157.23 2637.42  159.79 5151.17  157.75
 5193.58  158.23 5213.54  155.49 5253.45  158.54    5849  158.01 5962.11  156.21
 5997.08  158.43 6032.05  155.67 6057.03  158.64 6601.55  157.24  6651.5  158.88
 6661.49  157.12 6681.48  158.63 6741.42  157.21 8479.88  158.29 8509.86  155.84
 8534.83  157.99 8564.81  156.31 8959.45  156.47 9528.93  160.5710188.33  160.89
#Mann= 5 ,-1 , 0
       0     .07       0 2477.25     .04       0 2563.17     .07       0
 5151.17      .1       0    5849     .07       0
#XS Ineff= 3 ,-1
       0 2382.82  158.93 2637.42 6057.03     158 6057.0310188.33   159.2
Permanent Ineff=
       F       F       T
Bank Sta=2477.25,2563.17
XS Rating Curve= 0 ,0
Exp/Cntr=0.3,0.1

Type RM Length L Ch R = 1 ,89441.95,46.28,43.68,43.7
XS GIS Cut Line= 6
2975019.3637905313881860.69412542975061.0247964413880679.9179437
2975106.1815302813879379.97959872975161.3211837713877916.9710418
2975232.19013652 13876047.2907262972424.6281663613872697.0464423
#Sta/Elev= 30
       0  161.77 1091.77  161.73 1799.48  158.21 2486.83  159.77 2509.06  158.34
 2516.31  154.14 2563.17  160.11 2607.44  157.31 2617.44  159.25 5151.74  157.93
 5193.58  158.93 5208.55  155.88  5278.4  158.83 5458.01  157.46 5552.81  159.12
  5602.7  157.07 5767.35  156.63 5848.93  158.39 6042.04  155.81    6087  158.28
 6106.98     156 6131.96  158.51 8484.88  158.07 8509.86  155.88 8604.77  158.12
 9024.39  157.07 9039.37  160.01 9079.34   156.8 9359.08  160.2410188.33  160.82
#Mann= 5 ,-1 , 0
       0     .07       0 2486.83     .04       0 2563.17     .07       0
 5151.74      .1       0 5848.93     .07       0
#XS Ineff= 2 ,-1
       0 2088.53  158.85 5552.8110188.33  159.12
Permanent Ineff=
       F       T
Bank Sta=2486.83,2563.17
XS Rating Curve= 0 ,0
Exp/Cntr=0.3,0.1

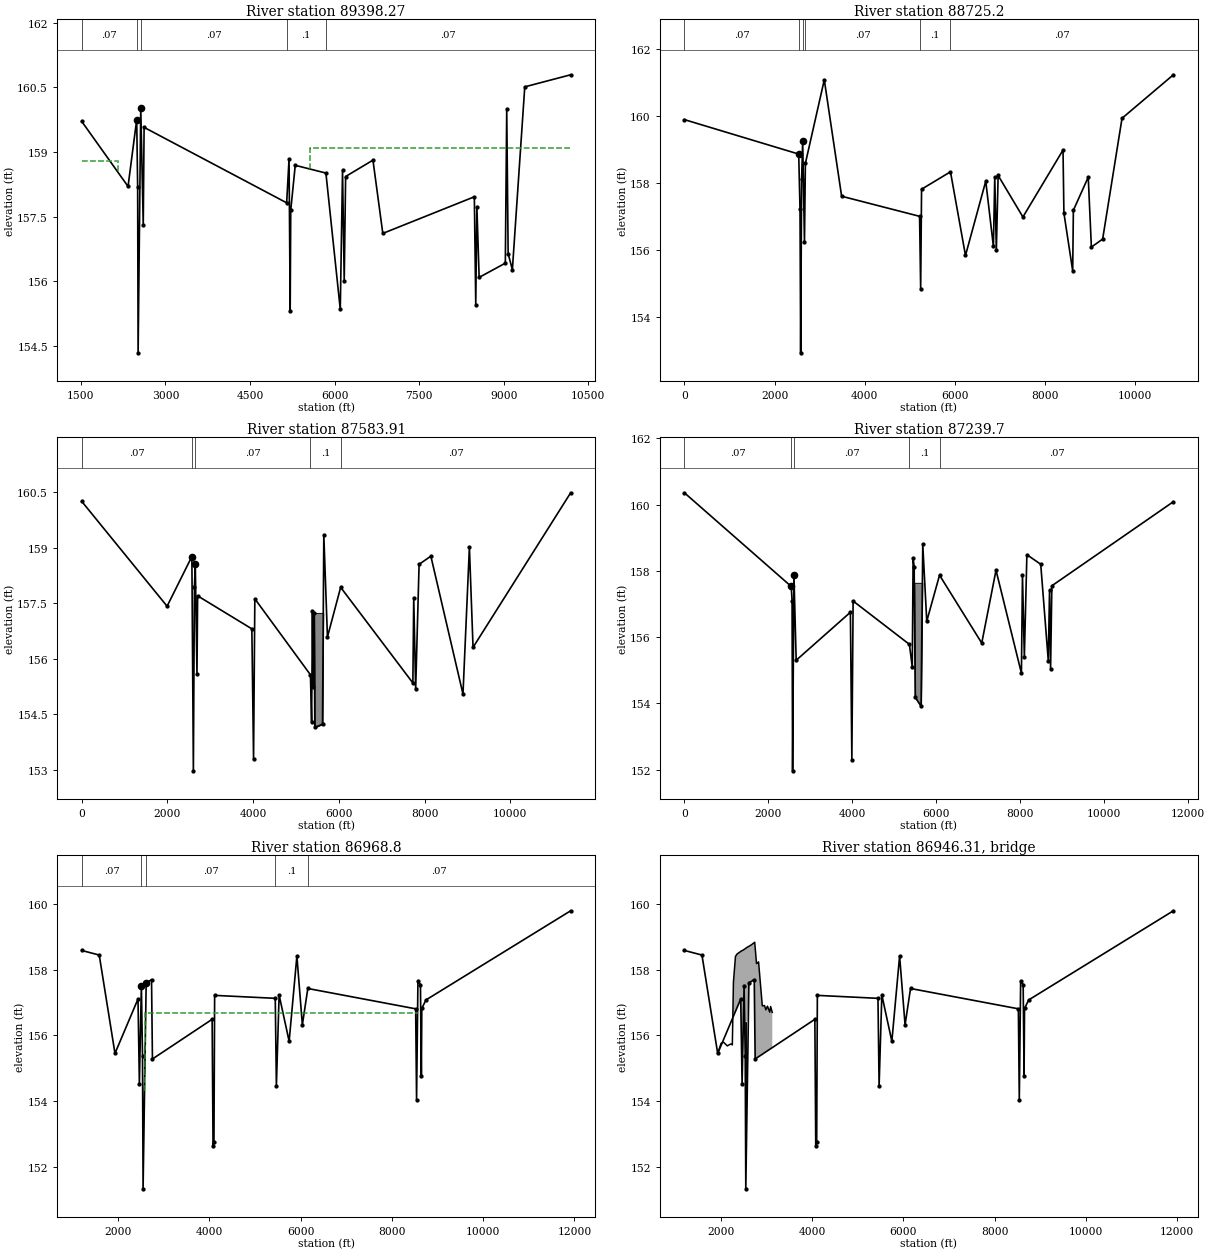
Type RM Length L Ch R = 1 ,89398.27,703.01,673.08,573.9
Node Name=AW
XS GIS Cut Line= 6
2975116.2917671813880346.75257492975149.8566397713879380.5120779
2975154.2854366913879260.37845992975204.99629328 13877917.503521
2975275.8652460313876047.82320532972468.3032758513872697.5789215
#Sta/Elev= 30
 1515.41  159.71 2337.71   158.2 2491.42  159.75 2508.22  158.18 2516.24  154.34
 2563.17  160.02 2607.44  157.31 2622.43  159.57 5150.93  157.82 5193.58  158.84
 5213.54  155.31 5223.52  157.65 5303.35  158.69 5847.11  158.51 6101.99  155.35
 6141.95  158.57 6171.93  156.01  6196.9  158.43 6681.48  158.81 6856.32  157.11
 8479.88  157.96 8504.86  155.46 8524.84  157.73 8564.81  156.09 9029.38  156.42
 9054.36     160 9079.34  156.64 9154.27  156.27 9374.07  160.5110188.33  160.79
#Mann= 5 ,-1 , 0
 1515.41     .07       0 2491.42     .04       0 2563.17     .07       0
 5150.93      .1       0 5847.11     .07       0
#XS Ineff= 2 ,-1
 1515.41 2163.28   158.8  5557.810188.33   159.1
Permanent Ineff=
       F       T
Bank Sta=2491.42,2563.17
XS Rating Curve= 0 ,0
Exp/Cntr=0.3,0.1

Type RM Length L Ch R = 1 ,88725.2 ,1153.65,1141.28,881.85
XS GIS Cut Line= 6
 2975775.132620213881945.38358862975759.1536495213880363.8903605
2975820.95995636 13879405.1698372975825.8900646113879302.2901215
2975722.9115960313876050.02005132972557.7673357713872238.2343678
#Sta/Elev= 30
       0  159.89  2537.3  158.86  2566.3  157.21 2580.56  152.92 2602.27  158.11
 2625.66  159.25 2665.27  156.22 2685.27  158.58 3105.13  161.08    3490   157.6
 5220.08     157 5244.38  154.82 5264.37  157.81 5906.05  158.33 6239.11  155.83
 6689.06  158.05 6859.05   156.1 6889.04  158.18 6924.04  155.98 6964.04  158.22
 7513.98  156.98 8403.91  158.98 8423.91   157.1  8618.9  155.37  8633.9  157.18
 8963.89  158.17 9033.89  156.08 9283.88  156.32 9713.87  159.9310853.84  161.23
#Mann= 6 ,-1 , 0
       0     .07       0  2537.3     .04       0 2625.66     .05       0
 2685.27     .07       0 5220.08      .1       0 5906.05     .07       0
#XS Ineff= 3 ,-1
       0  2537.3   158.7 3105.13 6964.04   157.9 6964.0410853.84  158.22
Permanent Ineff=
       F       T       T
Bank Sta=2537.3,2625.66
XS Rating Curve= 0 ,0
Exp/Cntr=0.3,0.1

Type RM Length L Ch R = 1 ,87583.91,343.88,344.22,208
XS GIS Cut Line= 6
2976647.3700489413881994.38545912976923.0617547813879829.2972696
2976966.2700016913879342.95014522976984.2624197813879058.1912003
 2976227.263605713876068.90059092972736.8211115313871987.3086885
#Sta/Elev= 30
       0  160.25 1992.78  157.42 2571.19  158.76 2606.26  152.98 2630.97  157.93
  2650.9  158.56 2690.51  155.58 2705.27   157.7 3970.72  156.81 4010.71  153.31
 4040.69  157.62 5338.36  155.57 5365.08   154.3 5385.07  157.28 5400.06  155.25
 5425.05  157.24 5440.04  154.15 5619.96  154.24 5649.94  159.35  5734.9  156.59
 6042.96  157.93 7728.36  155.35 7748.34  157.65  7793.3  155.18 7873.24  158.55
 8148.01  158.77 8897.41  155.05 9047.29  159.01 9132.23  156.3111410.41  160.48
#Mann= 5 ,-1 , 0
       0     .07       0 2571.19     .04       0  2650.9     .07       0
 5338.36      .1       0 6042.96     .07       0
#XS Ineff= 3 ,-1
       0 2571.19  157.73 5649.94 7873.24  157.66 7873.2411410.41  158.55
Permanent Ineff=
       F       F       F
#Block Obstruct= 1 ,-1
 5425.05 5649.94  157.24
Bank Sta=2571.19,2650.9
XS Rating Curve= 0 ,0
Exp/Cntr=0.3,0.1

Type RM Length L Ch R = 1 ,87239.7 ,487.27,270.89,76.99
XS GIS Cut Line= 6
2977039.3869814413881984.58528182977185.8801267713880285.7100707
 2977302.729958713879498.81991222977268.0699230313878952.5398368
2976338.0950769513876071.20636062972919.1130697713871674.8086573
#Sta/Elev= 30
       0  160.36 2544.75  157.53 2564.32   157.1 2576.81  151.96 2608.37  157.89
  2662.2   155.3 3953.22  156.75  3988.2   152.3 4018.17  157.09 5359.24  155.78
 5427.11  155.09 5447.09  158.39 5472.07  158.13 5497.06  154.18 5636.95  153.91
 5676.92   158.8 5771.85  156.48  6076.3  157.87 7081.52  155.82 7421.48  158.02
 8026.42  154.91 8051.42  157.87 8096.41   155.4  8156.4  158.49 8486.34   158.2
 8666.31  155.29  8696.3  157.41  8721.3  155.05 8751.29  157.5511645.73  160.09
#Mann= 5 ,-1 , 0
       0     .07       0 2544.75     .04       0 2608.37     .07       0
 5359.24      .1       0  6076.3     .07       0
#XS Ineff= 3 ,-1
       0 2544.75  157.53 5676.92  8156.4  157.53  8156.411645.73  158.49
Permanent Ineff=
       F       F       F
#Block Obstruct= 1 ,-1
 5462.08  5706.9  157.64
Bank Sta=2544.75,2608.37
XS Rating Curve= 0 ,0
Exp/Cntr=0.5,0.3

Type RM Length L Ch R = 1 ,86968.8 ,18.97,73.17,24.85
BEGIN DESCRIPTION:
Upstream Section - FREEMAN (FM 529)
END DESCRIPTION:
Node Name=AV
XS GIS Cut Line= 6
2977823.4060548313880688.51010952977634.1052801913879412.8561734
2977437.8100691113879403.10848942976473.8103566913876105.4940217
2975130.0240022813874034.87939652973199.9045029413871324.1220228
#Sta/Elev= 30
 1199.65  158.59 1584.53  158.45 1929.43  155.45 2434.29  157.11 2464.28  154.52
 2508.11  157.52 2532.89  155.37  2545.4  151.32 2613.26   157.6 2730.75   157.7
 2750.73  155.28 4059.07  156.49 4079.04  152.62 4099.02  152.75    4114  157.22
 5442.65  157.13  5467.3  154.46 5527.22  157.23 5746.95  155.82 5916.73  158.42
 6036.58  156.32 6156.15  157.43 8520.03  156.81 8540.02  154.04    8570  157.65
 8624.96  157.55 8644.95  154.77 8654.94  156.82 8744.88  157.0811917.62   159.8
#Mann= 5 ,-1 , 0
 1199.65     .07       0 2508.11     .04       0 2613.26     .07       0
 5442.65      .1       0 6156.15     .07       0
#XS Ineff= 4 ,-1
 1199.65 2508.11   157.2 2508.11 2524.03  155.45 2577.69    8570  156.69
    857011917.62  157.65
Permanent Ineff=
       F       F       F       F
Bank Sta=2508.11,2613.26
XS Rating Curve= 0 ,0
Exp/Cntr=0.5,0.3

Type RM Length L Ch R = 3 ,86946.31,,,
BEGIN DESCRIPTION:
FREEMAN (FM 529)
END DESCRIPTION:
Node Name=FREEMAN (FM 529)
Bridge Culvert--1,0,-1,-1, 0
Deck Dist Width WeirC Skew NumUp NumDn MinLoCord MaxHiCord MaxSubmerge Is_Ogee
7,35,2.6,0, 36, 35, , , 0.98, 0, 0,0,,
 1929.43 2004.41 2059.39 2139.37 2219.35  2250.5 2274.33 2319.32 2339.31 2349.31
 2359.31  2384.3 2404.29 2414.29 2429.29 2439.28 2444.28 2454.28 2474.27  2517.7
 2577.69  2618.1 2676.14 2710.78 2725.76 2740.74 2780.69 2790.68 2825.63  2907.3
 2955.47 2985.43 3020.39 3070.32  3090.3 3125.25
  155.45  155.76  155.79  155.68  155.74  155.71  157.62  158.41  158.45  158.47
  158.49  158.51  158.53  158.54  158.56  158.56  158.57  158.58  158.59  158.63
  158.69  158.72  158.77  158.81  158.82  158.84  158.19   158.2  158.24   156.9
  156.91  156.78  156.89  156.71  156.88   156.7
       0       0       0       0       0       0       0       0       0       0
       0       0       0       0       0       0       0       0       0  156.38
  156.44       0       0       0       0       0       0       0       0       0
       0       0       0       0       0       0
 1789.47 2004.41 2059.39 2219.35  2250.5 2274.33 2319.32 2339.31 2349.31 2359.31
  2384.3 2404.29 2414.29 2429.29 2439.28 2444.28 2454.28 2474.27  2517.7 2577.69
  2618.1 2676.14 2710.78 2725.76 2740.74 2780.69 2790.68 2825.63  2907.3 2955.47
 2985.43 3020.39 3070.32  3090.3 3125.25
  155.47  155.76  155.79  155.74  155.71  157.62  158.41  158.45  158.47  158.49
  158.51  158.53  158.54  158.56  158.56  158.57  158.58  158.59  158.63  158.69
  158.72  158.77  158.81  158.82  158.84  158.19   158.2  158.24   156.9  156.91
  156.78  156.89  156.71  156.88   156.7
       0       0       0       0       0       0       0       0       0       0
       0       0       0       0       0       0       0       0  156.35  156.41
       0       0       0       0       0       0       0       0       0       0
       0       0       0       0       0
Pier Skew, UpSta & Num, DnSta & Num=  ,2538, 2 ,2538, 2 , 0 , 0 , 0 ,,
     2.2     2.2
     150   157.5
     2.2     2.2
     150   157.5
Pier Skew, UpSta & Num, DnSta & Num=  ,2557.5, 2 ,2557.5, 2 , 0 , 0 , 0 ,,
     2.2     2.2
     150   157.5
     2.2     2.2
     150   157.5
Abutment Skew #Up #Dn= , 2 , 2
  2517.5  2518.8
  156.38  154.77
  2517.5  2518.8
  156.35  154.74
Abutment Skew #Up #Dn= , 3 , 3
  2576.5 2577.89 2578.89
  154.57  156.44  156.44
  2576.5 2577.89 2578.89
  154.54  156.41  156.41
BR Coef=-1 , 1 , 1 ,0.9, 0 ,,,0.8,-1,1.2,0,
WSPro=,,,, 1 ,,,, 0 ,,,, 0 ,,,,-1 ,-1 ,-1 , 0 , 0 , 0 , 0 , 0
BC Design=,, 0 ,, 0 ,,,,,,
BC Use User HTab Curves=0
BC User HTab FreeFlow(D)= 0

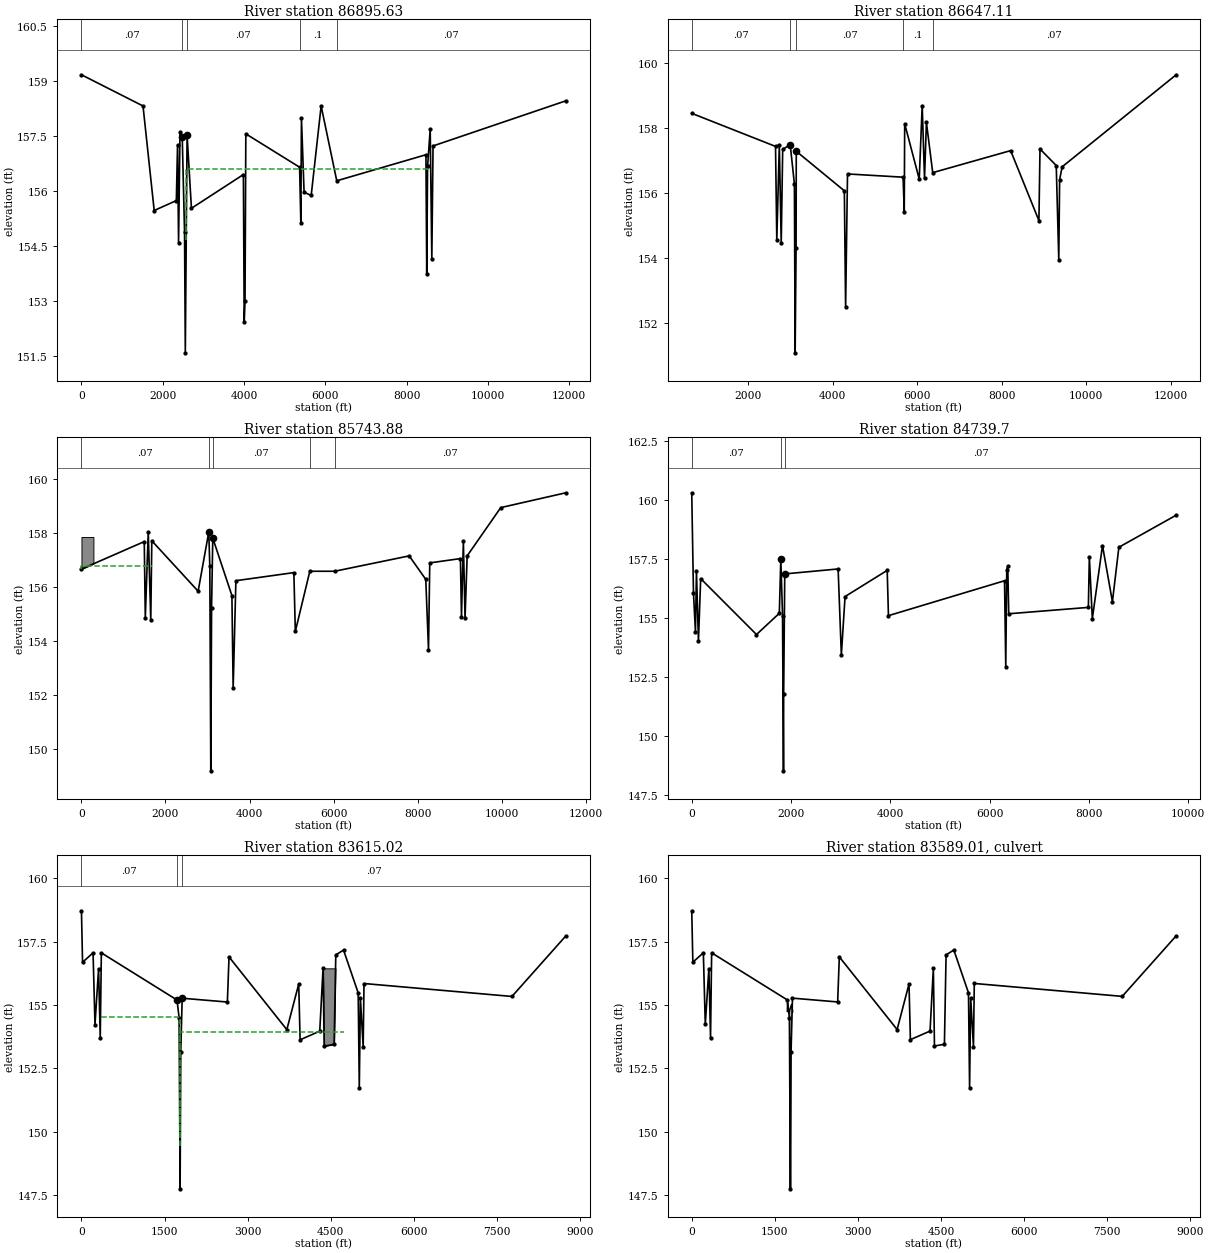
Type RM Length L Ch R = 1 ,86895.63,654.33,248.52,270.24
BEGIN DESCRIPTION:
Downstream Section - FREEMAN (FM 529)
END DESCRIPTION:
XS GIS Cut Line= 6
2978004.4277022813881803.49345242977639.0330918613879341.1840726
2977442.7378807813879331.43638872976478.7381683613876033.8219209
2975134.9518139413873963.20729582973204.83231461 13871252.449922
#Sta/Elev= 30
       0  159.17 1514.56  158.32 1789.47  155.47 2334.31  155.74 2364.31  157.26
  2389.3  154.59 2424.29  157.61 2479.27  157.48 2536.38  154.88 2555.22  151.59
 2598.75  157.53 2705.78  155.53 3984.16  156.45 4004.14  152.44 4024.11     153
 4044.09  157.56 5367.14  156.65 5397.39  155.12 5412.37  157.99 5477.29  155.97
 5652.07  155.88 5896.76  158.32 6281.38  156.28 8475.06  156.99 8495.04  153.74
 8515.03  156.67    8580  157.68 8619.97  154.15 8649.95  157.2311917.63  158.46
#Mann= 5 ,-1 , 0
       0     .07       0 2479.27     .04       0 2598.75     .07       0
 5367.14      .1       0 6281.38     .07       0
#XS Ineff= 4 ,-1
       0 2444.28  157.15 2444.28 2517.54  155.45 2577.69    8580   156.6
    858011917.63  157.68
Permanent Ineff=
       F       F       F       F
Bank Sta=2479.27,2598.75
XS Rating Curve= 0 ,0
Exp/Cntr=0.5,0.3

Type RM Length L Ch R = 1 ,86647.11,1103.1,903.23,403.25
Node Name=AU
XS GIS Cut Line= 5
2979122.98202364 13881158.1997382977961.6515411113879302.9223381
 2977644.930061713879130.38003232976790.7221244413876080.6233365
2973574.3348564513871310.0452793
#Sta/Elev= 30
  659.63  158.46 2643.51  157.44  2673.5  154.55 2733.46  157.49 2778.44  154.45
 2813.42  157.35 2991.68  157.49 3090.49  156.28 3108.11  151.07 3130.08  154.31
 3134.96  157.29 4273.12  156.07 4303.09  152.47 4348.05  156.59 5663.73  156.49
 5691.86  155.42 5701.85  158.14 6046.55  156.43 6116.49   158.7 6171.44  156.45
  6216.4  158.18 6365.63  156.63 8210.81  157.31 8880.68  155.15 8905.68  157.36
  9290.6  156.85 9350.59  153.95 9370.59  156.41 9430.57  156.8112130.05  159.65
#Mann= 5 ,-1 , 0
  659.63     .07       0 2991.68     .04       0 3134.96     .07       0
 5663.73      .1       0 6365.63     .07       0
#XS Ineff= 3 ,-1
  659.63 2991.69  157.05 3149.78 8905.68   156.6 8905.6812130.05  157.36
Permanent Ineff=
       F       F       F
Bank Sta=2991.68,3134.96
XS Rating Curve= 0 ,0
Exp/Cntr=0.3,0.1

Type RM Length L Ch R = 1 ,85743.88,1006.48,1004.18,870.6
XS GIS Cut Line= 6
2980435.73583178 13880635.6988722978931.5469110313878956.1428479
2978232.2599237713878428.74003132978001.9831533613878260.1773764
2976934.1598296913876083.60758252973824.02595811 13871319.650575
#Sta/Elev= 30
       0  156.67 1494.77  157.69 1519.77  154.87 1589.76  158.04 1649.75  154.78
 1674.74  157.72 2777.19  155.85    3031  158.05 3054.93  156.77 3078.42  149.19
 3097.04  155.24 3125.55  157.82 3580.87  155.69 3610.86  152.26 3675.84  156.24
 5055.51  156.54  5090.5  154.36 5435.42  156.59  6025.3  156.59 7800.09  157.16
 8195.04  156.29 8260.03  153.68 8290.03   156.9  9019.9  157.06  9044.9   154.9
 9089.89   157.7 9129.88  154.85 9179.87  157.16 9979.73  158.9511529.46   159.5
#Mann= 5 ,-1 , 0
       0     .07       0    3031     .05       0 3125.55     .07       0
 5435.42      .1       0  6025.3     .07       0
#XS Ineff= 4 ,-1
       0 1674.74   156.8 3675.84 8290.03     156 8290.03 9399.83   156.9
 9399.8311529.46  157.37
Permanent Ineff=
       F       F       F       F
#Block Obstruct= 2 , 0
       0  284.96  157.86               0
Bank Sta=3031,3125.55
XS Rating Curve= 0 ,0
Exp/Cntr=0.3,0.1

Type RM Length L Ch R = 1 ,84739.7 ,896.03,1124.69,1190.05
Node Name=AT
XS GIS Cut Line= 6
2980341.7917939413878781.54805282978935.5600263613877716.2900127
2978828.5500697813877635.32987282978648.9178831113877489.3432881
2977744.2605716913876100.46155142974137.4374047813871342.9756596
#Sta/Elev= 30
       0   160.3   34.98  156.04   74.96  154.41   94.95  156.99  134.94  154.01
  179.91  156.66 1304.38  154.29 1764.16  155.19 1793.98  157.48 1828.78  155.09
 1848.08  148.51 1851.73  151.78  1873.5  156.86  2948.6  157.07  3013.5  153.42
 3088.39   155.9 3937.22  157.01  3962.2  155.09 6300.34  156.57 6325.32  152.93
  6345.3  157.04 6365.28  157.18 6385.27  155.17    7989  155.44 8008.98  157.58
 8068.93  154.96 8273.77  158.06 8473.61  155.68 8603.51  157.99 9757.61  159.35
#Mann= 3 ,-1 , 0
       0     .07       0 1793.98     .05       0  1873.5     .07       0
#XS Ineff= 2 ,-1
       0  179.91  156.66 6365.28 9757.61  157.18
Permanent Ineff=
       F       F
Bank Sta=1793.98,1873.5
XS Rating Curve= 0 ,0
Exp/Cntr=0.5,0.3

Type RM Length L Ch R = 1 ,83615.02,35.28,40.69,36
BEGIN DESCRIPTION:
Upstream Section - 72" CULVERT
END DESCRIPTION:
XS GIS Cut Line= 6
2980418.06001411 13878367.1207322979610.0124176113876863.6322692
2979477.0851900313876677.05160562979004.1806240213875780.7279389
2977751.8652152713874128.68695172975212.4352547813871402.9479806
#Sta/Elev= 30
       0  158.72   19.96  156.69  209.62  157.06  244.55  154.23  309.43  156.44
  339.38   153.7  359.34  157.06 1725.74   155.2 1763.48   154.5 1781.78  147.75
 1793.46  153.14 1819.01  155.27 2635.13  155.12 2665.09   156.9 3708.92  154.03
 3923.72  155.83  3948.7  153.63 4303.36  153.97  4363.3  156.45 4383.29  153.38
 4563.12  153.45 4593.09  156.98 4732.96  157.17 4997.71  155.48 5017.69  151.74
 5037.67  155.27 5087.61  153.35 5102.59  155.85 7774.32  155.34 8748.15  157.73
#Mann= 3 ,-1 , 0
       0     .07       0 1725.74     .05       0 1819.01     .07       0
#XS Ineff= 4 ,-1
       0  359.34  157.06  359.34 1777.23  154.54 1786.73 4732.96  153.95
 4732.96 8748.15  155.85
Permanent Ineff=
       F       F       F       F
#Block Obstruct= 1 ,-1
  4363.3 4593.09  156.45
Bank Sta=1725.74,1819.01
XS Rating Curve= 0 ,0
Exp/Cntr=0.5,0.3

Type RM Length L Ch R = 2 ,83589.01,,,
BEGIN DESCRIPTION:
72" CULVERT
END DESCRIPTION:
Node Name=72" CULVERT
Bridge Culvert--1,0,-1,-1, 0
Deck Dist Width WeirC Skew NumUp NumDn MinLoCord MaxHiCord MaxSubmerge Is_Ogee
4,30,2.6,0, 12, 14, , , 0.98, 0, 1,1,,
 1725.74 1730.46  1739.9 1754.05  1768.2 1772.92 1777.64 1782.35 1790.91 1795.19
 1804.36 1823.89
  154.75  155.08  154.76  154.68  154.81  154.84  154.86  154.89  154.94  154.97
  155.02  154.73
       0       0       0       0       0       0       0       0       0       0
       0       0
 1711.59 1725.74 1730.46  1739.9 1754.05  1768.2 1772.92 1777.64 1782.35 1790.91
 1795.19 1804.36 1823.89 1828.78
  155.23  154.75  155.08  154.76  154.78  154.86  154.89  154.91  154.94  154.99
  155.02     155  155.89  155.78
       0       0       0       0       0       0       0       0       0       0
       0       0       0       0
BR Coef=-1 , 0 , 0 ,, 0 ,,,0.8,-1,,0,
WSPro=,,,, 1 ,,,, 0 ,,,, 0 ,,,,-1 ,-1 ,-1 , 0 , 0 , 0 , 0 , 0
Culvert=1,6,,32,0.013,0.5,1,1,3,147.74,1781.98,148.06,1772.68,Culvert #1  , 0 ,3
Culvert Bottom n=0.013
BC Design=,, 0 ,, 0 ,,,,,,
BC Use User HTab Curves=0
BC User HTab FreeFlow(D)= 0