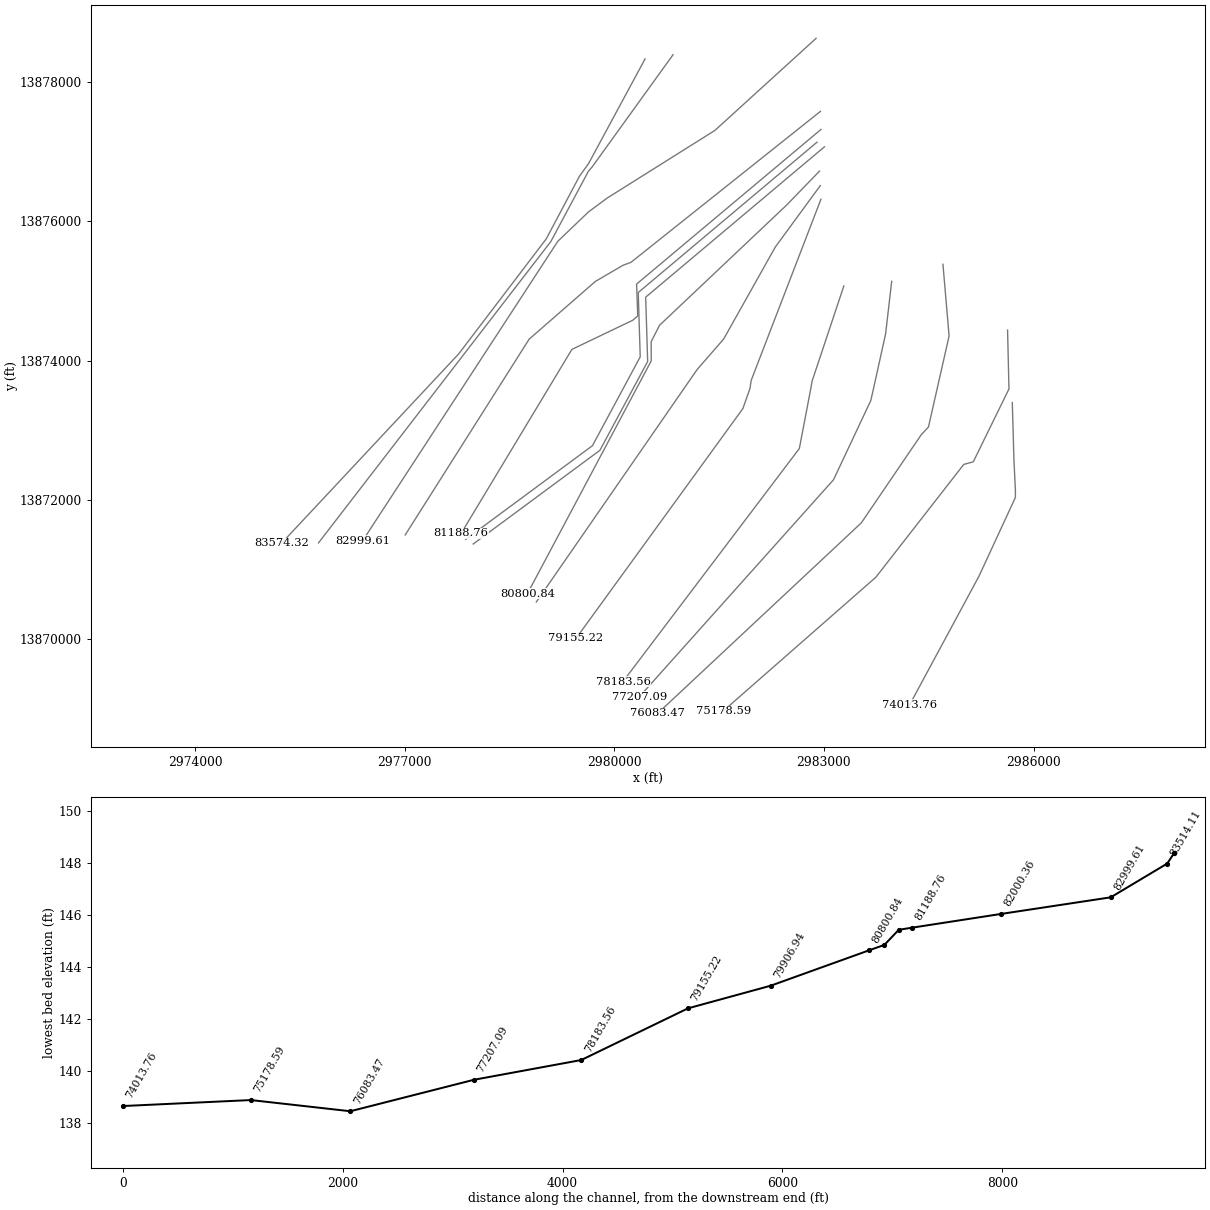
HEC-RAS study U101-00-00.prj: U101-00-00 2019 (Re-Study)

--- U101-00-00.g01 (geometry) --- (continued)

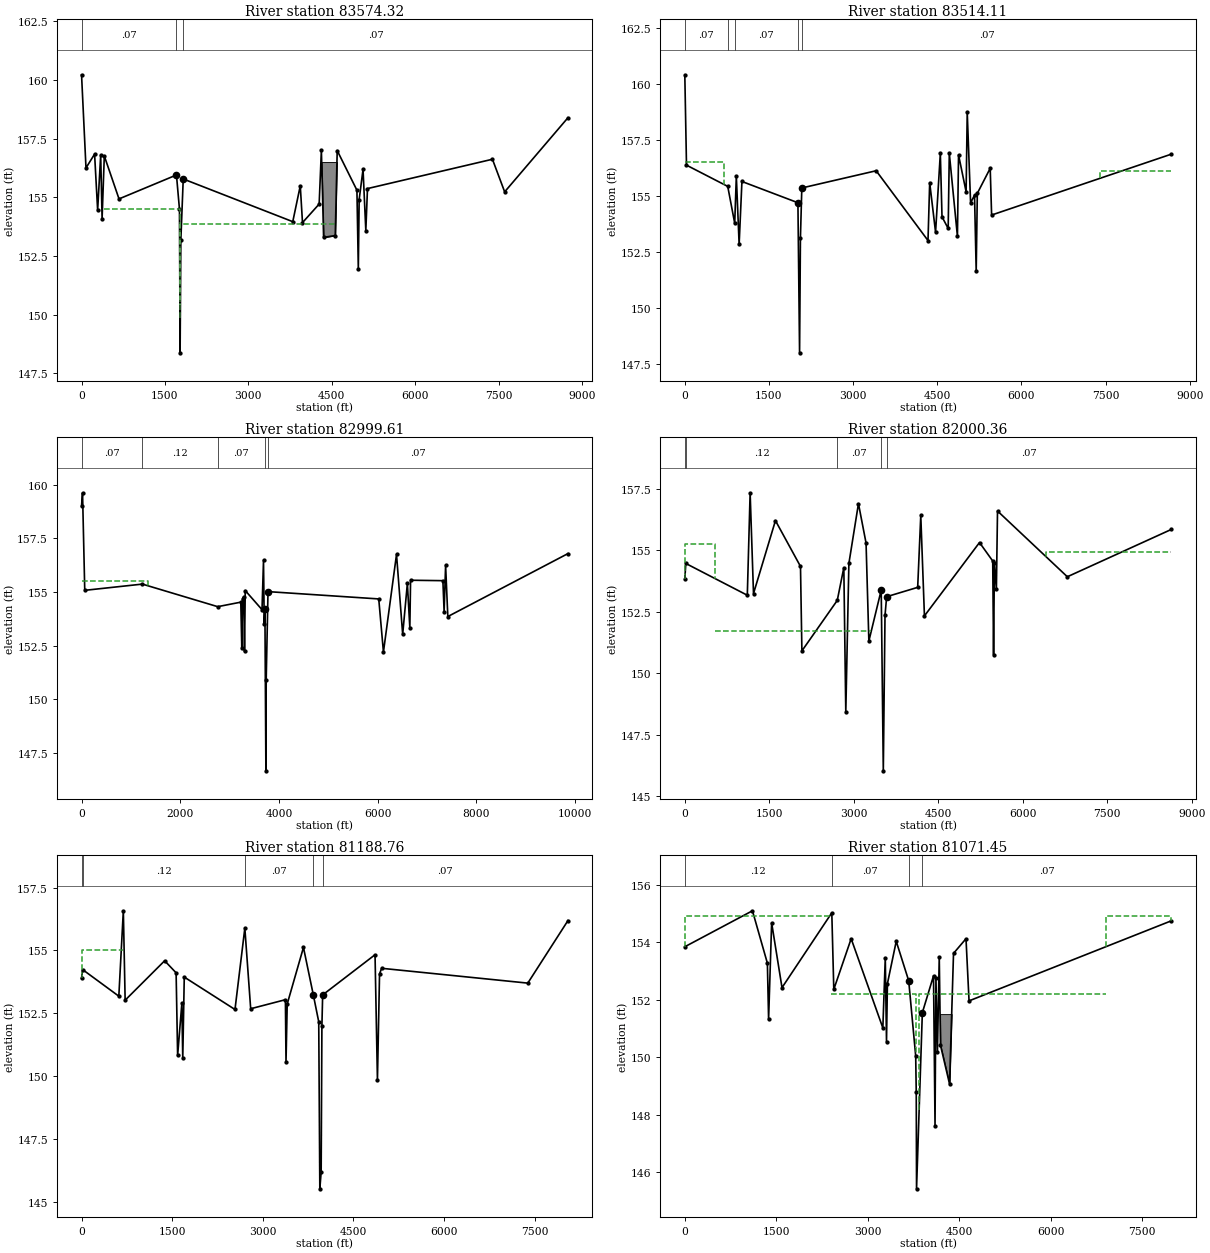
Type RM Length L Ch R = 1 ,83574.32,146.46,60.21,80.66
BEGIN DESCRIPTION:
Downstream Section - 72" CULVERT
END DESCRIPTION:
XS GIS Cut Line= 6
2980441.1941541913878335.99185732979633.1465576913876832.5033944
2979500.2193301213876645.92273082979027.3147641113875749.5990642
2977774.9993553613874097.55807692975235.5693948613871371.8191058
#Sta/Elev= 30
       0  160.22   79.85  156.25  234.57  156.84  289.47  154.45  344.37   156.8
  369.32  154.09  409.25  156.76  673.77  154.93 1706.87  155.95 1761.16  154.49
 1772.48  148.37 1786.01  153.18 1828.78  155.78 3798.84  153.96 3933.71  155.49
 3973.67  153.92 4273.39  154.71 4313.35     157 4353.31  153.29 4563.12  153.37
 4598.08  156.99 4952.75   155.3 4977.73  151.93 4992.72   154.9 5062.64  156.19
 5112.58  153.58 5142.54  155.37 7389.79  156.62 7609.52  155.23 8748.15  158.39
#Mann= 3 ,-1 , 0
       0     .07       0 1706.87     .05       0 1828.78     .07       0
#XS Ineff= 4 ,-1
       0  409.25  156.76  409.25 1768.68   154.5 1776.68 4588.09  153.85
 4588.09 8748.15  155.85
Permanent Ineff=
       F       F       F       F
#Block Obstruct= 1 ,-1
 4313.35 4598.08   156.5
Bank Sta=1706.87,1828.78
XS Rating Curve= 0 ,0
Exp/Cntr=0.5,0.3

Type RM Length L Ch R = 1 ,83514.11,728.91,514.5,287.83
Node Name=AS
XS GIS Cut Line= 5
2980841.8117912713878396.31391512979683.1900927713876782.4798724
2979631.1800261913876722.56004482979092.8448167713875711.5131824
2975767.9052724413871380.5697445
#Sta/Elev= 30
       0  160.41   29.95  156.37  765.41  155.42  889.81  153.77  918.46  155.88
  968.38  152.83 1018.29  155.64 2016.43  154.69 2045.93  147.98 2061.06  153.11
 2085.94  155.35 3411.28  156.12 4335.44     153 4365.41  155.59 4470.32  153.37
 4555.24   156.9 4585.21  154.06 4695.11  153.54 4715.09   156.9 4859.96  153.19
 4879.94  156.83 5014.82  155.18  5034.8  158.73 5094.74  154.68 5164.68  155.03
 5194.65  151.63 5214.63  155.11 5444.42  156.23  5469.4  154.14 8671.43  156.86
#Mann= 5 ,-1 , 0
       0     .07       0  765.41     .12       0  889.81     .07       0
 2016.43     .04       0 2085.94     .07       0
#XS Ineff= 3 ,-1
       0  703.82   156.5 4558.88 7402.62     154 7402.62 8671.43  156.09
Permanent Ineff=
       F       F       F
Bank Sta=2016.43,2085.94
XS Rating Curve= 0 ,0
Exp/Cntr=0.3,0.1

Type RM Length L Ch R = 1 ,82999.61,941.86,999.25,975.59
XS GIS Cut Line= 6
2982887.9212161213878630.76390552981439.91033261 13877307.284269
2979898.1000960313876335.23011082979630.9444623613876136.0625301
2979193.6139721913875716.01678232976401.7232305313871414.4217109
#Sta/Elev= 30
       0  159.01   19.97  159.62   64.89  155.08 1232.19  155.37 2758.65  154.32
  3226.5  154.53  3246.5  152.41 3261.49   154.7 3286.49  154.79 3301.49  152.24
 3316.48  155.07 3656.42  154.18 3686.42  156.48 3701.42   153.5 3714.94  154.21
 3734.97  146.68 3741.01  150.93 3777.73  155.02 6021.35  154.68 6116.32  152.21
 6381.22  156.75 6506.17  153.03 6601.13   155.4 6651.11  153.34 6666.11  155.55
 7320.86  155.53 7345.85  154.08 7375.84  156.24 7420.82  153.86 9854.87  156.79
#Mann= 5 ,-1 , 0
       0     .07       0 1232.19     .12       0 2758.65     .07       0
 3714.94     .05       0 3777.73     .07       0
#XS Ineff= 4 ,-1
       0 1337.76   155.5 1337.76 3289.92     154  6036.5 7375.84     154
 7375.84 9854.87   155.5
Permanent Ineff=
       F       F       F       F
Bank Sta=3714.94,3777.73
XS Rating Curve= 0 ,0
Exp/Cntr=0.3,0.1

Type RM Length L Ch R = 1 ,82000.36,296.69,811.6,783.78
XS GIS Cut Line= 6
2982950.5726656213877581.35688362980238.6000711913875411.6801206
2980125.74990319 13875370.1700332979727.5079175213875135.9930079
2978781.8123023713874307.47465192977008.9976065313871495.0058673
#Sta/Elev= 30
       0  153.83   17.92  154.46 1109.82  153.17 1159.81  157.33 1219.77  153.24
 1609.48   156.2 2054.14  154.34 2079.12  150.91 2707.11  152.96 2823.57  154.29
 2858.55  148.42 2913.51  154.46 3083.38  156.89 3218.28  155.29 3268.25  151.31
 3487.52  153.38  3524.7  146.04 3554.86  152.35 3583.72  153.11 4135.15  153.49
 4190.03  156.41 4254.89  152.33 5232.79  155.31  5467.6  154.56  5482.6  150.76
  5497.6  154.49  5532.6  153.41 5552.59  156.59 6792.46  153.92 8637.21  155.84
#Mann= 5 ,-1 , 0
       0     .07       0   17.92     .12       0 2707.11     .07       0
 3487.52     .06       0 3583.72     .07       0
#XS Ineff= 4 ,-1
       0  544.91  155.25  544.91 3312.21  151.73 4927.37  6412.5  152.82
  6412.5 8637.21  154.91
Permanent Ineff=
       F       F       F       F
Bank Sta=3487.52,3583.72
XS Rating Curve= 0 ,0
Exp/Cntr=0.3,0.1

Type RM Length L Ch R = 1 ,81188.76,114.39,117.31,497.26
XS GIS Cut Line= 6
2982958.4286210213877322.11396382980319.5300274513875099.5101413
2980336.0398369413874641.99005892980264.08000711  13874579.27004
2979394.0764977813874161.27350072977807.8109695313871515.4766269
#Sta/Elev= 30
       0  153.89   16.68  154.24  617.21  153.18  691.88  156.58  721.74  153.02
 1375.77  154.59 1565.72  154.11 1590.71  150.82 1660.69  152.89 1675.69  150.71
 1700.68  153.94 2540.43  152.65 2703.53  155.89 2800.35  152.68 3375.18  153.04
 3385.18  150.56 3405.18  152.87 3674.09  155.12 3838.31  153.22 3927.07  152.16
 3945.07  145.51 3967.25  146.18 3979.57     152    3992  153.23 4859.18  154.83
 4898.98  149.84 4933.81  154.07 4968.63  154.29 7388.51   153.7 8053.48  156.19
#Mann= 5 ,-1 , 0
       0     .07       0   16.68     .12       0 2703.53     .07       0
 3838.31     .06       0    3992     .07       0
#XS Ineff= 3 ,-1
       0  691.88     155  691.88 3376.18  151.73 4245.94 8053.48  152.82
Permanent Ineff=
       F       F       F
Bank Sta=3838.31,3992
XS Rating Curve= 0 ,0
Exp/Cntr=0.5,0.3

Type RM Length L Ch R = 1 ,81071.45,133.22,130.39,145.01
BEGIN DESCRIPTION:
Upstream Section - KATY-HOCKLEY CUTOFF RD
END DESCRIPTION:
XS GIS Cut Line= 6
2982900.7476340213877138.41649652980342.8974347713874977.7735081
2980357.4243086113874509.49951032980371.5584666913874053.8770619
2979687.8754508613872777.29660982977875.4364904513871431.2973334
#Sta/Elev= 30
       0  153.84 1109.43  155.09  1354.3  153.27 1374.29  151.32 1424.27  154.67
 1594.18  152.42 2411.05  155.02 2443.75  152.36  2728.6  154.12 3248.34  151.02
 3288.32  153.46 3308.31  150.54  3323.3  152.56 3467.91  154.03 3672.26  152.66
  3786.9  150.05 3796.07  148.79 3800.96  145.43 3896.08  151.55 4079.41  152.83
 4104.18  147.63 4119.04  152.76 4143.82   150.2 4173.54  153.49 4193.36  150.42
 4342.55  149.07 4407.46  153.61  4612.2  154.12 4662.13  151.96 7978.34  154.74
#Mann= 4 ,-1 , 0
       0     .12       0 2411.05     .07       0 3672.26     .06       0
 3896.08     .07       0
#XS Ineff= 4 ,-1
       0 2393.77   154.9 2393.77  3784.1   152.2 3843.79 6914.49   152.2
 6914.49 7978.34   154.9
Permanent Ineff=
       F       F       F       F
#Block Obstruct= 1 ,-1
 4173.54 4422.44   151.5
Bank Sta=3672.26,3896.08
XS Rating Curve= 0 ,0
Exp/Cntr=0.5,0.3

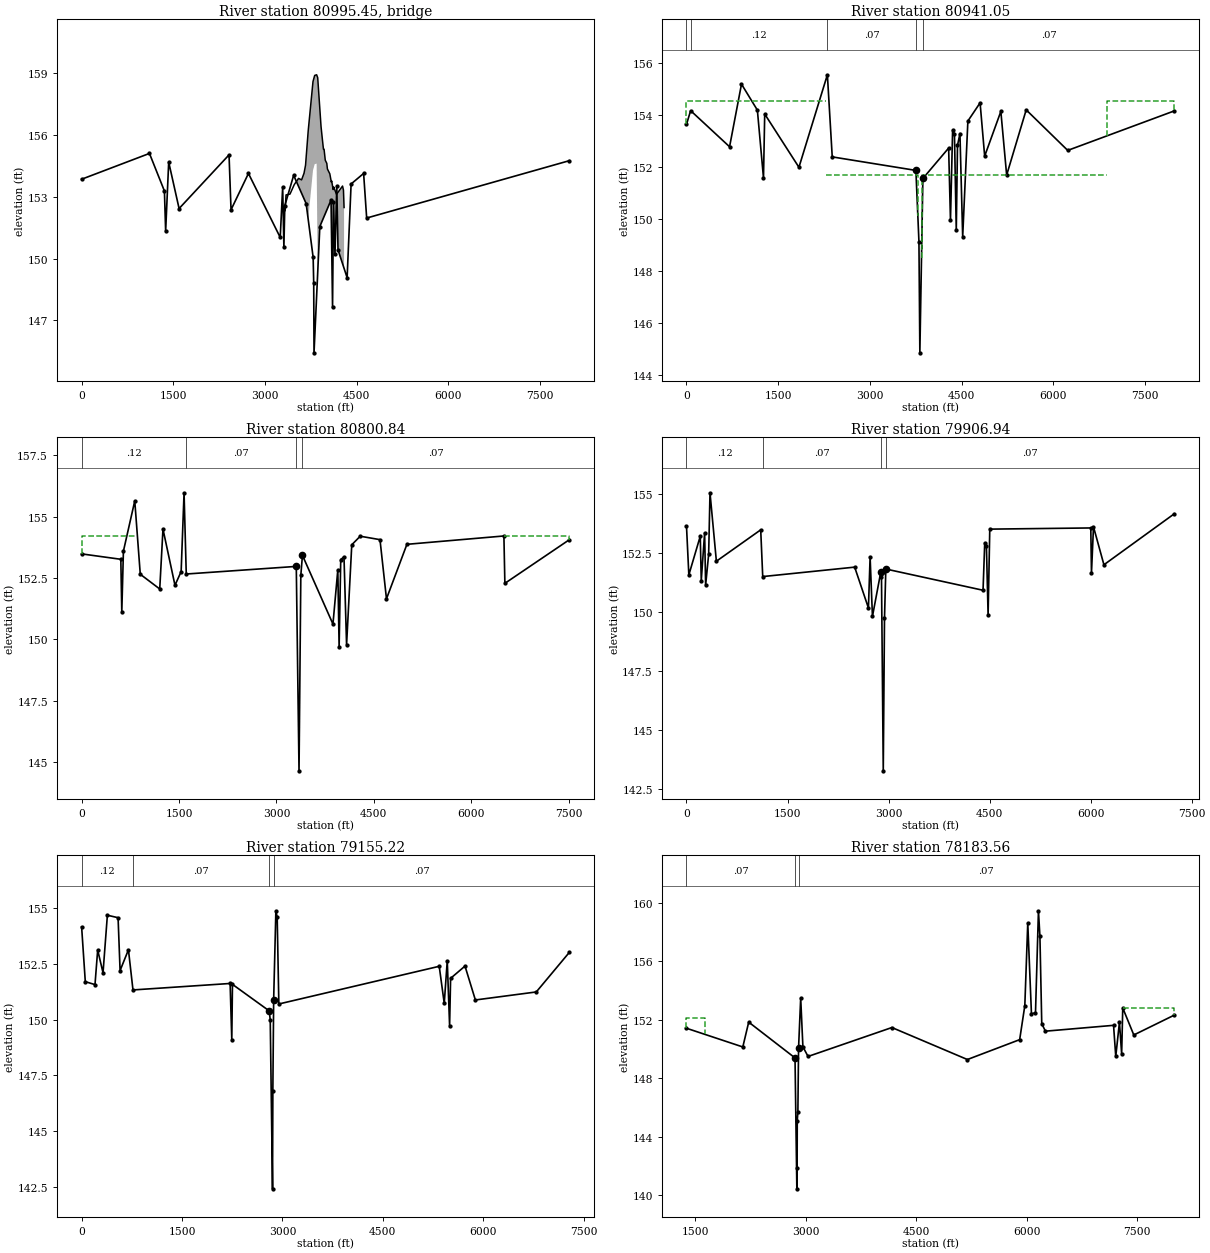
Type RM Length L Ch R = 3 ,80995.45,,,
BEGIN DESCRIPTION:
KATY-HOCKLEY CUTOFF RD
END DESCRIPTION:
Node Name=KATY-HOCKLEY CUT
Bridge Culvert--1,0,-1,-1, 0
Deck Dist Width WeirC Skew NumUp NumDn MinLoCord MaxHiCord MaxSubmerge Is_Ogee
54.5,40.5,2.6,0, 29, 29, , , 0.98, 0, 0,0,,
  3328.3 3343.29  3408.1 3477.88 3547.66  3597.5 3637.37 3662.29 3705.99  3784.1
 3811.82 3843.79 3861.39 3916.01 3935.72 3955.54 3965.45 3985.26 4010.04 4019.95
 4059.59 4084.36 4089.32 4114.09    4124 4168.59 4267.68 4282.62 4292.61
  152.32  153.08  153.12  153.58  153.88  153.81  154.13  154.52  156.19  158.57
  158.87   158.9  158.76  156.39  155.83  155.29  155.29  154.76  154.61  154.34
   154.1   153.7  153.76  153.34  153.46  153.11  153.51  153.31  152.47
       0       0       0       0       0       0       0       0       0  154.27
  154.57   154.6       0       0       0       0       0       0       0       0
       0       0       0       0       0       0       0       0       0
  3328.3 3343.29  3408.1 3477.88 3547.66  3597.5 3637.37 3662.29 3705.99  3784.1
 3811.82 3843.79 3861.39 3916.01 3935.72 3955.54 3965.45 3985.26 4010.04 4019.95
 4059.59 4084.36 4089.32 4114.09    4124 4168.59 4267.68 4282.62 4292.61
  152.32  153.08  153.12  153.58  153.88  153.81  154.13  154.52  156.19  158.57
  158.87   158.9  158.76  156.39  155.83  155.29  155.29  154.76  154.61  154.34
   154.1   153.7  153.76  153.34  153.46  153.11  153.51  153.31  152.47
       0       0       0       0       0       0       0       0       0  154.22
  154.52  154.55       0       0       0       0       0       0       0       0
       0       0       0       0       0       0       0       0       0
Abutment Skew #Up #Dn= , 3 , 3
  3781.9  3783.9  3785.3
  154.27  154.27  149.05
  3781.9  3783.9  3785.3
  154.22  154.22     149
Abutment Skew #Up #Dn= , 3 , 3
  3841.3 3843.99 3845.99
  152.21   154.6   154.6
  3841.3 3843.99 3845.99
  152.16  154.55  154.55
BR Coef=-1 , 0 , 0 ,, 0 ,,,0.8,-1,,0,
WSPro=,,,, 1 ,,,, 0 ,,,, 0 ,,,,-1 ,-1 ,-1 , 0 , 0 , 0 , 0 , 0
BC Design=,, 0 ,, 0 ,,,,,,
BC Use User HTab Curves=0
BC User HTab FreeFlow(D)= 0

Type RM Length L Ch R = 1 ,80941.05,420.95,140.21,51.45
BEGIN DESCRIPTION:
Downstream Section - KATY-HOCKLEY CUTOFF RD
END DESCRIPTION:
Node Name=AR
XS GIS Cut Line= 6
2983007.3264891113877071.90777132980449.4762898513874911.2647828
 2980464.0031637 13874442.9907852980478.1373217713873987.3683367
2979794.4543059513872710.78788462977982.0153455313871364.7886081
#Sta/Elev= 30
       0  153.64   67.69  154.17  704.64  152.78  899.54  155.19  1159.4  154.19
 1259.35  151.58 1279.34  154.04 1839.05  151.99 2304.37  155.55 2383.78  152.39
 3752.01  151.87 3801.85  149.13  3816.8  144.85 3866.35  151.56 4287.62  152.73
 4317.58  149.95 4352.53  153.41 4382.49  153.28 4412.46  149.57 4432.43  152.83
 4472.38  153.29 4517.32  149.32 4602.21  153.77 4801.95  154.47 4876.86  152.42
 5141.52  154.14 5236.39  151.69 5555.98   154.2 6235.22  152.64 7978.34  154.16
#Mann= 5 ,-1 , 0
       0     .07       0   67.69     .12       0 2304.37     .07       0
 3752.01     .06       0 3866.35     .07       0
#XS Ineff= 4 ,-1
       0 2283.83  154.56 2283.83  3784.1   151.7 3843.79 6869.54   151.7
 6869.54 7978.34  154.56
Permanent Ineff=
       F       F       F       F
Bank Sta=3752.01,3866.35
XS Rating Curve= 0 ,0
Exp/Cntr=0.5,0.3

Type RM Length L Ch R = 1 ,80800.84,778.24,893.9,612.41
BEGIN DESCRIPTION:
CONFLUENCE WITH U101-12-00
END DESCRIPTION:
XS GIS Cut Line= 6
2982936.5431661213876722.52723642982465.5841342813876234.0613499
2980647.8200532813874507.30988212980527.9098600313874271.1699344
2980529.23006736 13873996.2200252978756.9481788613870650.2181869
#Sta/Elev= 30
       0  153.48  603.69  153.26  618.66  151.11   643.6  153.59  818.37  155.64
  903.28  152.65 1202.94  152.05 1252.88  154.49 1437.67   152.2 1532.56  152.76
 1577.51  155.97 1611.33  152.66 3305.65  152.97 3347.84  144.64  3375.6  152.61
 3400.59  153.42 3870.37  150.62  3945.3  152.83 3965.28  149.68 3990.26  153.25
 4040.21  153.36 4080.17  149.78  4160.1  153.85 4289.98   154.2 4594.69  154.06
  4694.6  151.65  5009.3  153.87 6502.89  154.21 6517.88  152.28 7511.94  154.06
#Mann= 4 ,-1 , 0
       0     .12       0 1611.33     .07       0 3305.65     .06       0
 3400.59     .07       0
#XS Ineff= 2 ,-1
       0  818.37  154.21 6502.89 7511.94  154.21
Permanent Ineff=
       F       F
Bank Sta=3305.65,3400.59
XS Rating Curve= 0 ,0
Exp/Cntr=0.3,0.1

Type RM Length L Ch R = 1 ,79906.94,595.78,751.72,868.13
Node Name=AQ
XS GIS Cut Line= 5
2982948.53198728 13876514.7189252982304.8603743613875632.6002824
2981565.6000418713874310.28009242981185.2799363613873870.7901578
2978885.1739722813870531.9805624
#Sta/Elev= 30
       0  153.65    34.9  151.58  204.44  153.22   219.4  151.34  269.26  153.36
  284.22  151.15  329.09  152.45  349.04  155.06  443.78  152.16 1101.99  153.49
 1131.88  151.51 2496.93  151.91 2701.31  150.18 2726.15  152.34 2760.92  149.82
 2885.11  151.71 2895.05  151.48 2921.53  143.28 2939.76  149.74 2959.63  151.83
 4402.95  150.93 4427.95  152.94 4452.94  152.81 4477.94  149.88 4502.93  153.52
 6002.69  153.57 6012.69  151.65 6042.69  153.62 6197.66  152.01 7242.49  154.17
#Mann= 4 ,-1 , 0
       0     .12       0 1131.88     .07       0 2885.11     .06       0
 2959.63     .07       0
#XS Ineff= 2 ,-1
       0  349.04  153.65 4502.93 7242.49  153.52
Permanent Ineff=
       F       F
Bank Sta=2885.11,2959.63
XS Rating Curve= 0 ,0
Exp/Cntr=0.3,0.1

Type RM Length L Ch R = 1 ,79155.22,832.1,971.66,1033.52
XS GIS Cut Line= 5
2982957.7347247813876319.05921142981959.4699890313873716.0998504
2981941.6301296913873598.54988862981840.4324974413873310.5980367
2979453.2781510213870008.1279356
#Sta/Elev= 30
       0  154.16   54.96   151.7  199.84  151.57  239.81  153.12  319.75   152.1
   384.7  154.68  544.57  154.57  574.55   152.2  699.45  153.13  767.23  151.33
 2218.26  151.62 2243.24  149.09 2253.24  151.58 2802.69  150.39 2817.55  149.98
 2851.82  142.41 2856.61  146.82 2868.68   150.9 2901.77  154.88 2921.49  154.58
  2946.1   150.7  5341.9  152.39  5416.9  150.73  5461.9  152.64  5496.9  149.72
  5511.9  151.85  5726.9   152.4 5881.89  150.88 6791.88  151.24 7286.88  153.02
#Mann= 4 ,-1 , 0
       0     .12       0  767.23     .07       0 2802.69     .05       0
 2868.68     .07       0
#XS Ineff= 2 ,-1
       0  699.45  152.64  5461.9 7286.88  152.64
Permanent Ineff=
       F       F
Bank Sta=2802.69,2868.68
XS Rating Curve= 0 ,0
Exp/Cntr=0.3,0.1

Type RM Length L Ch R = 1 ,78183.56,880.48,976.46,807.05
Node Name=AP
XS GIS Cut Line= 5
2983285.3754113513875073.1736412  2982830.159849  13873703.13006
  2982812.319989 13873598.549889  2982648.099845 13872735.969921
  2980125.296164 13869388.455947
#Sta/Elev= 30
 1383.74  151.41 2148.05  150.13 2227.98  151.83 2856.46  149.38 2881.29  140.42
 2885.02  141.83  2886.8  145.09 2895.28  145.67  2904.5  150.05 2933.52  153.48
 2963.46  150.14 3033.31  149.48 4171.33  151.46 5195.53  149.27 5904.98  150.63
 5974.92  152.96 6014.89  158.61 6064.85   152.4 6119.81  152.47 6159.78  159.45
 6179.76  157.71 6204.74  151.72  6254.7  151.21 7178.98  151.61 7208.96  149.48
 7258.92  151.82  7288.9  149.65 7303.88   152.8 7453.77  150.95 8003.34  152.31
#Mann= 3 ,-1 , 0
 1383.74     .07       0 2856.46     .05       0  2904.5     .07       0
#XS Ineff= 3 ,-1
 1383.74 1638.51  152.09 6159.78 7303.88  151.45 7303.88 8003.34   152.8
Permanent Ineff=
       F       F       F
Bank Sta=2856.46,2904.5
XS Rating Curve= 0 ,0
Exp/Cntr=0.3,0.1

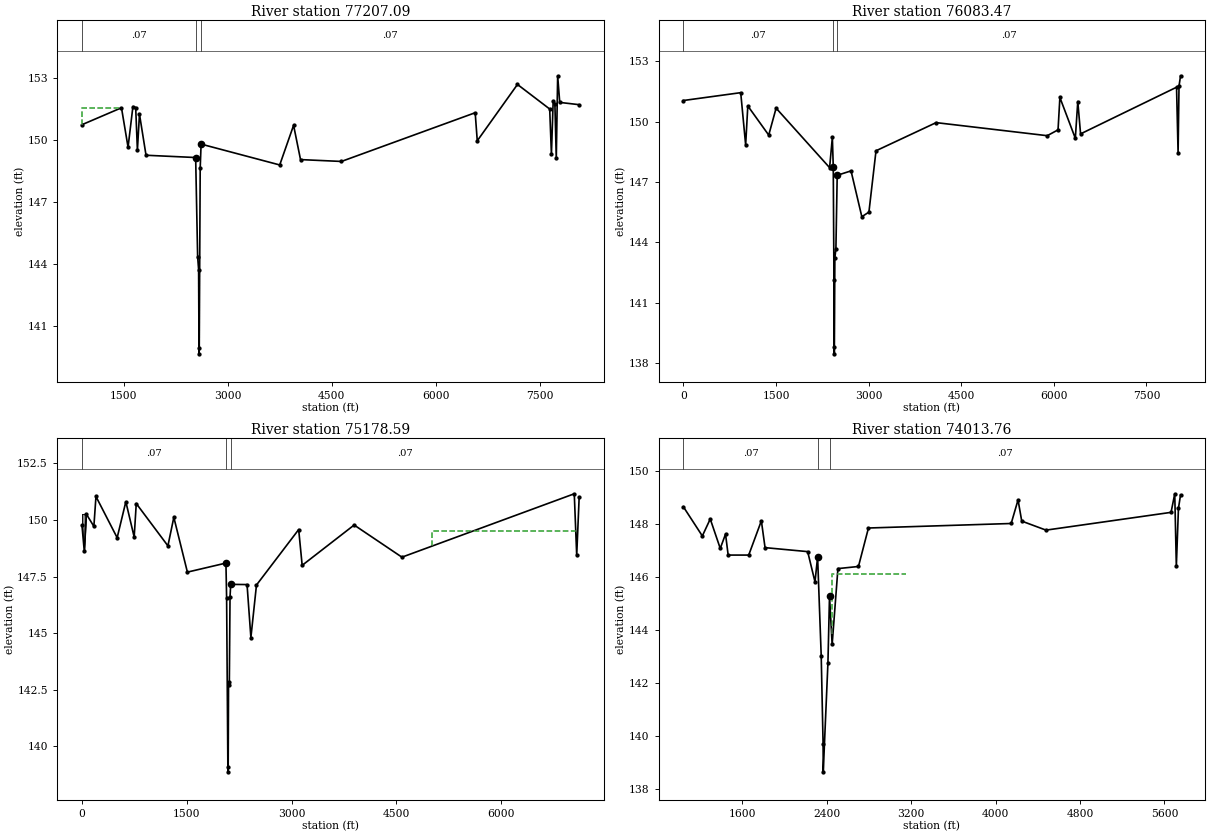
Type RM Length L Ch R = 1 ,77207.09,975.6,1123.62,840.07
Node Name=AO
XS GIS Cut Line= 6
2983969.8334513613875138.98073892983882.7194233513874383.9981209
2983700.85003644 13873558.0201142983670.0400586913873424.2500404
2983137.67235702 13872288.046276 2980361.1841436 13869170.942274
#Sta/Elev= 30
  894.98  150.76 1464.97  151.58 1559.97  149.67 1629.97  151.64 1669.89  151.59
 1694.77  149.53 1724.62  151.27 1819.14  149.28 2535.05  149.17 2563.47  144.37
 2577.77  143.74 2583.69  139.66 2586.88  139.93 2600.55  148.66  2613.5  149.82
 3747.78  148.81 3947.74  150.73 4047.72  149.07 4637.63  148.98 6567.33  151.34
 6597.33  149.98 7177.23  152.71 7642.16  151.52 7667.16  149.32 7692.15  151.89
 7717.15  151.76 7737.15  149.13 7757.14  153.13 7787.14  151.84  8067.1  151.73
#Mann= 3 ,-1 , 0
  894.98     .07       0 2535.05     .05       0  2613.5     .07       0
#XS Ineff= 2 ,-1
  894.98 1464.97  151.58 7177.23  8067.1  151.58
Permanent Ineff=
       F       F
Bank Sta=2535.05,2613.5
XS Rating Curve= 0 ,0
Exp/Cntr=0.3,0.1

Type RM Length L Ch R = 1 ,76083.47,908.54,904.88,743.77
XS GIS Cut Line= 6
2984703.2348426913875383.70215822984791.2290892813874353.6284309
2984496.1499550313873046.4601135 2984389.939865613872930.5298992
2983536.0452479413871669.14003352980621.7512077813868930.6717572
#Sta/Elev= 30
       0  151.05  928.95  151.44 1008.85  148.84 1043.79  150.78 1382.54  149.33
  1502.1  150.67  2368.9  147.71 2413.19  149.22 2427.93  147.76 2439.14  142.12
 2442.12  138.77 2445.39  138.45 2453.74  143.22 2470.81  143.68  2491.8  147.33
 2715.89  147.55 2890.69  145.27 3005.55   145.5 3120.42  148.55 4094.31  149.95
 5893.87   149.3 6068.83  149.59 6098.82   151.2 6348.76  149.17 6388.75     151
 6433.74  149.39 7988.36  151.71 8013.35  148.44 8028.35  151.77 8053.34  152.28
#Mann= 3 , 0 , 0
       0     .07       0 2427.93     .05       0  2491.8     .07       0
#XS Ineff= 2 ,-1
       0 1043.29   150.2 6098.82 8053.34   150.2
Permanent Ineff=
       F       F
Bank Sta=2427.93,2491.8
XS Rating Curve= 0 ,0
Exp/Cntr=0.3,0.1

Type RM Length L Ch R = 1 ,75178.59,422.56,1164.83,1023.23
XS GIS Cut Line= 6
2985627.8707886913874439.21224932985647.9327564413873592.7487191
2985137.4101554513872545.44996072985001.20996852 13872508.160009
2983743.2594004413870887.15275242981558.6935596213868963.6684103
#Sta/Elev= 30
       0  149.77   32.78  148.64   61.16  150.27  170.54  149.72  200.37  151.04
  503.65  149.22  627.94  150.81  747.27  149.25   777.1  150.73 1230.09  148.86
 1314.73  150.12 1508.92   147.7  2060.5   148.1 2070.24  146.56 2088.01  139.11
  2092.3  138.88 2097.72  142.73  2109.2  142.84    2119   146.6 2128.67  147.16
 2362.69  147.15 2417.61  144.81 2497.49  147.13 3101.56  149.58 3151.48     148
 3895.34  149.78 4579.32  148.36 7045.71  151.16 7080.66  148.44 7115.61     151
#Mann= 3 , 0 , 0
       0     .07       0  2060.5     .06       0 2128.67     .07       0
#XS Ineff= 2 ,-1
       0 1314.73   149.5 5013.68 7115.61   149.5
Permanent Ineff=
       F       F
#Block Obstruct= 2 , 0
       0   61.16  150.27               0
Bank Sta=2060.5,2128.67
XS Rating Curve= 0 ,0
Exp/Cntr=0.3,0.1

Type RM Length L Ch R = 1 ,74013.76,35.62,30.21,205.05
Node Name=AN
XS GIS Cut Line= 6
2985695.5617576813873396.93546142985719.0198846213872573.6900617
2985740.1500916913872131.27985732985739.8298823513872033.5799214
2985218.8299401113870901.88008512984225.91525927 13869052.741723
#Sta/Elev= 30
 1043.59  148.64 1223.28  147.54 1298.15  148.18 1392.99  147.07  1442.9  147.61
 1467.86  146.82 1662.52  146.82 1782.32  148.11 1817.26   147.1 2220.88  146.95
 2290.26  145.81 2314.97  146.75 2349.16  143.02 2366.87   139.7 2368.46  138.65
 2412.82  142.76 2427.72  145.28 2452.63  143.45 2507.45  146.31 2701.81  146.39
 2796.49  147.84 4148.39  148.01 4213.35   148.9 4248.33   148.1 4478.21  147.76
 5662.55  148.43 5697.53  149.13 5712.53  146.39 5732.51  148.58  5752.5  149.09
#Mann= 3 ,-1 , 0
 1043.59     .07       0 2314.97     .06       0 2427.72     .07       0
#XS Ineff= 3 ,-1
 1043.59 2242.31  146.36 2447.16 3155.31  146.09 4213.35  5752.5   148.9
Permanent Ineff=
       F       F       F
Bank Sta=2314.97,2427.72
XS Rating Curve= 0 ,0
Exp/Cntr=0.5,0.3