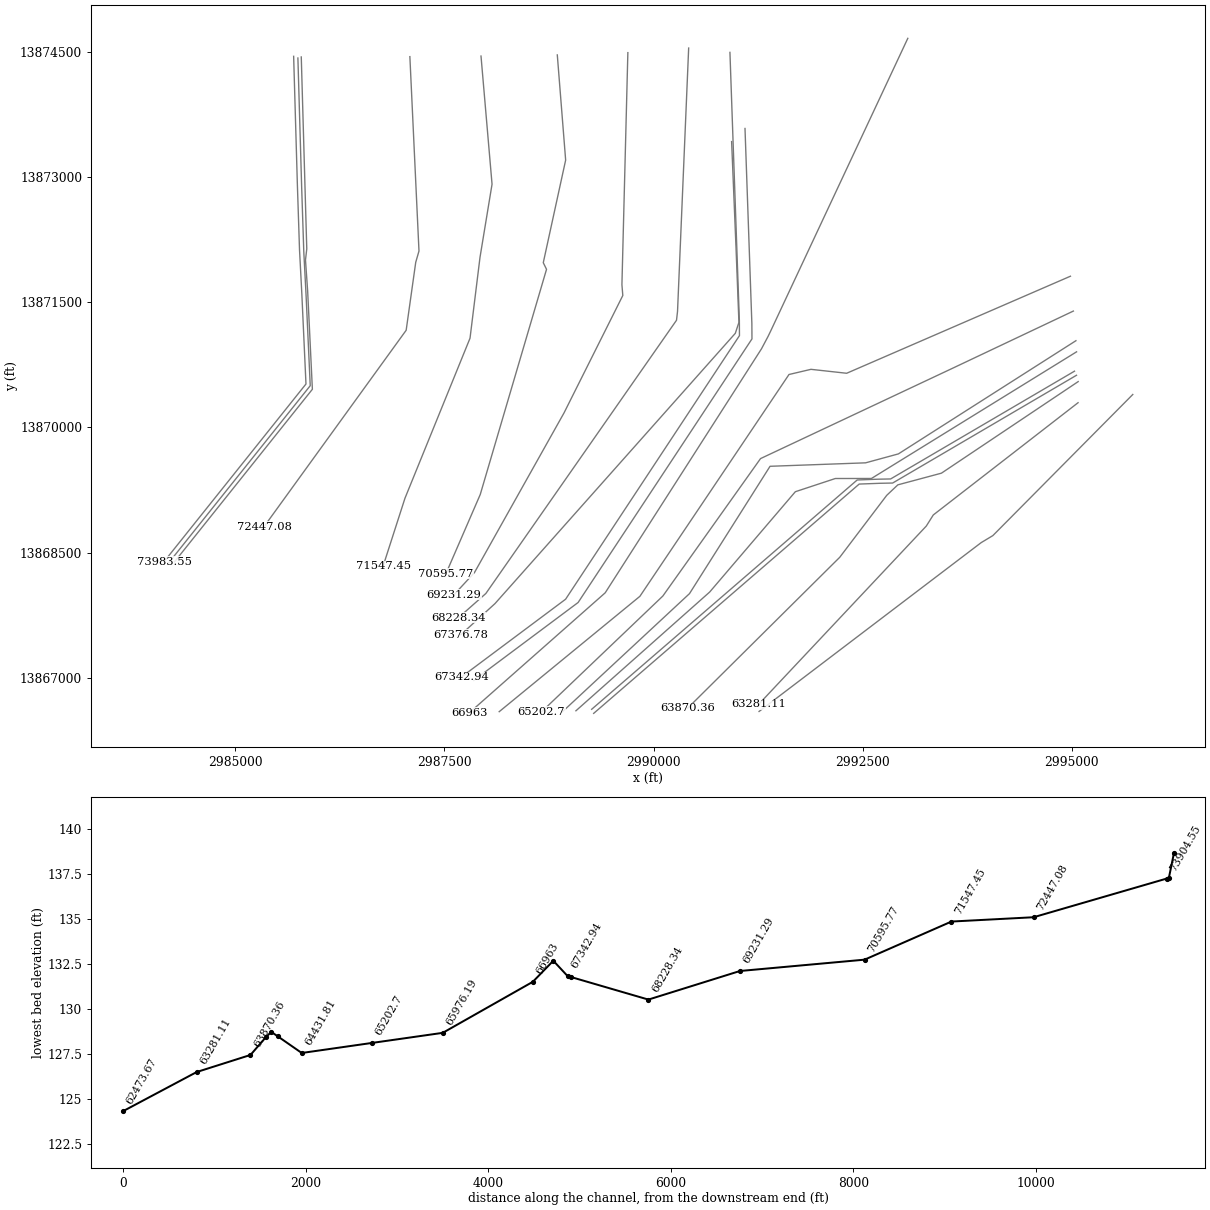
HEC-RAS study U101-00-00.prj: U101-00-00 2019 (Re-Study)

--- U101-00-00.g01 (geometry) --- (continued)

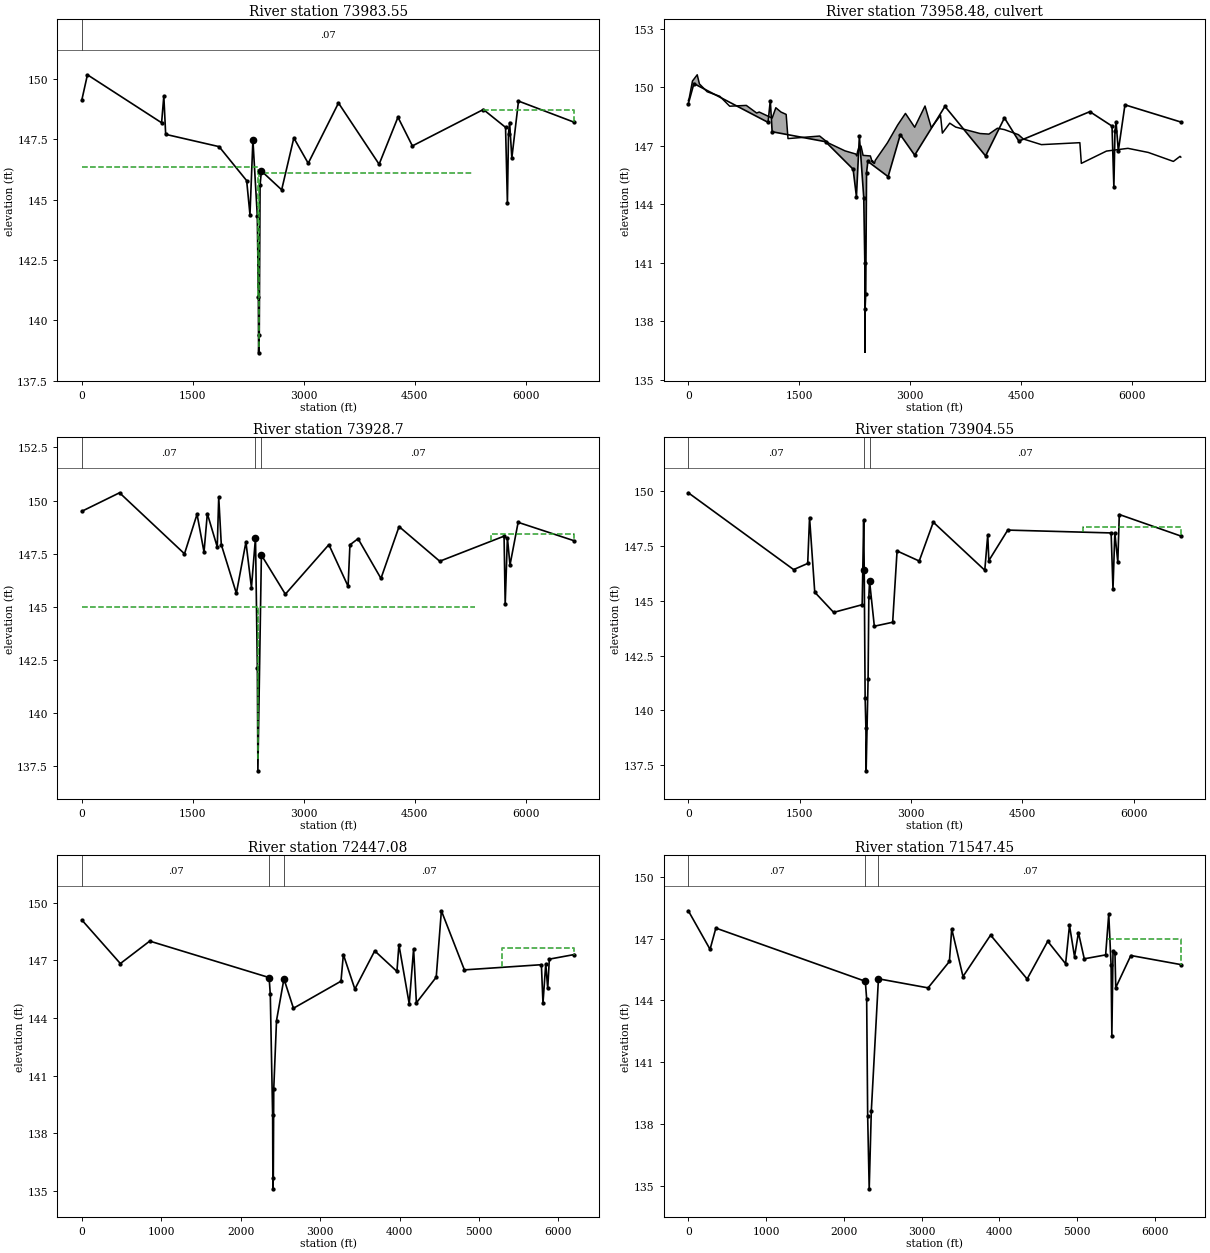
Type RM Length L Ch R = 1 ,73983.55,55.92,54.84,74.34
BEGIN DESCRIPTION:
Upstream Section - PORTER ROAD
END DESCRIPTION:
XS GIS Cut Line= 6
   2985696.3742613874450.4950351 2985741.238672213872904.4069199
 2985766.678253913872129.7759233 2985794.494143113871597.5650454
  2985843.82836213870521.0219229 2984146.941149613868390.9868105
#Sta/Elev= 30
       0  149.14    75.4  150.18 1077.91  148.19 1107.83   149.3 1132.77  147.71
 1854.77   147.2  2227.4  145.79 2272.11  144.38 2311.86  147.48 2370.98  144.34
 2385.51  140.98    2389  138.65 2397.65   139.4 2408.64   145.6 2426.42  146.19
 2700.35  145.41 2864.72  147.56  3059.3  146.51 3468.43  149.01 4017.38  146.47
 4272.22  148.42 4467.09  147.23 5426.48  148.74 5726.29     148 5751.28  144.87
 5766.27  147.74 5781.26   148.2 5811.24  146.73 5901.18  149.09 6655.73  148.21
#Mann= 1 ,-1 , 0
       0     .07       0
#XS Ineff= 3 ,-1
       0  2385.7  146.36  2391.7 5281.59  146.09 5426.48 6655.73  148.74
Permanent Ineff=
       F       F       T
Bank Sta=2311.86,2426.42
XS Rating Curve= 0 ,0
Exp/Cntr=0.5,0.3

Type RM Length L Ch R = 2 ,73958.48,,,
BEGIN DESCRIPTION:
PORTER ROAD
END DESCRIPTION:
Node Name=PORTER ROAD
Bridge Culvert--1,0,-1,-1, 0
Deck Dist Width WeirC Skew NumUp NumDn MinLoCord MaxHiCord MaxSubmerge Is_Ogee
20.5,12,2.6,0, 58, 58, , , 0.98, 0, 0,0,,
       0   14.02   56.08  120.29  150.22  254.96  424.53   559.2  783.64  923.29
   958.2 1132.77 1182.65 1252.47  1322.3 1347.24 1775.28 1889.55 2118.09 2262.17
 2277.08 2287.02 2301.92 2311.86 2326.79  2335.1 2361.73  2460.6 2486.19 2491.17
 2501.13 2516.07 2526.03 2690.39 2829.84 2934.57  3059.3    3199 3283.82 3408.55
  3433.5 3533.29 3613.12 3942.43 4062.35 4177.28 4272.22  4462.1 4527.06 4771.91
 5291.58 5311.57 5651.36 5941.18    6216 6555.79 6645.74 6655.73
   149.3  149.47  150.31  150.63  150.16  149.76  149.53  149.02  149.06  148.67
  148.72  148.41  148.94  148.72   148.6  147.36  147.49  147.14  146.73  146.57
  146.47  146.69  146.87  146.86     147  146.96   146.5  146.47  146.15  146.22
  146.11  146.09  146.24  147.14  148.06  148.65  147.94  149.03  147.92  148.55
  147.64  148.15  147.95  147.62  147.59  147.89  147.82  147.56  147.34  147.05
  147.15  146.09  146.72  146.86  146.65  146.19  146.45  146.41
       0       0       0       0       0       0       0       0       0       0
       0       0       0       0       0       0       0       0       0       0
       0       0       0       0       0       0       0       0       0       0
       0       0       0       0       0       0       0       0       0       0
       0       0       0       0       0       0       0       0       0       0
       0       0       0       0       0       0       0       0
       0   14.02   56.08  120.29  150.22  254.96  424.53   559.2  783.64  923.29
   958.2 1132.77 1182.65 1252.47  1322.3 1347.24 1775.28 1889.55 2118.09 2262.17
 2277.08 2287.02 2301.92 2311.86 2326.79  2335.1 2361.73  2460.6 2486.19 2491.17
 2501.13 2516.07 2526.03 2690.39 2829.84 2934.57  3059.3    3199 3283.82 3408.55
  3433.5 3533.29 3613.12 3942.43 4062.35 4177.28 4272.22  4462.1 4527.06 4771.91
 5291.58 5311.57 5651.36 5941.18    6216 6555.79 6645.74 6655.73
   149.3  149.47  150.31  150.63  150.16  149.76  149.53  149.02  149.06  148.67
  148.72  148.41  148.94  148.72   148.6  147.36  147.49  147.14  146.73  146.57
  146.47  146.69  146.87  146.86     147  146.96   146.5  146.47  146.15  146.22
  146.11  146.09  146.24  147.14  148.06  148.65  147.94  149.03  147.92  148.55
  147.64  148.15  147.95  147.62  147.59  147.89  147.82  147.56  147.34  147.05
  147.15  146.09  146.72  146.86  146.65  146.19  146.45  146.41
       0       0       0       0       0       0       0       0       0       0
       0       0       0       0       0       0       0       0       0       0
       0       0       0       0       0       0       0       0       0       0
       0       0       0       0       0       0       0       0       0       0
       0       0       0       0       0       0       0       0       0       0
       0       0       0       0       0       0       0       0
BR Coef=-1 , 0 , 0 ,, 0 ,,,0.8,-1,,0,
WSPro=,,,, 1 ,,,, 0 ,,,, 0 ,,,,-1 ,-1 ,-1 , 0 , 0 , 0 , 0 , 0
Culvert=1,6,,32,0.013,0.5,1,1,3,136.38,2388.7,136.91,2378.81,Culvert #1  , 0 ,10
Culvert Bottom n=0.013
BC Design=,, 0 ,, 0 ,,,,,,
BC Use User HTab Curves=0
BC User HTab FreeFlow(D)= 0

Type RM Length L Ch R = 1 ,73928.7 ,43.96,24.15,88.31
BEGIN DESCRIPTION:
Downstream Section - PORTER ROAD
END DESCRIPTION:
XS GIS Cut Line= 6
  2985747.279014 13874430.152228  2985792.14342613872884.0641129
 2985817.583007713872109.4331162  2985845.39889713871577.2222383
 2985894.733115913870500.6791158 2984197.845903413868370.6440035
#Sta/Elev= 30
       0   149.5  509.32  150.37 1387.14   147.5 1556.68  149.36 1651.07  147.58
 1695.79  149.39 1829.93  147.82 1849.81  150.17 1884.58  147.93 2088.28  145.64
 2217.46  148.05 2291.98  145.91 2346.75  148.26 2371.71  142.14 2379.11  137.29
 2426.42  147.44 2750.15   145.6  3338.7  147.93 3598.15  145.97 3623.09  147.92
 3732.86  148.21 4042.36  146.34 4287.21  148.78 4836.86  147.15  5706.3  148.33
  5721.3  145.12 5751.28  148.26 5786.25  146.97 5896.18  148.98 6655.73  148.11
#Mann= 3 ,-1 , 0
       0     .07       0 2346.75     .06       0 2426.42     .07       0
#XS Ineff= 3 ,-1
       0 2375.81     145 2381.81 5316.57     145 5531.42 6655.73  148.42
Permanent Ineff=
       F       F       T
Bank Sta=2346.75,2426.42
XS Rating Curve= 0 ,0
Exp/Cntr=0.5,0.3

Type RM Length L Ch R = 1 ,73904.55,1405.76,1457.47,1584.07
XS GIS Cut Line= 6
  2985787.56174213874442.9550239 2985853.379852113872141.2998504
  2985837.92647113872007.8562196 2985863.765658113871638.2739535
 2985920.443038213870458.0407497 2984271.814645813868388.5834253
#Sta/Elev= 30
       0  149.92 1418.67  146.42 1608.44   146.7 1633.41  148.79 1703.32  145.39
 1958.01  144.47 2342.39  144.82  2362.3  148.66    2370   146.4  2382.2  140.57
  2392.6  139.18 2395.57  137.25    2422  141.44 2431.95  145.16 2441.87  145.89
 2506.09  143.84 2753.08  144.02 2812.36  147.27 3110.75  146.81 3300.37  148.58
    3994  146.39 4033.94     148 4048.91  146.83 4303.52  148.22 5696.38  148.09
 5721.34  145.53 5746.31   148.1 5786.24  146.76 5806.21  148.93 6634.87  147.95
#Mann= 3 ,-1 , 0
       0     .07       0    2370     .06       0 2441.87     .07       0
#XS Ineff= 3 ,-1
       0 2312.34     144 2481.45 5202.11     144 5311.97 6634.87  148.34
Permanent Ineff=
       F       F       T
Bank Sta=2370,2441.87
XS Rating Curve= 0 ,0
Exp/Cntr=0.3,0.1

Type RM Length L Ch R = 1 ,72447.08,800.13,899.62,803.66
Node Name=AM
XS GIS Cut Line= 6
  2987086.01747813874446.6275888 2987194.959846113872115.7798883
  2987156.05014713871980.3900672  2987041.68784313871165.5101353
  2985343.25816913868811.7477824 2985343.234740213868811.7153137
#Sta/Elev= 30
       0  149.11  484.67  146.84  854.41  148.01 2357.68  146.11 2372.25  145.23
 2401.65  138.93 2405.42   135.1 2410.28  135.68 2415.87  140.31 2450.63  143.87
 2544.08  146.04 2663.77  144.51 3262.22  145.92 3292.15  147.31 3437.01  145.51
  3686.8   147.5 3966.56  146.43 3991.54  147.82 4121.43  144.74 4176.38  147.61
 4211.35  144.79 4461.14  146.13 4526.09  149.59 4815.84  146.51 5785.02  146.78
    5805  144.77 5839.97  146.82 5864.95  145.54 5884.93  147.07 6199.71  147.31
#Mann= 3 , 0 , 0
       0     .07       0 2357.68     .06       0 2544.08     .07       0
#XS Ineff= 2 ,-1
       0  854.41  147.64 5295.43 6199.71  147.64
Permanent Ineff=
       F       T
Bank Sta=2357.68,2544.08
XS Rating Curve= 0 ,0
Exp/Cntr=0.3,0.1

Type RM Length L Ch R = 1 ,71547.45,806.3,951.68,773.01
Node Name=AL
XS GIS Cut Line= 6
2987936.4977331213874453.48617092988068.4935321113872916.8537454
2987924.5899485213872040.38994722987805.2299510213871070.1874913
2987027.6110994413869151.92393932986765.6365577713868336.2949932
#Sta/Elev= 30
       0  148.35  279.51  146.48  354.38  147.51 2276.59  144.93 2294.06  144.07
 2307.01  138.37 2326.68  134.86 2353.57  138.62 2445.47  145.05 3083.86  144.61
 3358.17  145.89 3388.09  147.47 3533.03  145.16 3888.01  147.17 4357.98  145.04
 4622.95  146.87 4852.93  145.78 4902.93  147.64 4967.92  146.12 5017.92  147.29
 5092.91  146.02 5367.89  146.21 5407.88  148.19 5437.88  145.71 5447.88  142.27
 5462.88   146.4 5487.84  146.32  5497.8  144.62 5692.04  146.18 6334.54  145.74
#Mann= 3 ,-1 , 0
       0     .07       0 2276.59     .06       0 2445.47     .07       0
#XS Ineff= 2 ,-1
       0  349.39     147 5402.88 6334.54     147
Permanent Ineff=
       F       F
Bank Sta=2276.59,2445.47
XS Rating Curve= 0 ,0
Exp/Cntr=0.3,0.1

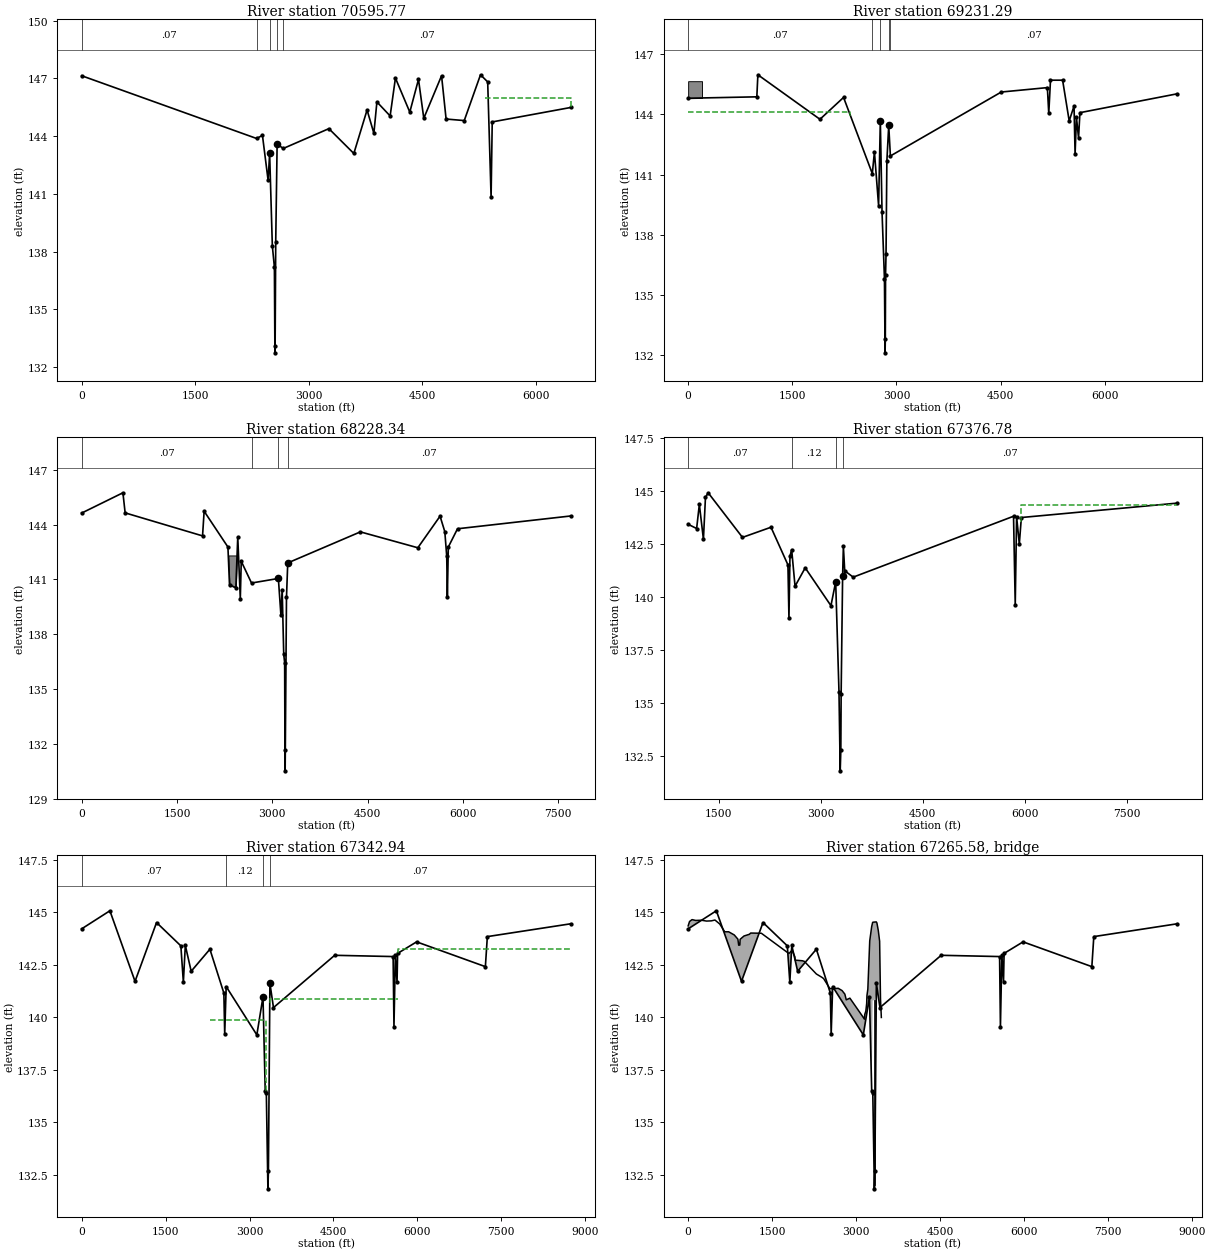
Type RM Length L Ch R = 1 ,70595.77,944.92,1364.49,1021.06
XS GIS Cut Line= 6
2988848.7062105213874467.20366312988948.5272051113873205.8662908
2988680.9798399513871975.52984072988719.8898671113871896.0798683
2987927.5052970213869196.21551742987516.2761326113868244.7535096
#Sta/Elev= 30
       0  147.14 2311.64  143.88 2389.47  144.04 2464.42   141.7  2484.4   143.1
 2520.18   138.3 2547.32  137.19 2554.15  132.74 2556.98  133.09 2564.97  138.52
 2583.35  143.59 2664.32  143.36 3267.54  144.39 3597.39   143.1 3772.31  145.36
 3862.27  144.15 3902.25  145.78 4077.17  145.05 4147.14  147.02 4337.06  145.25
 4452.01  146.95 4521.98  144.93 4756.88  147.14 4816.86  144.89 5056.75  144.81
 5271.66  147.19 5366.62  146.82  5411.6  140.83 5426.59  144.74 6463.11  145.49
#Mann= 5 ,-1 , 0
       0     .07       0 2311.64     .12       0  2484.4     .06       0
 2583.35     .12       0 2664.32     .07       0
#XS Ineff= 1 ,-1
 5331.63 6463.11     146
Permanent Ineff=
       F
Bank Sta=2484.4,2583.35
XS Rating Curve= 0 ,0
Exp/Cntr=0.3,0.1

Type RM Length L Ch R = 1 ,69231.29,789.64,1002.94,705.14
Node Name=AK
XS GIS Cut Line= 6
2989692.3275547813874494.6383195 2989621.390032613871712.0500527
2989631.9300377813871582.34001032988929.4501435313870175.1499113
2987857.8781396913868259.37519952987612.3553367713867993.0676613
#Sta/Elev= 30
       0  144.81  989.47  144.88 1004.46  145.98 1898.97  143.76 2238.78  144.85
 2653.01  141.05 2683.54  142.13 2743.51  139.45  2768.5  143.68 2793.13  139.12
 2827.88  135.81 2836.94  132.11 2840.32  132.79 2843.83  136.01 2850.67  137.05
 2862.56  141.66 2889.53  143.45 2913.41  141.93 4511.36  145.12 5174.88  145.34
 5194.83  144.05 5219.78  145.71 5394.39  145.71 5489.17  143.68 5559.02  144.42
 5573.98  142.03 5593.94  143.85 5623.87  142.83 5643.83  144.09 7043.73  145.03
#Mann= 5 ,-1 , 0
       0     .07       0 2653.01     .12       0  2768.5     .06       0
 2889.53     .12       0 2913.41     .07       0
#XS Ineff= 2 ,-1
       0 2338.73   144.1  5389.4 7043.73     145
Permanent Ineff=
       F       F
#Block Obstruct= 2 , 0
       0  199.89  145.66               0
Bank Sta=2768.5,2889.53
XS Rating Curve= 0 ,0
Exp/Cntr=0.3,0.1

Type RM Length L Ch R = 1 ,68228.34,715.69,851.57,707.96
XS GIS Cut Line= 5
 2990419.351035113874549.50796042990286.1600285313871391.8298926
2990273.9999478613871285.62997382987994.5871838613868009.1339021
2987668.0271414413867719.3477363
#Sta/Elev= 30
       0  144.63  649.07  145.74  684.02  144.64 1902.28  143.38 1927.24  144.73
 2301.71  142.77 2326.67  140.69 2426.53  140.55 2456.49  143.32 2496.43  139.94
 2511.41  141.99 2672.96   140.8 3095.57  141.05 3135.52  139.05 3155.49  140.44
 3179.92   136.9 3194.49  136.44 3199.25  131.65  3202.4  130.52 3223.28  140.01
 3243.08   141.9 4386.37   143.6 5290.58  142.73 5640.27  144.46  5715.2  143.61
 5745.18  142.27 5755.17  140.04 5770.16  142.77 5915.03  143.77 7695.45  144.47
#Mann= 4 ,-1 , 0
       0     .07       0 2672.96     .12       0 3095.57     .06       0
 3243.08     .07       0
#XS Ineff= 4 ,-1
       0 1927.24   143.7 1927.24 2611.27  139.88 3943.09 5640.27  140.88
 5640.27 7695.45  144.46
Permanent Ineff=
       F       F       F       F
#Block Obstruct= 1 ,-1
 2241.79 2456.49  142.31
Bank Sta=3095.57,3243.08
XS Rating Curve= 0 ,0
Exp/Cntr=0.3,0.1

Type RM Length L Ch R = 1 ,67376.78,10.47,33.84,113.03
Node Name=AJ
XS GIS Cut Line= 6
2990932.8378542813873427.91737682990986.2636151913872135.6824075
2991020.2300826913871259.73993372990976.9798411113871128.8701167
2988103.5262704513867887.68401382987695.8633718613867515.2175671
#Sta/Elev= 30
 1048.66  143.44  1173.5  143.24 1213.44  144.38 1273.37  142.73 1303.33  144.71
 1343.28  144.93 1847.63  142.82 2267.09   143.3 2516.32  141.52 2531.26  138.99
  2546.2  141.93 2571.11  142.24 2620.91  140.51 2770.33  141.38 3148.86  139.59
 3218.59  140.72 3267.29   135.5 3285.16  131.78  3294.2  132.75 3298.84  135.42
 3320.65     141 3331.81  142.39  3351.5  141.24 3476.33  140.94 5834.46  143.82
 5859.44  139.63 5879.42   143.8 5919.39  142.51 5949.37  143.76 8240.19  144.44
#Mann= 4 ,-1 , 0
 1048.66     .07       0 2571.11     .12       0 3218.59     .06       0
 3320.65     .07       0
#XS Ineff= 4 ,-1
       0 2267.09   143.3 2267.09 3046.89  139.88 3443.86 5944.37  140.88
 5944.37 8240.19  144.33
Permanent Ineff=
       F       F       F       F
Bank Sta=3218.59,3320.65
XS Rating Curve= 0 ,0
Exp/Cntr=0.5,0.3

Type RM Length L Ch R = 1 ,67342.94,188.93,155.96,160.25
BEGIN DESCRIPTION:
Upstream Section - PEEK ROAD
END DESCRIPTION:
XS GIS Cut Line= 6
2990912.7617936913874497.77282772991025.4393898513871283.8169853
2991026.1762650313871173.91989542991026.6634687813871101.2956968
 2988948.171234713867940.55661142987700.3089010313867005.9817089
#Sta/Elev= 30
       0  144.21  504.36  145.07  953.79  141.71 1338.31  144.51 1772.76   143.4
  1817.7  141.67 1852.66  143.42 1957.52  142.19  2292.1  143.24 2541.79  141.15
 2556.77  139.19 2583.18  141.46 3131.06  139.16 3240.93  140.97 3280.89  136.51
 3300.87  136.38    3329  131.83 3338.11  132.69 3364.58  141.62 3428.46  140.46
 4522.85  142.95 5567.28  142.89 5582.27  139.55 5607.26  142.97 5637.24  141.68
 5647.24  143.04 5987.05  143.59 7216.38  142.41 7251.36  143.84 8740.46  144.45
#Mann= 4 ,-1 , 0
       0     .07       0 2583.18     .12       0 3240.93     .06       0
 3364.58     .07       0
#XS Ineff= 4 ,-1
       0  2292.1  143.24  2292.1  3298.3  139.88 3361.78 5657.23  140.88
 5657.23 8740.46  143.24
Permanent Ineff=
       F       F       F       F
Bank Sta=3240.93,3364.58
XS Rating Curve= 0 ,0
Exp/Cntr=0.5,0.3

Type RM Length L Ch R = 3 ,67265.58,,,
BEGIN DESCRIPTION:
PEEK ROAD
END DESCRIPTION:
Node Name=PEEK ROAD
Bridge Culvert--1,0,-1,-1, 0
Deck Dist Width WeirC Skew NumUp NumDn MinLoCord MaxHiCord MaxSubmerge Is_Ogee
60,39,2.6,0, 55, 55, , , 0.98, 0, 0,0,,
       0   24.97   69.91  134.83   234.7  329.58  414.48  479.39  564.29  654.17
  724.08  823.96  888.88  903.86  923.83  928.82  998.74 1093.62 1118.58 1308.34
 1777.75 1802.72 1857.65 1907.59 1912.58 2042.42 2077.37  2292.1 2391.98 2421.94
  2531.8 2586.74 2681.62 2751.53 2801.47 2826.44 2891.35 3116.07 3151.03 3156.02
    3176 3190.98 3195.97 3211.99 3245.92 3260.91 3280.89  3298.3 3315.86 3363.07
 3374.27 3398.48 3423.01 3438.45 3453.44
  144.35  144.56  144.65  144.61  144.62  144.58  144.59  144.63  144.44  144.07
  144.07  143.92  143.72  143.43  143.44  143.71  143.87  143.95  144.01     144
  143.08  143.04  143.19  142.88  142.72  142.69  142.66  142.06   141.9  141.84
  141.37  141.36  141.38  141.27   141.1  140.83  140.91  140.05  139.91  140.13
  140.29  140.65  141.03  141.34  143.64  143.93  144.32  144.52  144.53  144.54
  144.49  144.14  143.62  140.87  139.99
       0       0       0       0       0       0       0       0       0       0
       0       0       0       0       0       0       0       0       0       0
       0       0       0       0       0       0       0       0       0       0
       0       0       0       0       0       0       0       0       0       0
       0       0       0       0       0       0       0   140.8  140.81  140.82
       0       0       0       0       0
       0   24.97   69.91  134.83   234.7  329.58  414.48  479.39  564.29  654.17
  724.08  823.96  888.88  903.86  923.83  928.82  998.74 1093.62 1118.58 1308.34
 1777.75 1802.72 1857.65 1907.59 1912.58 2042.42 2077.37  2292.1 2391.98 2421.94
  2531.8 2586.74 2681.62 2751.53 2801.47 2826.44 2891.35 3116.07 3151.03 3156.02
    3176 3190.98 3195.97 3211.99 3245.92 3260.91 3280.89  3298.3 3315.86 3363.07
 3374.27 3398.48 3423.01 3438.45 3453.44
  144.35  144.56  144.65  144.61  144.62  144.58  144.59  144.63  144.44  144.07
  144.07  143.92  143.72  143.43  143.44  143.71  143.87  143.95  144.01     144
  143.08  143.04  143.19  142.88  142.72  142.69  142.66  142.06   141.9  141.84
  141.37  141.36  141.38  141.27   141.1  140.83  140.91  140.05  139.91  140.13
  140.29  140.65  141.03  141.34  143.64  143.93  144.32  144.52  144.53  144.54
  144.49  144.14  143.62  140.87  139.99
       0       0       0       0       0       0       0       0       0       0
       0       0       0       0       0       0       0       0       0       0
       0       0       0       0       0       0       0       0       0       0
       0       0       0       0       0       0       0       0       0       0
       0       0       0       0       0       0       0  140.76  140.77  140.78
       0       0       0       0       0
Pier Skew, UpSta & Num, DnSta & Num=  ,3330.9, 2 ,3330.9, 2 , 0 , 0 , 0 ,,
     1.2     1.2
     130   141.5
     1.2     1.2
     130   141.5
Abutment Skew #Up #Dn= , 3 , 3
  3297.1  3298.1 3301.22
   140.8   140.8   139.2
  3297.1  3298.1 3301.22
  140.76  140.76  139.16
Abutment Skew #Up #Dn= , 2 , 2
 3361.56 3363.27
  140.39  140.82
 3361.56 3363.27
  140.35  140.78
BR Coef=-1 , 1 , 1 ,0.9, 0 ,,,0.8,-1,1.2,0,
WSPro=,,,, 1 ,,,, 0 ,,,, 0 ,,,,-1 ,-1 ,-1 , 0 , 0 , 0 , 0 , 0
BC Design=,, 0 ,, 0 ,,,,,,
BC Use User HTab Curves=0
BC User HTab FreeFlow(D)= 0

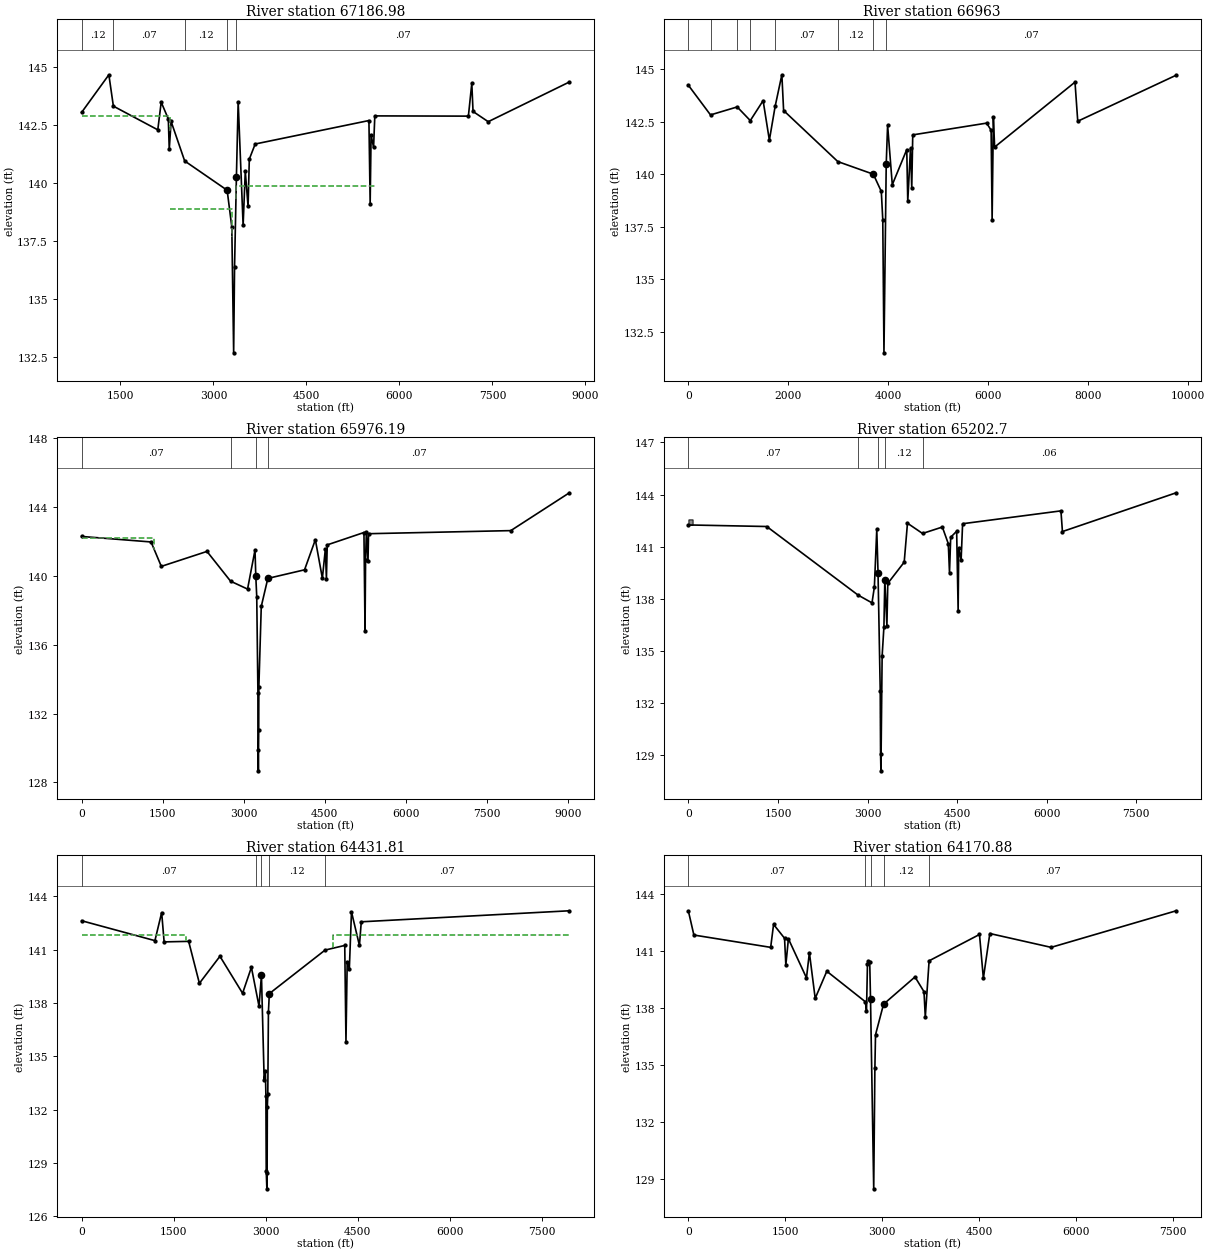
Type RM Length L Ch R = 1 ,67186.98,459.33,223.97,189.93
BEGIN DESCRIPTION:
Downstream Section - PEEK ROAD
END DESCRIPTION:
Node Name=AI
XS GIS Cut Line= 6
2991092.93078724 13873585.1021992991174.9896156913871244.4998067
2991175.7264908613871134.60271682991176.2136946213871061.9785182
2989097.7214605213867901.23943292987849.8591268713866966.6645304
#Sta/Elev= 30
  873.89  143.03 1313.34  144.65 1386.04   143.3 2102.34  142.28 2157.27  143.47
 2272.13  142.75 2287.11  141.44 2317.07  142.64 2535.93  140.94 3220.94  139.68
 3295.88   138.1 3325.85  132.68 3340.38  136.39 3370.47  140.27 3398.48  143.49
 3478.43  138.17 3513.41  140.49 3558.38  138.98 3578.37  141.02 3673.32  141.67
 5507.31  142.68  5527.3   139.1 5542.29  142.07 5582.27  141.52 5602.26  142.88
 7111.44  142.87 7166.41  144.28  7186.4  143.07 7431.25  142.63 8740.46  144.34
#Mann= 5 ,-1 , 0
  873.89     .12       0 1386.04     .07       0 2535.93     .12       0
 3220.94     .04       0 3370.47     .07       0
#XS Ineff= 4 ,-1
       0 2307.09  142.88 2307.09  3298.3  138.88 3363.07 5602.26  139.88
 5602.26 8740.46  142.88
Permanent Ineff=
       F       F       F       F
Bank Sta=3220.94,3370.47
XS Rating Curve= 0 ,0
Exp/Cntr=0.5,0.3

Type RM Length L Ch R = 1 ,66963   ,1214.05,986.82,511
XS GIS Cut Line= 6
2993039.3782753613874666.10615242991399.5200065213871155.4901422
2991368.4600292713871091.17006092991289.7200292813870942.5601218
2989421.3500783613868017.18014592987793.4386360213866575.4888035
#Sta/Elev= 30
       0  144.24  442.26  142.83  976.19  143.21  1238.2  142.56  1494.9  143.51
 1619.89  141.63 1735.63  143.24 1869.87  144.74 1904.87  143.04 2989.65  140.61
 3699.73  140.01 3859.72  139.19    3889  137.85 3912.81  131.51 3958.16   140.5
 3985.71  142.34  4079.7  139.51 4369.04  141.18 4389.02  138.72 4443.96  141.24
 4468.93  139.36  4488.9  141.88 5967.25  142.44 6057.15   142.1 6077.13  137.84
  6102.1  142.72 6127.08   141.3 7735.42  144.39 7790.41  142.53 9760.02  144.72
#Mann= 8 ,-1 , 0
       0     .07       0  442.26     .12       0  976.19     .07       0
  1238.2     .12       0 1735.63     .07       0 2989.65     .12       0
 3699.73     .04       0 3958.16     .07       0
#XS Ineff= 3 ,-1
       0 1869.87  142.72 4228.54  6102.1     140  6102.1 9760.02  142.72
Permanent Ineff=
       F       F       F
Bank Sta=3699.73,3958.16
XS Rating Curve= 0 ,0
Exp/Cntr=0.3,0.1

Type RM Length L Ch R = 1 ,65976.19,500.15,773.49,809.59
XS GIS Cut Line= 6
2994983.9445961913871813.63711992992308.4299341113870649.8599198
 2991881.620092213870697.05995672991618.8837410213870635.0728759
2989836.20325127 13867975.2005712988154.0140303713866591.8785345
#Sta/Elev= 30
       0   142.3 1284.68  141.98 1474.63  140.56 2319.42  141.43 2755.68   139.7
 3070.35  139.24 3208.23  141.51    3223  139.98 3240.22   138.8 3262.18  133.21
 3265.93   129.9  3270.1  128.67  3276.8  131.07 3279.27  133.52 3324.06  138.23
 3445.48  139.86 4124.99  140.36 4324.81  142.11  4454.7  139.87 4509.65  141.56
 4529.63  139.85 4544.61  141.81    5224  142.53 5243.98   136.8 5253.97  140.93
 5268.96  142.57 5298.93  140.88 5308.92  142.46 7941.45  142.64 9025.39  144.84
#Mann= 4 ,-1 , 0
       0     .07       0 2755.68     .12       0    3223     .06       0
 3445.48     .07       0
#XS Ineff= 2 ,-1
       0 1344.66  142.19 5318.91 9025.39  142.19
Permanent Ineff=
       F       F
Bank Sta=3223,3445.48
XS Rating Curve= 0 ,0
Exp/Cntr=0.3,0.1

Type RM Length L Ch R = 1 ,65202.7 ,648.6,770.88,561.9
XS GIS Cut Line= 5
2995018.7719543613871395.70980612993590.2498770213870717.3099162
2991278.7499068513869626.81012872990110.4677946113867978.4518768
2988658.8201073613866588.6006539
#Sta/Elev= 30
       0  142.25 1312.03  142.16 2839.37  138.22 3073.99  137.77 3113.92  138.68
 3153.86  141.99 3175.05 139.504 3211.97  132.69 3217.44   129.1 3223.52  128.11
 3243.71  134.71 3273.66  136.39 3288.64  139.09 3323.58  136.45 3338.56  138.89
 3613.11  140.11 3668.02  142.35 3920.24  141.76 4251.99  142.13 4351.76  141.17
 4371.72  139.49 4391.67  141.54 4491.44  141.89 4516.39  137.33 4526.36  140.91
 4566.27  140.24 4591.21  142.32 6237.63  143.06 6262.62  141.87 8167.35   144.1
#Mann= 5 ,-1 , 0
       0     .07       0 2839.37     .12       0 3175.05     .06       0
 3288.64     .12       0 3920.24     .06       0
#XS Ineff= 2 ,-1
       0 1436.75  141.75 4242.01 8167.35  141.75
Permanent Ineff=
       F       F
#Block Obstruct= 2 , 0
       0   69.84  142.57               0
Bank Sta=3175.05,3288.64
XS Rating Curve= 0 ,0
Exp/Cntr=0.3,0.1

Type RM Length L Ch R = 1 ,64431.81,123.53,260.93,201.71
XS GIS Cut Line= 6
2995049.4634940313871040.25382412992926.9723321913869683.0104756
 2992534.606975213869575.77643812991392.3536822813869534.3460748
2990429.2657134413868007.43344622988911.2228177813866591.8785345
#Sta/Elev= 30
       0  142.63 1194.69  141.51 1304.66  143.09 1344.65  141.44 1744.54  141.47
  1919.5  139.11 2254.41  140.63 2623.52  138.55 2767.37  140.01 2891.38  137.82
 2931.04  139.57 2975.48  133.66 2995.24  134.19 3003.61  132.77 3008.94  128.54
 3019.37  127.55 3023.37  128.43 3026.67  132.14 3034.32  132.88 3044.64  137.49
 3059.43  138.53 3968.47  140.98 4288.62  141.24 4308.57  135.83 4328.51  140.31
 4363.42  139.92 4398.33  143.13    4528  141.24 4557.92  142.57 7950.11  143.19
#Mann= 5 ,-1 , 0
       0     .07       0 2849.61     .12       0 2931.04     .06       0
 3059.43     .12       0 3968.47     .07       0
#XS Ineff= 2 ,-1
       0 1694.55  141.81 4094.12 7950.11  141.81
Permanent Ineff=
       F       F
Bank Sta=2931.04,3059.43
XS Rating Curve= 0 ,0
Exp/Cntr=0.3,0.1

Type RM Length L Ch R = 1 ,64170.88,146.65,71.79,22.64
Node Name=AH
XS GIS Cut Line= 6
2995057.2994363613870907.03952362992604.65998469 13869388.189871
2992172.99450944 13869387.8276672991694.7966469413869229.4920257
2990670.7793380313868026.75460182989071.4472348513866602.6232637
#Sta/Elev= 30
       0  143.12   84.94  141.86 1274.08  141.21 1319.05  142.42 1488.92  141.69
 1508.91  140.28 1548.88  141.66 1828.68   139.6 1873.64  140.93 1963.58  138.52
 2143.45  139.95 2740.54  138.34 2758.15  137.85 2773.15  140.34 2788.14  140.49
 2808.13  140.44  2820.5  138.47 2870.04  128.47    2888  134.82 2897.98   136.6
 3022.02  138.21  3509.2  139.65 3648.84  138.87 3668.79  137.53 3727.78   140.5
 4508.21  141.89  4568.2  139.58 4668.17  141.94 5617.64  141.21  7554.5  143.14
#Mann= 5 ,-1 , 0
       0     .07       0 2740.54     .12       0  2820.5     .06       0
 3022.02     .12       0 3727.78     .07       0
#XS Ineff= 2 ,-1
       0 1548.88  141.66 4508.21  7554.5  141.66
Permanent Ineff=
       F       F
Bank Sta=2820.5,3022.02
XS Rating Curve= 0 ,0
Exp/Cntr=0.5,0.3

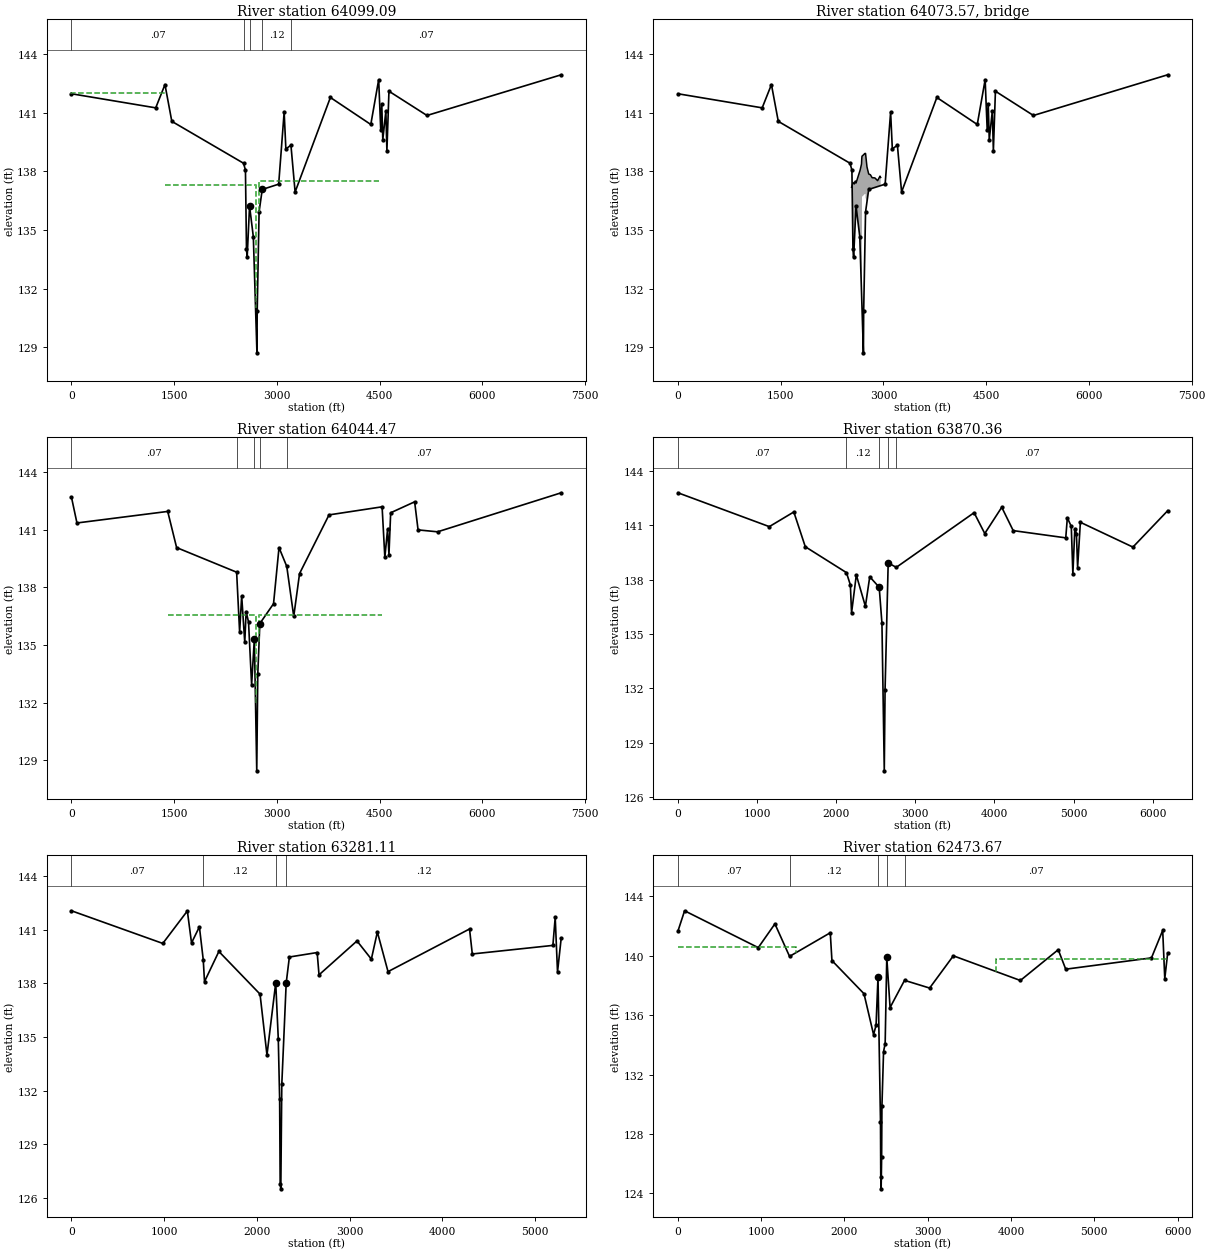
Type RM Length L Ch R = 1 ,64099.09,61.01,54.62,62.79
BEGIN DESCRIPTION:
Upstream Section - STOCKDICK SCHOOL RD
END DESCRIPTION:
XS GIS Cut Line= 5
2995032.3539481913870674.94385922992834.1112974413869382.5704597
2992684.1407968613869379.59966512992434.3141967813869370.2929252
2989259.5800606913866620.5543302
#Sta/Elev= 30
       0  141.96    1230  141.24    1365  142.43    1465  140.55 2511.68  138.41
    2540  138.06    2555  134.01    2565  133.61    2600  136.22    2655  134.65
 2707.82  128.72 2711.65  130.87 2739.08  135.92    2785  137.07    3025  137.34
    3105  141.02    3130  139.14 3204.09  139.33    3265  136.94 3780.01  141.77
 4370.02  140.39 4485.02  142.68 4515.02  140.12 4530.02  141.45 4545.02  139.61
 4590.02  141.08 4605.02  139.04 4635.02  142.09 5190.01  140.85    7150  142.93
#Mann= 5 ,-1 , 0
       0     .07       0 2511.68     .12       0    2600     .06       0
    2785     .12       0 3204.09     .07       0
#XS Ineff= 4 ,-1
       0    1365     142    1365 2687.21  137.28 2739.05 4485.02  137.52
 4485.02    7150     142
Permanent Ineff=
       F       F       F       F
Bank Sta=2600,2785
XS Rating Curve= 0 ,0
Exp/Cntr=0.5,0.3

Type RM Length L Ch R = 3 ,64073.57,,,
BEGIN DESCRIPTION:
STOCKDICK SCHOOL RD
END DESCRIPTION:
Node Name=STOCKDICK SCHOOL
Bridge Culvert--1,0,-1,-1, 0
Deck Dist Width WeirC Skew NumUp NumDn MinLoCord MaxHiCord MaxSubmerge Is_Ogee
13,29,2.6,0, 22, 22, , , 0.98, 0, 0,0,,
    2535    2555    2575    2590    2600    2660    2680 2683.51 2687.21    2700
    2710    2720    2730 2739.05    2760    2785    2810    2835    2875    2915
    2950    2960
  137.18  137.43  137.35   137.5   137.4  138.06  138.37  138.64  138.77  138.81
  138.84  138.88  138.91  138.91  138.22  137.86  137.82  137.67  137.66  137.52
  137.75  137.68
       0       0       0       0       0       0       0       0   136.7  136.74
  136.77  136.81  136.84  136.84       0       0       0       0       0       0
       0       0
    2535    2555    2575    2590    2600    2660    2680 2683.51 2687.21    2700
    2710    2720    2730 2739.05    2760    2785    2810    2835    2875    2915
    2950    2960
  137.18  137.43  137.35   137.5   137.4  138.06  138.37  138.64  138.77  138.81
  138.84  138.88  138.91  138.91  138.22  137.86  137.82  137.67  137.66  137.52
  137.75  137.68
       0       0       0       0       0       0       0       0  136.78  136.82
  136.85  136.89  136.92  136.92       0       0       0       0       0       0
       0       0
Abutment Skew #Up #Dn= , 2 , 2
 2687.01 2689.72
   136.7  134.14
 2687.01 2689.72
  136.78  134.22
BR Coef=-1 , 0 , 0 ,, 0 ,,,0.8,-1,,0,
WSPro=,,,, 1 ,,,, 0 ,,,, 0 ,,,,-1 ,-1 ,-1 , 0 , 0 , 0 , 0 , 0
BC Design=,, 0 ,, 0 ,,,,,,
BC Use User HTab Curves=0
BC User HTab FreeFlow(D)= 0

Type RM Length L Ch R = 1 ,64044.47,62.25,174.11,330.75
BEGIN DESCRIPTION:
Downstream Section - STOCKDICK SCHOOL RD
END DESCRIPTION:
XS GIS Cut Line= 5
2995056.3627584413870625.8822775 2992858.1201077 13869333.508878
2992708.1496071113869330.53808342992458.3230070313869321.2313435
2989283.5888709413866571.4927485
#Sta/Elev= 30
       0  142.69      80  141.35    1405  141.95    1535  140.07 2411.27  138.79
    2455  135.67    2485  137.55    2530  135.14    2550  136.74    2585   136.2
    2630  132.93    2670  135.33    2705  128.46    2720  133.49    2750  136.12
    2950  137.15    3030  140.07  3143.2  139.09    3245  136.49    3330  138.72
 3760.01  141.77 4535.02  142.19 4575.02  139.56 4615.02  141.03 4635.02  139.71
 4660.02  141.88 5010.01  142.45 5060.01  140.99 5345.01  140.89 7149.99  142.92
#Mann= 5 ,-1 , 0
       0     .07       0 2411.27     .12       0    2670     .06       0
    2750     .12       0  3143.2     .07       0
#XS Ineff= 4 ,-1
       0    1405  141.95    1405 2687.21  136.55 2739.05 4535.02  136.55
 4535.02 7149.99  141.95
Permanent Ineff=
       F       F       F       F
Bank Sta=2670,2750
XS Rating Curve= 0 ,0
Exp/Cntr=0.5,0.3

Type RM Length L Ch R = 1 ,63870.36,552.12,589.25,587.46
Node Name=AG
XS GIS Cut Line= 6
2995076.6501194413870549.97002782993441.58646044 13869451.937775
2992920.4198518513869311.85012872992787.5999075313869186.2798418
2992225.9100860213868443.50015942990406.6315723713866632.8545024
#Sta/Elev= 30
       0   142.8 1154.73  140.93 1464.66  141.74 1609.63  139.82 2129.67  138.39
 2179.42  137.71 2194.41  136.16 2254.37  138.26  2369.3  136.53 2424.27  138.16
  2543.8  137.58 2578.38   135.6 2608.02  127.44  2617.9  131.92 2657.42  138.93
 2759.34  138.68  3743.1   141.7 3877.93  140.55 4092.67     142 4237.48  140.71
 4901.64  140.31 4921.61  141.42 4971.55  140.94 4991.53  138.31 5016.49  140.82
 5036.47  140.55 5051.45  138.67  5086.4  141.17 5750.56   139.8    6190  141.81
#Mann= 5 ,-1 , 0
       0     .07       0 2129.67     .12       0  2543.8     .06       0
 2657.42     .12       0 2759.34     .07       0
#XS Ineff= 2 ,-1
       0 1464.66  141.74 4921.61    6190  141.42
Permanent Ineff=
       F       F
Bank Sta=2543.8,2657.42
XS Rating Curve= 0 ,0
Exp/Cntr=0.3,0.1

Type RM Length L Ch R = 1 ,63281.11,819.84,807.44,574.25
XS GIS Cut Line= 5
2995074.9713170213870296.76876252993741.3499685213869259.7698523
2993344.1201199413868950.80984032993260.6101163613868817.8599749
2991255.8749526113866679.4731756
#Sta/Elev= 30
       0  142.07  984.62  140.24 1249.52  142.06  1294.5  140.27 1379.47  141.17
    1421  139.32 1434.45   138.1 1589.39  139.79 2033.15   137.4 2107.89  133.99
 2202.41  138.03 2229.83  134.91 2244.62   131.5 2250.18  126.77 2257.22  126.49
 2267.82  132.34 2315.25  138.02 2349.59  139.48  2649.2  139.73 2669.18  138.48
 3078.64  140.38 3233.44  139.36 3298.35  140.88  3413.2  138.66 4292.04  141.05
 4322.01  139.65 5190.85  140.13 5215.81   141.7 5240.78  138.64 5280.73  140.55
#Mann= 4 ,-1 , 0
       0     .07       0    1421     .12       0 2202.41     .06       0
 2315.25     .12       0
#XS Ineff= 2 ,-1
       0 1589.39  139.79 3298.25 5280.73   139.7
Permanent Ineff=
       F       F
#Block Obstruct= 2 , 0
       0                 5215.81       0   141.7
Bank Sta=2202.41,2315.25
XS Rating Curve= 0 ,0
Exp/Cntr=0.3,0.1

Type RM Length L Ch R = 1 ,62473.67,351.42,360.69,312.31
XS GIS Cut Line= 4
2995729.2807039513870395.47952312994056.4165956113868703.3260833
2993916.4578860313868618.89318132991261.0170026913866594.4142906
#Sta/Elev= 30
       0  141.65   79.98  143.02  964.78  140.54 1164.74  142.14 1340.53  139.95
 1829.59  141.54 1849.59  139.67  2234.5  137.44 2349.48  134.69 2379.47  135.31
 2402.76  138.55 2432.76  128.83 2435.95  125.09 2440.65  124.31 2446.37  126.42
 2450.08  129.87  2469.6  133.55 2488.78  134.08 2508.25  139.88 2547.92  136.51
 2721.52  138.34 3022.81  137.82 3307.74  139.99 4112.54  138.33 4567.42   140.4
 4657.39  139.09 5687.11  139.85 5822.08   141.7 5847.07  138.45 5882.06  140.19
#Mann= 5 ,-1 , 0
       0     .07       0 1340.53     .12       0 2402.76     .06       0
 2508.25     .12       0 2721.52     .07       0
#XS Ineff= 2 ,-1
       0 1419.68  140.61 3822.61 5882.06   139.8
Permanent Ineff=
       F       F
#Block Obstruct= 2 , 0
       0                 5822.08       0   141.7
Bank Sta=2402.76,2508.25
XS Rating Curve= 0 ,0
Exp/Cntr=0.3,0.1