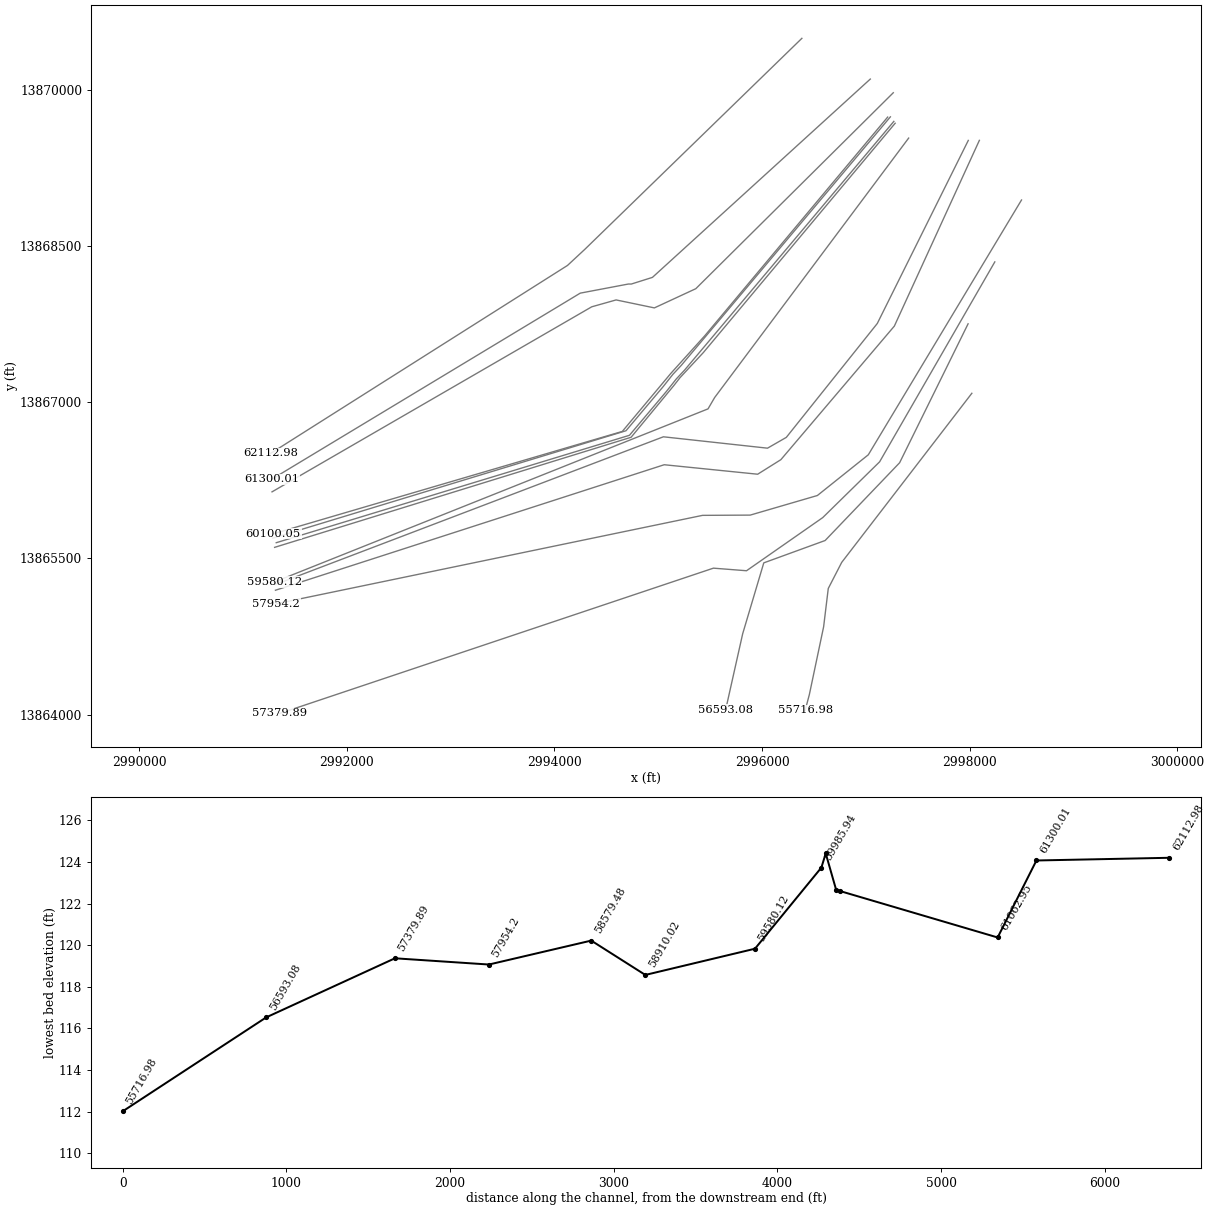
HEC-RAS study U101-00-00.prj: U101-00-00 2019 (Re-Study)

--- U101-00-00.g01 (geometry) --- (continued)

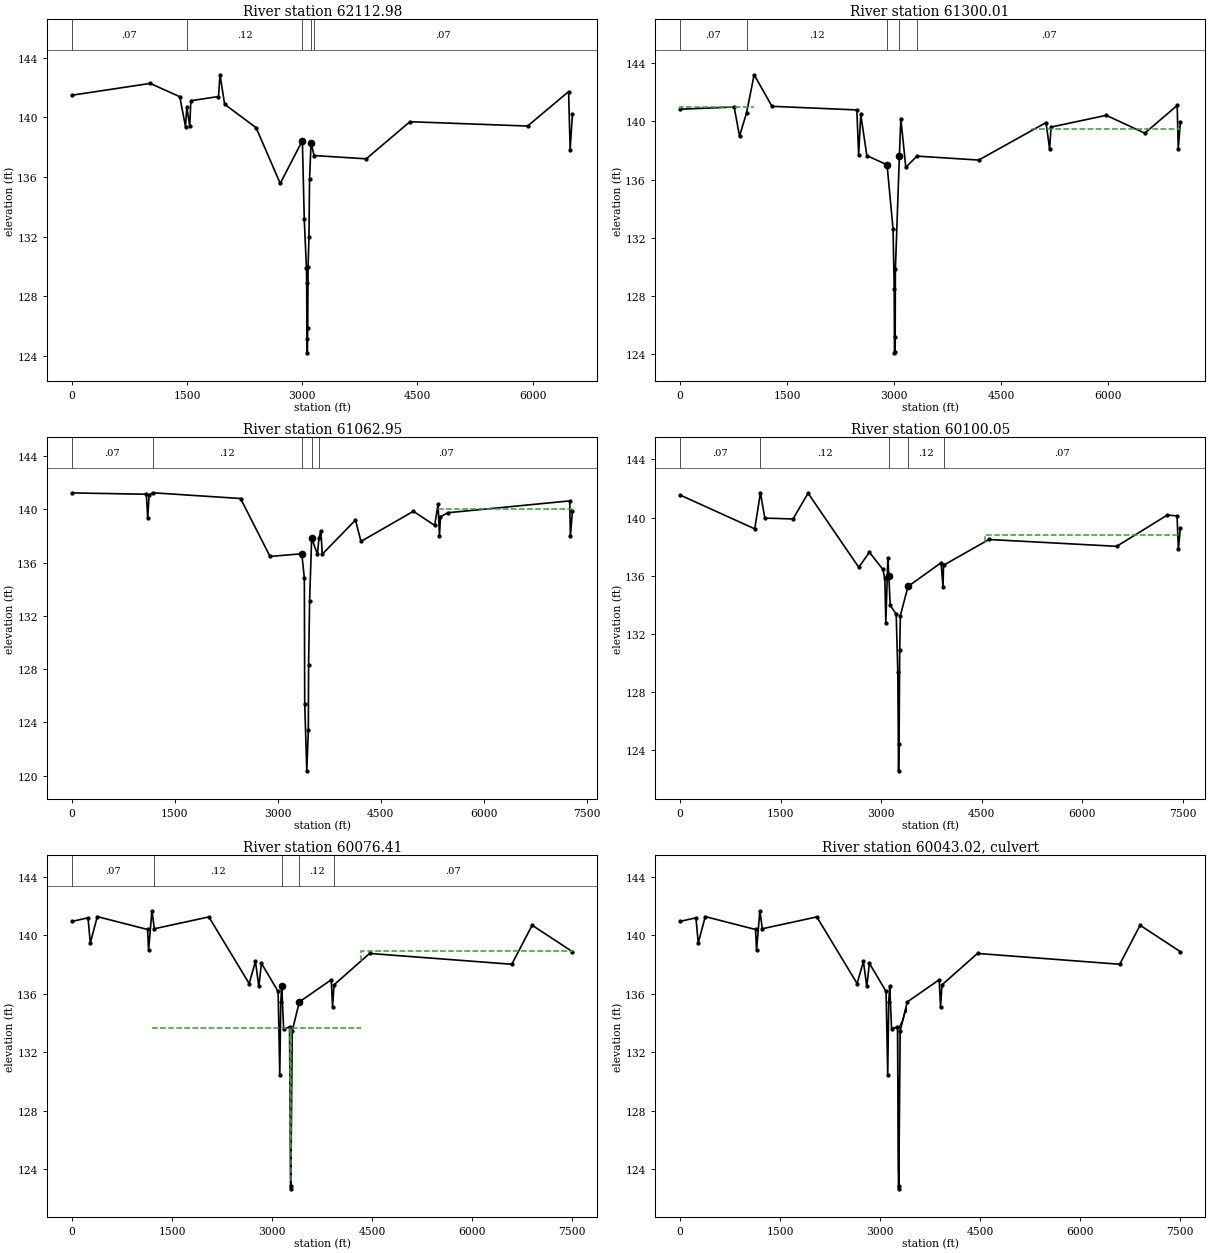
Type RM Length L Ch R = 1 ,62112.98,808.7,812.97,364.42
XS GIS Cut Line= 4
2996383.5900908613870494.18995562994291.4699312713868467.4400721
2994125.3600272813868313.4800782 2991266.158724713866509.3554056
#Sta/Elev= 30
       0  141.49 1019.25  142.28 1403.96  141.39 1478.91  139.38 1496.08  140.69
 1533.87  139.43 1548.86  141.12 1908.59   141.4 1928.58  142.86 1988.54  140.88
 2398.24  139.31 2713.01  135.57 3001.49  138.44  3026.1  133.18 3054.47  129.89
 3057.52  128.89 3060.78  125.14 3065.82   124.2 3071.25  125.88 3075.73  129.94
 3087.26  131.95 3095.03  135.87 3114.73   138.3 3153.99  137.44 3833.49  137.22
 4402.79  139.71  5935.9  139.42 6470.25  141.73 6490.22  137.83 6520.19  140.21
#Mann= 5 ,-1 , 0
       0     .07       0 1496.08     .12       0 3001.49     .06       0
 3114.73     .12       0 3153.99     .07       0
#XS Ineff= 2 ,-1
       0 1673.77     141 4402.79 6520.19   139.5
Permanent Ineff=
       F       F
#Block Obstruct= 2 , 0
       0                 6470.25       0  141.73
Bank Sta=3001.49,3114.73
XS Rating Curve= 0 ,0
Exp/Cntr=0.3,0.1

Type RM Length L Ch R = 1 ,61300.01,287.95,237.07,166.14
Node Name=AF
XS GIS Cut Line= 6
2997042.9283391113870103.18417592994943.7235480213868198.7647564
2994740.14587119 13868134.8144252994711.9999301113868135.0001202
2994248.1691648713868047.44878612991277.24925369 13866261.424471
#Sta/Elev= 30
       0  140.84  759.82  140.99   834.8  138.99  934.45  140.61 1039.76  143.21
  1289.7  141.04 2479.42  140.79 2504.41  137.66  2534.4  140.48 2619.38  137.65
 2902.78  137.01 2986.94  132.58 3003.29  128.45 3006.68  124.07 3014.44  124.16
 3016.66  125.16 3019.61  129.82  3075.6  137.62 3095.77   140.2 3165.34  136.84
 3321.84  137.61 4187.27  137.34 5131.27  139.92 5181.22   138.1  5201.2  139.61
 5975.38  140.42 6514.81  139.19 6969.33   141.1 6984.32  138.12 7014.29  139.98
#Mann= 5 ,-1 , 0
       0     .07       0  934.45     .12       0 2902.78     .06       0
  3075.6     .12       0 3321.84     .07       0
#XS Ineff= 2 ,-1
       0 1039.76     141 4936.48 7014.29   139.5
Permanent Ineff=
       F       F
#Block Obstruct= 2 , 0
       0                 6969.33       0   141.1
Bank Sta=2902.78,3075.6
XS Rating Curve= 0 ,0
Exp/Cntr=0.3,0.1

Type RM Length L Ch R = 1 ,61062.95,653.96,962.89,1276.59
XS GIS Cut Line= 6
2997264.4646414413869971.80714212995361.6521741213868090.1996849
2994962.3468703613867905.73811152994593.6901273613867982.2999663
2994358.7001117813867916.16984922991278.1918371213866139.3282585
#Sta/Elev= 30
       0  141.24 1083.39  141.14 1103.36  139.32 1123.33  141.08 1176.84  141.25
 2456.35  140.82 2885.95  136.47 3348.64  136.67 3385.87  134.85 3391.33  125.41
 3421.54  120.37 3443.74   123.4 3447.77  128.29 3462.65  133.15 3492.39  137.85
 3577.09  136.62 3599.02  137.87 3626.91  138.41 3646.84  136.64 4131.09   139.2
 4211.01   137.6  4975.2  139.86 5284.87   138.8 5334.82  140.38  5354.8  138.03
 5369.78  139.44 5474.67  139.75 7252.79  140.64 7262.78  137.98 7292.75   139.9
#Mann= 5 ,-1 , 0
       0     .07       0 1176.84     .12       0 3348.64     .06       0
 3492.39     .12       0 3599.02     .07       0
#XS Ineff= 2 ,-1
       0  1143.3     140 5334.82 7292.75     140
Permanent Ineff=
       F       F
#Block Obstruct= 2 , 0
       0                 7252.79       0  140.64
Bank Sta=3348.64,3492.39
XS Rating Curve= 0 ,0
Exp/Cntr=0.3,0.1

Type RM Length L Ch R = 1 ,60100.05,20.65,23.65,26.99
XS GIS Cut Line= 6
2997210.30595711 13869737.8781482995449.0401226913867639.2701405
2995121.2212245313867277.1015735 2995081.635017613867229.7913007
2994653.3199293613866719.43995922991290.8965361113865736.5455995
#Sta/Elev= 30
       0  141.56  1114.9  139.23 1199.63  141.71 1264.88  139.97 1684.85  139.91
 1909.83  141.68 2664.75  136.59 2824.48  137.62 3023.87  136.45 3053.77  135.82
 3068.73  132.75 3098.64  137.26 3113.59  136.02 3133.53  133.98 3223.25  133.37
 3247.22  129.39 3258.48   122.6 3266.16  124.45 3275.69  130.91 3285.18  133.27
 3399.31  135.27 3891.56   136.9 3921.39  135.24 3928.72  136.73 4605.86   138.5
 6509.88  138.03 7264.49  140.18 7409.42  140.12 7429.41  137.83 7459.39   139.3
#Mann= 5 ,-1 , 0
       0     .07       0 1199.63     .12       0 3113.59     .06       0
 3399.31     .12       0 3928.72     .07       0
#XS Ineff= 2 ,-1
       0 1174.89     140 4550.89 7459.39  138.84
Permanent Ineff=
       F       F
#Block Obstruct= 2 , 0
       0                 7409.42       0  140.12
Bank Sta=3113.59,3399.31
XS Rating Curve= 0 ,0
Exp/Cntr=0.5,0.3

Type RM Length L Ch R = 1 ,60076.41,54.67,63.98,60.48
BEGIN DESCRIPTION:
Upstream Section - 78" CULVERT
END DESCRIPTION:
XS GIS Cut Line= 6
2997236.4505898713869740.29907492995220.2653177813867352.3084441
2995140.9731535313867267.88899352995046.4431588713867149.0247299
2994688.9163148613866726.12892222991285.5231872813865694.6956176
#Sta/Elev= 30
       0  140.95  239.64   141.2  274.59  139.48  379.43  141.28  1133.3   140.4
 1148.27  138.97  1198.2  141.68 1234.74  140.45 2051.91  141.26 2655.99   136.7
 2750.85  138.21 2800.77   136.5 2840.71  138.08 3090.33  136.16  3115.3  130.45
 3130.11  135.42 3144.58   136.5 3173.54  133.56 3261.38  133.74 3277.02  122.65
 3281.06  122.86 3301.92  133.46 3407.96  135.44 3886.91  136.96 3906.86   135.1
 3928.33  136.61 4461.24  138.76    6594  138.02 6898.68  140.69 7503.05  138.88
#Mann= 5 ,-1 , 0
       0     .07       0 1234.74     .12       0 3144.58     .06       0
 3407.96     .12       0 3928.33     .07       0
#XS Ineff= 4 ,-1
       0  1198.2     140  1198.2 3273.17  133.64 3281.67 4336.37  133.63
 4336.37 7503.05  138.91
Permanent Ineff=
       F       F       F       F
#Block Obstruct= 2 , 0
       0                 7433.12       0  139.83
Bank Sta=3144.58,3407.96
XS Rating Curve= 0 ,0
Exp/Cntr=0.5,0.3

Type RM Length L Ch R = 2 ,60043.02,,,
BEGIN DESCRIPTION:
78" CULVERT
END DESCRIPTION:
Node Name=78" CULVERT
Bridge Culvert--1,0,-1,-1, 0
Deck Dist Width WeirC Skew NumUp NumDn MinLoCord MaxHiCord MaxSubmerge Is_Ogee
15,33,2.6,0, 15, 15, , , 0.98, 0, 0,0,,
 3197.67  3221.8 3231.45 3236.27 3250.79 3265.32 3279.85 3289.81 3299.76 3304.74
 3314.62 3329.32 3339.11  3388.1    3393
  133.68  133.67  133.69   133.7  133.73  133.65  133.63  133.72  133.81  133.86
  133.95  134.12  134.14  135.01  134.76
       0       0       0       0       0       0       0       0       0       0
       0       0       0       0       0
 3197.67  3221.8 3231.45 3236.27 3250.79 3265.32 3279.85 3289.81 3299.76 3304.74
 3314.62 3329.32 3339.11  3388.1    3393
  133.68  133.69   133.7  133.71  133.74  133.57   133.7   133.8  133.89  133.94
  134.04  134.12  134.14  135.01  134.76
       0       0       0       0       0       0       0       0       0       0
       0       0       0       0       0
BR Coef=-1 , 0 , 0 ,, 0 ,,,0.8,-1,,0,
WSPro=,,,, 1 ,,,, 0 ,,,, 0 ,,,,-1 ,-1 ,-1 , 0 , 0 , 0 , 0 , 0
Culvert=1,6.5,,33,0.013,0.5,1,1,3,123.77,3277.42,124.41,3268.82,Culvert #1  , 0 ,15
Culvert Bottom n=0.013
BC Design=,, 0 ,, 0 ,,,,,,
BC Use User HTab Curves=0
BC User HTab FreeFlow(D)= 0

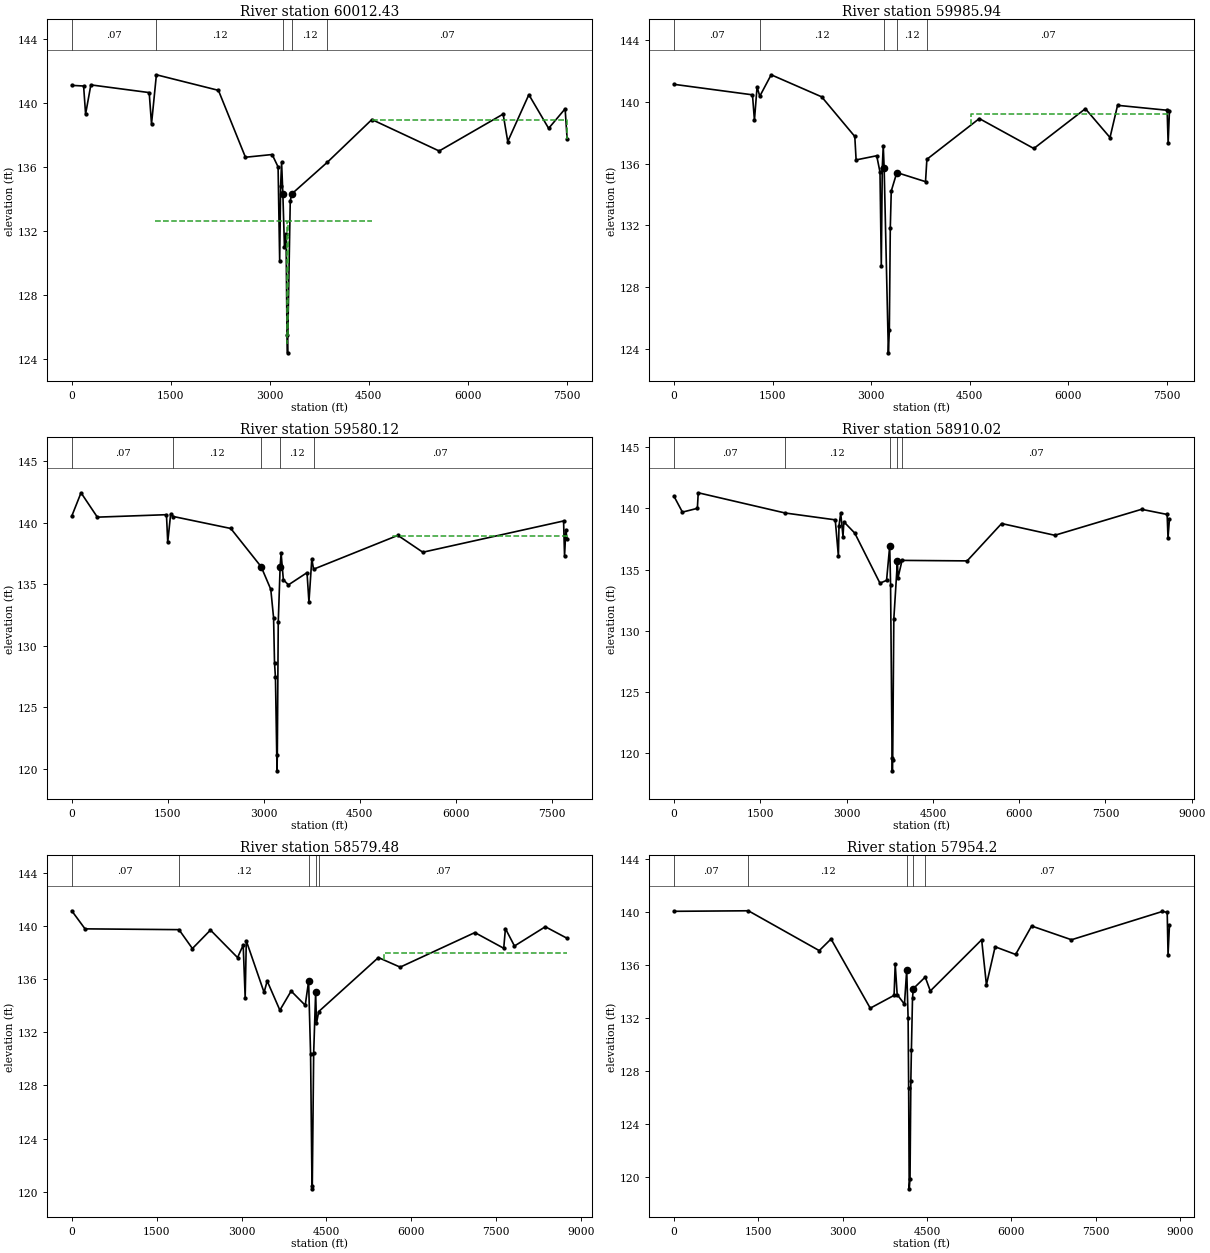
Type RM Length L Ch R = 1 ,60012.43,23.23,26.49,21.6
BEGIN DESCRIPTION:
Downstream Section - 78" CULVERT
END DESCRIPTION:
XS GIS Cut Line= 6
2997269.7710612713869696.60788942995253.5857891913867308.6172585
2995174.2936249413867224.19780792995079.7636302713867105.3335444
2994722.2367862813866682.4377366 2991318.8436587 13865651.004432
#Sta/Elev= 30
       0  141.08  179.73  141.04  209.68  139.29  289.56  141.11 1173.24  140.63
 1208.18  138.67 1282.03  141.74 2221.65  140.77 2631.03   136.6 3035.42  136.77
 3125.28     136 3149.41  130.14 3163.89   134.8 3178.36  136.29 3197.67  134.32
  3221.8  130.99 3245.94  131.84 3260.47   125.5 3268.42  124.41 3309.72  133.89
 3334.21  134.32 3871.96  136.29 4546.15  138.95 5565.08  136.99 6534.07  139.29
 6603.99  137.58 6923.66   140.5 7223.34   138.4 7473.08  139.62 7503.05  137.76
#Mann= 5 ,-1 , 0
       0     .07       0 1282.03     .12       0 3197.67     .06       0
 3334.21     .12       0 3871.96     .07       0
#XS Ineff= 4 ,-1
       0 1268.09     140 1268.09 3264.57  132.64 3273.07 4546.15  132.63
 4546.15 7503.05  138.95
Permanent Ineff=
       F       F       F       F
#Block Obstruct= 2 , 0
       0                 7473.08       0  139.62
Bank Sta=3197.67,3334.21
XS Rating Curve= 0 ,0
Exp/Cntr=0.5,0.3

Type RM Length L Ch R = 1 ,59985.94,370.68,405.83,285
Node Name=AE
XS GIS Cut Line= 6
2997282.6791719513869678.96980132995433.9801134513867476.5798491
2995210.0488027813867236.54981742995150.1867177813867160.2737232
2994738.17999586 13866663.4000452991303.1025484513865606.3473691
#Sta/Elev= 30
       0  141.14 1193.11  140.46 1223.06  138.81    1263  140.97 1304.44  140.37
 1477.66  141.76 2246.44  140.33 2750.66  137.76 2770.63  136.24 3084.36  136.51
  3134.1  135.45 3153.99  129.38 3168.92  135.74 3183.84  137.17 3197.45  135.73
 3261.91  123.73 3276.45   125.2    3291  131.85 3305.67  134.22 3390.36  135.42
 3827.22  134.83 3848.04  136.28 4645.99  138.92 5475.76  136.98 6260.53  139.56
 6635.43  137.69  6750.4  139.78 7505.18  139.46 7520.18  137.31 7540.17  139.41
#Mann= 5 ,-1 , 0
       0     .07       0 1304.44     .12       0 3197.45     .06       0
 3390.36     .12       0 3848.04     .07       0
#XS Ineff= 2 ,-1
       0 1272.98   139.2 4521.03 7540.17   139.2
Permanent Ineff=
       F       F
#Block Obstruct= 2 , 0
       0                 7505.18       0  139.46
Bank Sta=3197.45,3390.36
XS Rating Curve= 0 ,0
Exp/Cntr=0.3,0.1

Type RM Length L Ch R = 1 ,59580.12,839.8,670.1,321.12
XS GIS Cut Line= 4
2997412.4876393713869536.34607082995543.3699865313867045.3799241
2995479.4498387713866936.18985382991300.1639060213865273.3933106
#Sta/Elev= 30
       0  140.52  144.96  142.42   399.9  140.44 1479.64  140.64 1499.64  138.41
 1544.63  140.67 1589.29  140.49  2484.4  139.52 2959.28  136.41 3109.24  134.58
 3153.17  132.27 3167.77   128.6 3182.37  127.42  3206.7  119.83 3211.57  121.15
 3226.17   131.9 3255.76  136.43 3270.75  137.52 3305.74  135.35  3385.7  134.94
 3675.57  135.93 3705.56  133.54 3750.54  137.05 3777.85  136.21 5094.92  138.96
 5484.75  137.59 7683.74  140.13 7698.73  137.26 7718.72  139.38 7738.71  138.67
#Mann= 5 ,-1 , 0
       0     .07       0 1589.29     .12       0 2959.28     .06       0
 3255.76     .12       0 3777.85     .07       0
#XS Ineff= 2 ,-1
       0 1544.63  138.87 5019.96 7738.71  138.87
Permanent Ineff=
       F       F
#Block Obstruct= 2 , 0
       0                 7683.74       0  140.13
Bank Sta=2959.28,3255.76
XS Rating Curve= 0 ,0
Exp/Cntr=0.3,0.1

Type RM Length L Ch R = 1 ,58910.02,277.49,330.54,369.16
XS GIS Cut Line= 6
2997987.1442984513869514.00523622997110.4081910313867756.1928069
2996233.6720836213866662.44269792996052.4654250313866558.7581939
 2995049.304701713866667.99222742991311.79708485   13865249.6824
#Sta/Elev= 30
       0  140.97  144.95  139.69  404.86     140  419.86  141.27 1930.44  139.62
 2802.39  139.06 2857.27  136.08 2867.24  138.56 2897.18  139.61 2937.08   137.7
 2952.05   138.9 3141.61  137.98 3579.86  133.89 3694.76  134.12 3749.52  136.93
 3764.41  133.75 3790.82  119.58 3795.39  118.57 3801.17  119.49 3821.04  130.99
 3883.35  135.68 3893.27  134.32 3964.05  135.75 5095.83  135.71 5695.47  138.76
 6619.92   137.8 8129.03  139.92 8573.77   139.5 8588.76  137.58 8613.75  139.14
#Mann= 5 ,-1 , 0
       0     .07       0 1930.44     .12       0 3749.52     .06       0
 3883.35     .12       0 3964.05     .07       0
#XS Ineff= 2 ,-1
       0 2897.18   138.5 5695.47 8613.75   138.5
Permanent Ineff=
       F       F
#Block Obstruct= 2 , 0
       0                 8573.77       0   139.5
Bank Sta=3749.52,3883.35
XS Rating Curve= 0 ,0
Exp/Cntr=0.3,0.1

Type RM Length L Ch R = 1 ,58579.48,516.96,625.29,645.1
Node Name=AD
XS GIS Cut Line= 6
2998093.9866044413869514.59611432997274.7375867813867731.0983689
2996181.3700228613866448.49004182995957.6798534413866308.6799539
2995057.0943842813866399.72078242991311.28396253 13865194.706132
#Sta/Elev= 30
       0  141.14  234.72  139.78 1894.96  139.72  2132.2   138.3 2451.33  139.69
 2930.01  137.62 3029.74  138.56 3064.65   134.6 3084.59  138.88 3398.73     135
 3453.58  135.86 3677.91  133.66 3876.99   135.1 4125.83  134.03 4185.55  135.84
 4220.38  130.37 4245.26  120.47 4250.24  120.22 4275.12  130.42 4309.96  135.01
 4324.89  132.69 4364.98  133.56 5418.75  137.62 5803.72   136.9 7123.63   139.5
  7633.6  138.32  7663.6   139.8 7823.58  138.49 8368.56  139.94 8753.56  139.07
#Mann= 5 ,-1 , 0
       0     .07       0 1894.96     .12       0 4185.55     .06       0
 4309.96     .12       0 4364.98     .07       0
#XS Ineff= 2 ,-1
       0 3084.59     138 5518.74 8753.56     138
Permanent Ineff=
       F       F
Bank Sta=4185.55,4309.96
XS Rating Curve= 0 ,0
Exp/Cntr=0.3,0.1

Type RM Length L Ch R = 1 ,57954.2 ,426.01,574.3,539.42
XS GIS Cut Line= 6
2998499.9861205213868941.84693172997023.7016715313866495.1940166
2996532.9483879513866104.15542862995885.8899707813865916.0600043
2995426.5099840313865913.60003542991318.0546182813865064.2953036
#Sta/Elev= 30
       0  140.04 1321.73  140.08 2582.77  137.07 2792.59  137.95 3490.02  132.72
 3914.29  133.69 3934.26  136.06  3969.2  133.75 4098.98  133.02 4138.91  135.62
 4163.75  131.98  4173.5  126.72 4183.24  119.07 4197.86  119.81 4212.49  127.21
 4222.31  129.54 4242.11   133.5 4256.96   134.2 4468.36  135.07 4558.88  134.02
 5472.35  137.89 5557.26  134.49 5712.09  137.36 6076.69  136.78 6361.38  138.93
 7070.61  137.89  8688.8  140.03  8773.7  139.96 8788.69  136.77 8813.66  138.97
#Mann= 5 ,-1 , 0
       0     .07       0 1321.73     .12       0 4138.91     .06       0
 4256.96     .12       0 4468.36     .07       0
#XS Ineff= 1 ,-1
 5472.35 8813.66  137.89
Permanent Ineff=
       F
#Block Obstruct= 2 , 0
       0                  8773.7       0  139.96
Bank Sta=4138.91,4256.96
XS Rating Curve= 0 ,0
Exp/Cntr=0.3,0.1

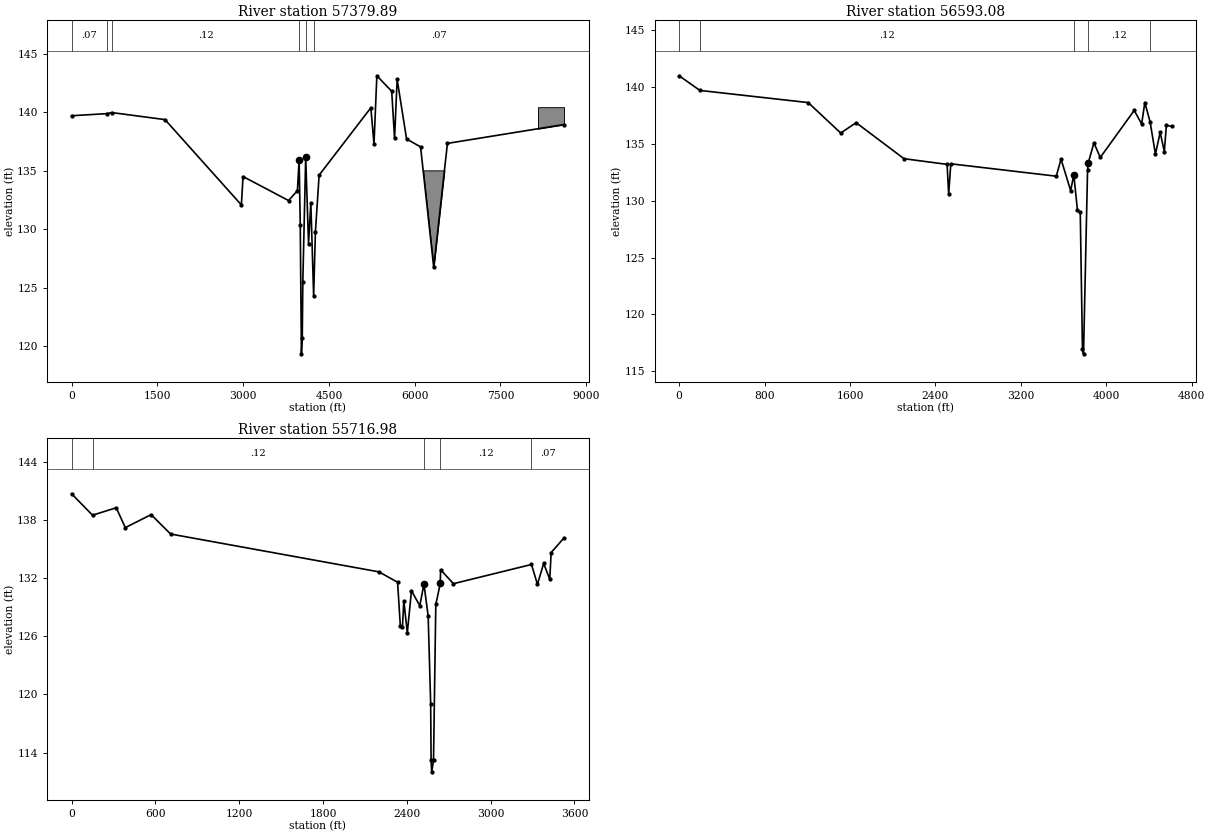
Type RM Length L Ch R = 1 ,57379.89,168.52,786.81,806.01
XS GIS Cut Line= 6
2998242.6116352813868347.34779262997132.6781596113866427.6813564
2996584.8334547713865892.28774212995850.22370353 13865381.796309
2995531.3191576213865406.61876592991355.4075619413864012.1845469
#Sta/Elev= 30
       0  139.69  617.21  139.87  702.73  139.96 1633.12  139.36 2968.53  132.08
 2998.32   134.5 3794.63  132.45 3948.52   133.3 3978.51  135.91  3998.5  130.36
  4018.5  119.37 4033.49  120.69 4043.49  125.54 4093.47  136.15 4143.45  128.78
 4183.43  132.25 4232.55  124.32 4263.39  129.78 4328.35  134.62 5232.86  140.37
 5287.83  137.28 5337.81   143.1 5597.67  141.78 5647.64  137.76 5692.61   142.8
 5857.52  137.71 6102.39  137.03 6332.27  126.76 6572.14  137.33 8611.01  138.94
#Mann= 6 ,-1 , 0
       0     .07       0  617.21     .15       0  702.73     .12       0
 3978.51     .06       0 4093.47     .12       0 4232.55     .07       0
#XS Ineff= 1 ,-1
 5367.79 8611.01     137
Permanent Ineff=
       F
#Block Obstruct= 2 ,-1
 6102.39 6602.12  135.03 8156.28 8611.01  140.42
Bank Sta=3978.51,4093.47
XS Rating Curve= 0 ,0
Exp/Cntr=0.3,0.1

Type RM Length L Ch R = 1 ,56593.08,826.42,876.1,804.4
Node Name=AC
XS GIS Cut Line= 6
2997985.2368219513867752.84832542997325.4878133513866418.8496811
 2996607.738592713865672.10084652996016.5698275313865457.4690579
2995813.2900503613864776.74994692995649.4403124513864048.1175459
#Sta/Elev= 30
       0  141.01  194.57  139.72 1208.56  138.65 1513.12  135.97 1657.53  136.88
  2105.7  133.71 2509.05  133.21 2523.99   130.6 2543.95  133.26 3531.52  132.17
 3576.36  133.67 3666.03   130.9 3695.92  132.28 3729.96  129.17 3756.18  128.99
 3776.83  116.92 3786.79  116.53 3824.52   132.7 3830.68  133.33 3884.19   135.1
 3943.78  133.82 4261.56  137.96 4331.07  136.77 4360.86  138.65 4410.45  136.94
 4460.17  134.11 4504.53  136.03 4543.37  134.34 4562.79  136.66 4611.35  136.55
#Mann= 5 ,-1 , 0
       0     .15       0  194.57     .12       0 3695.92     .06       0
 3830.68     .12       0 4410.45     .07       0
#Block Obstruct= 2 , 0
       0                 4410.45       0  136.94
Bank Sta=3695.92,3830.68
XS Rating Curve= 0 ,0
Exp/Cntr=0.3,0.1

Type RM Length L Ch R = 1 ,55716.98,1058.6,1220.04,1236.63
XS GIS Cut Line= 6
2998021.4867494413867085.8490033 2996767.238273713865461.8509389
2996637.9603170313865211.38654492996593.2599471113864843.9699568
2996455.6637656113864192.39350412996415.4755257813864042.1483978
#Sta/Elev= 30
       0  140.69  149.85  138.48  319.53  139.25  384.43   137.2  569.15  138.54
  708.95  136.54  2200.3  132.64 2333.81  131.57  2353.7  127.03 2368.62  126.95
 2378.56  129.66 2403.42  126.34 2433.25  130.69 2492.85  129.15 2522.42  131.38
  2552.7  128.11  2570.7  119.06 2573.76  113.22 2578.15  112.02  2591.1   113.2
 2607.49  129.28  2639.7  131.44 2641.46  132.86 2733.86  131.42 3292.39   133.4
 3335.19  131.35  3379.7  133.51 3423.44  131.87 3433.16  134.63 3525.51  136.14
#Mann= 5 ,-1 , 0
       0     .15       0  149.85     .12       0 2522.42     .06       0
  2639.7     .12       0 3292.39     .07       0
Bank Sta=2522.42,2639.7
XS Rating Curve= 0 ,0
Exp/Cntr=0.3,0.1