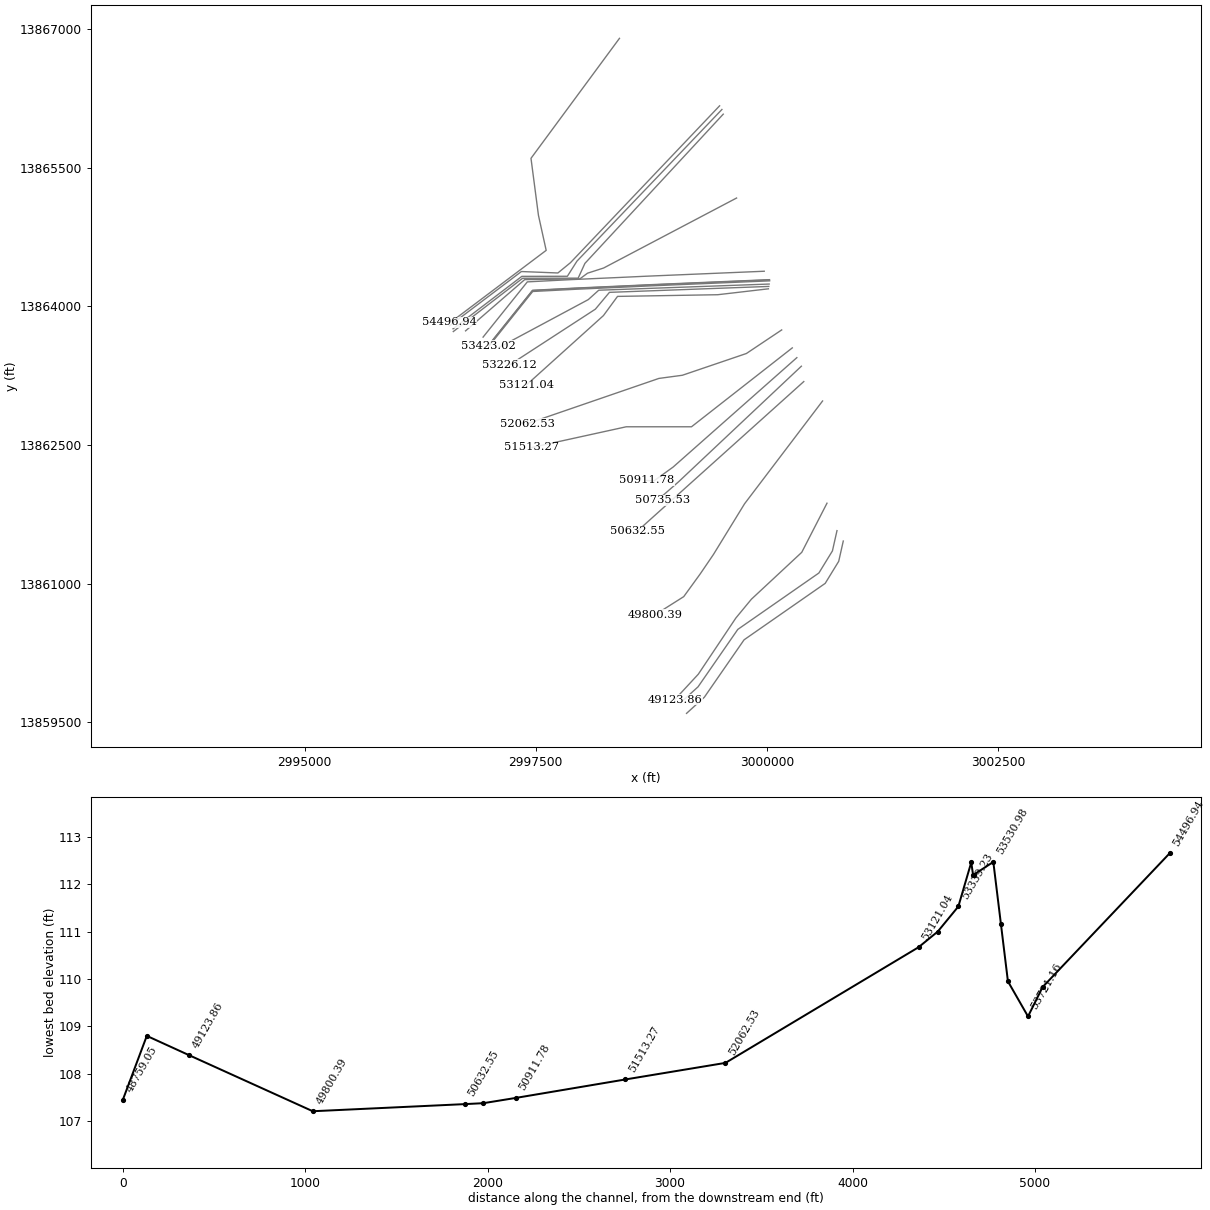
HEC-RAS study U101-00-00.prj: U101-00-00 2019 (Re-Study)

--- U101-00-00.g01 (geometry) --- (continued)

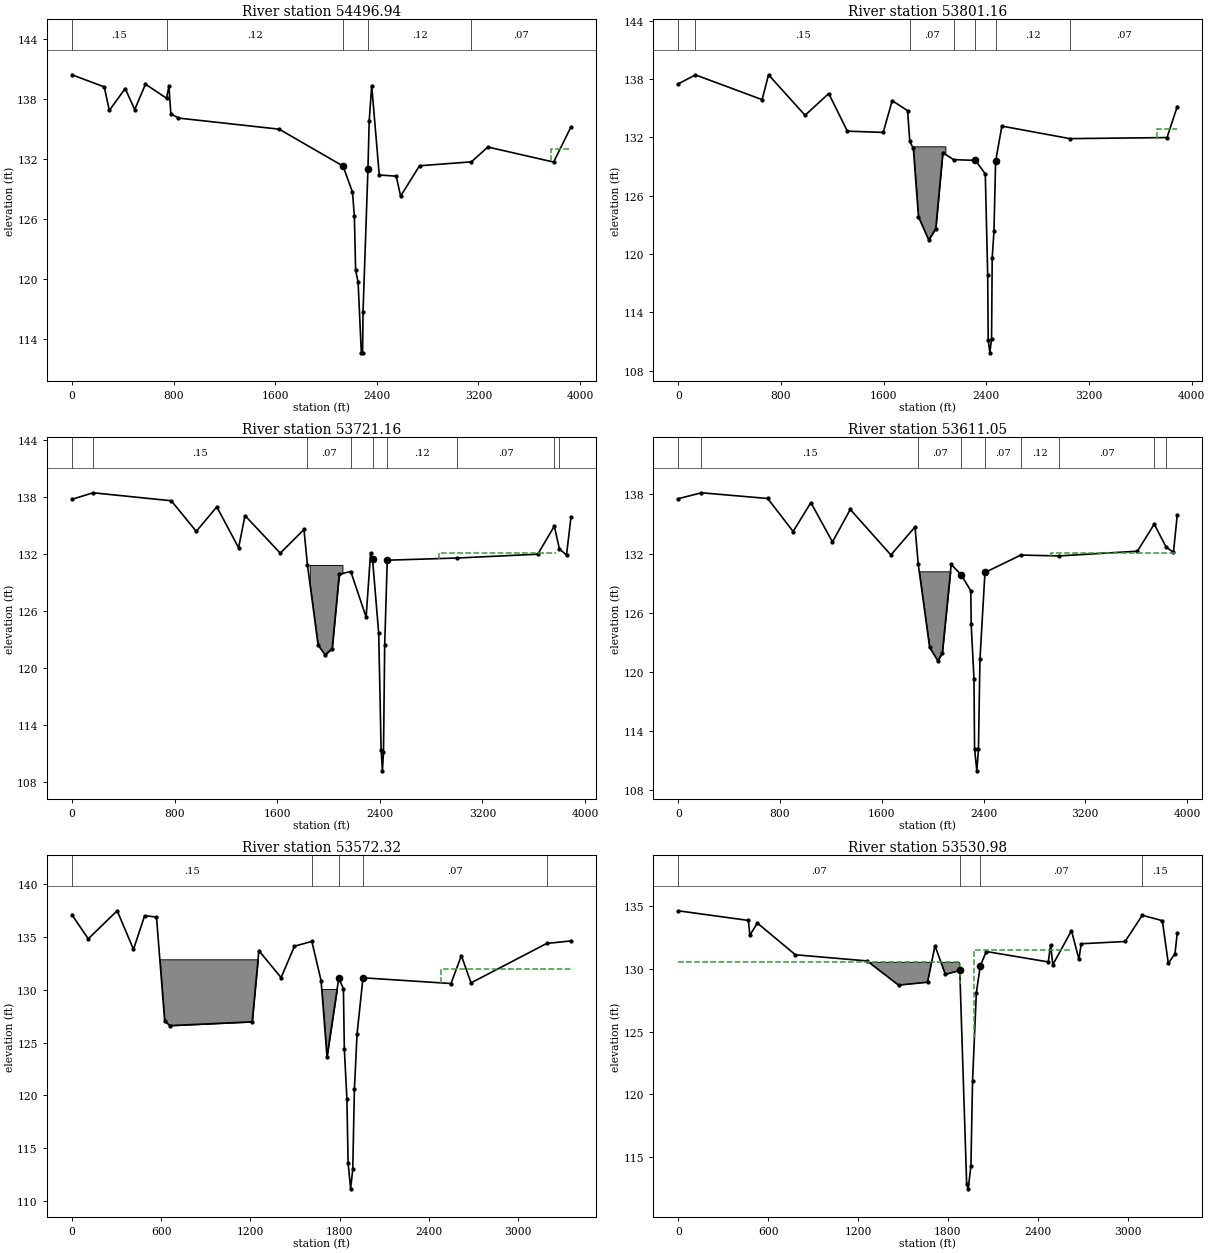
Type RM Length L Ch R = 1 ,54496.94,710.28,695.77,643.48
Node Name=AB
XS GIS Cut Line= 6
2998405.7363090213866897.34938032997448.7375668613865599.6009915
2997529.3299253613864983.4401504 2997613.020046713864604.1498984
2996646.3090536113863876.25896582996562.7134202713863827.2607042
#Sta/Elev= 30
       0   140.4   254.6  139.19  294.53  136.84  419.34  139.03  494.22  136.93
  579.08  139.46  744.73  138.06  763.79  139.26  778.77  136.51  838.67  136.08
 1632.33  134.97 2134.43  131.29    2209   128.7 2223.92   126.3 2233.86  120.88
 2253.28  119.72  2278.7  112.66 2288.69  112.65 2292.11  116.73 2330.95  131.01
 2340.66  135.76 2360.45  139.32 2419.81   130.4 2553.38  130.28 2588.01  128.29
 2737.17  131.32 3145.42  131.71 3275.01  133.19 3792.92  131.69 3929.65   135.2
#Mann= 5 ,-1 , 0
       0     .15       0  744.73     .12       0 2134.43     .06       0
 2330.95     .12       0 3145.42     .07       0
#XS Ineff= 2 ,-1
 3145.42    3773  131.71    3773 3929.65  132.95
Permanent Ineff=
       F       F
Bank Sta=2134.43,2330.95
XS Rating Curve= 0 ,0
Exp/Cntr=0.3,0.1

Type RM Length L Ch R = 1 ,53801.16,41.72,80,95
XS GIS Cut Line= 5
2999488.5402457713866167.34231012997875.6018706113864470.8854012
2997739.7100820213864359.58345842997344.9365933513864375.1598708
2996566.34989594 13863786.645956
#Sta/Elev= 30
       0   137.5  134.13  138.43  653.84  135.88  703.75  138.44  988.24  134.27
 1172.92  136.51 1317.66  132.64 1597.16  132.51 1667.04  135.78 1786.82  134.75
 1804.22  131.58 1831.74  130.86 1871.67  123.82 1951.53  121.45 2006.43  122.62
 2061.33  130.43 2144.77  129.71 2315.88  129.63 2392.15  128.24    2411  117.85
  2414.9  111.15 2427.93  109.83 2441.11  111.29 2446.18  119.62 2459.93  122.35
 2472.63  129.53 2521.43  133.16 3051.43  131.87 3807.87  131.98 3887.54  135.17
#Mann= 7 ,-1 , 0
       0     .07       0  134.13     .15       0 1804.22     .07       0
 2144.77     .12       0 2315.88     .06       0 2472.63     .12       0
 3051.43     .07       0
#XS Ineff= 3 ,-1
       0 1667.04     133 3051.43  3728.2  131.87 3733.18 3887.54  132.87
Permanent Ineff=
       F       F       F
#Block Obstruct= 1 ,-1
 1821.76  2081.3  131.08
Bank Sta=2315.88,2472.63
XS Rating Curve= 0 ,0
Exp/Cntr=0.3,0.1

Type RM Length L Ch R = 1 ,53721.16,81.94,110.11,89.03
XS GIS Cut Line= 5
2999513.7380300313866127.74593262997946.0095381913864487.6990159
2997842.1501658613864323.92572132997349.63540286  13864322.95197
2996605.6746204513863755.8681304
#Sta/Elev= 30
       0  137.76   164.9  138.45   774.6  137.61   969.5  134.39 1129.41  136.97
 1299.33  132.67  1349.3  136.05 1624.16   132.1 1809.06  134.59 1835.62   130.9
 1919.01  122.43 1973.98  121.41 2028.95  122.07 2083.92  129.89 2174.02  130.17
 2293.68  125.37 2328.49  132.14 2343.41   131.5 2391.66  123.66 2410.41  111.45
 2420.62  109.21    2429  111.18 2438.27   122.4 2458.21  131.36 3004.51  131.59
 3631.97  131.99 3760.94  134.95 3800.24  132.54 3855.88   131.9 3890.71   135.9
#Mann= 9 ,-1 , 0
       0     .07       0   164.9     .15       0 1835.62     .07       0
 2174.02     .12       0 2343.41     .06       0 2458.21     .12       0
 3004.51     .07       0 3760.94     .15       0 3800.24     .07       0
#XS Ineff= 3 ,-1
       0 1809.06     133 2860.75  3771.3  132.14  3771.3 3890.71     133
Permanent Ineff=
       F       F       F
#Block Obstruct= 1 ,-1
 1854.04 2108.91  130.86
Bank Sta=2343.41,2458.21
XS Rating Curve= 0 ,0
Exp/Cntr=0.3,0.1

Type RM Length L Ch R = 1 ,53611.05,251.1,38.73,27.62
XS GIS Cut Line= 5
2999528.1366232813866077.35036412998031.8413875313864463.1541174
2997958.8031477813864303.48153652997358.02088478 13864302.369334
2996608.3852449513863726.0529014
#Sta/Elev= 30
       0  137.57  183.04  138.17  703.73  137.59  903.37  134.24 1043.12  137.17
 1212.81  133.18 1352.56  136.48 1671.98  131.86 1861.64   134.7 1886.96  130.92
 1976.43  122.48 2041.31  121.11 2076.25  121.93 2146.13   130.9 2225.41  129.83
 2300.27  128.22 2303.13  124.82 2325.12  119.29 2329.67  112.21 2347.47  109.95
 2360.26  112.14 2372.06  121.25 2411.37  130.08 2693.47  131.85 2990.81  131.76
 3609.43  132.24 3742.37  134.99  3834.2  132.69  3893.1  132.12 3922.96  135.91
#Mann= 9 ,-1 , 0
       0     .07       0  183.04     .15       0 1886.96     .07       0
 2225.41     .06       0 2411.37     .07       0 2693.47     .12       0
 2990.81     .07       0 3742.37     .15       0  3834.2     .07       0
#XS Ineff= 2 ,-1
       0 2151.12   130.4 2927.75 3922.96  132.07
Permanent Ineff=
       F       F
#Block Obstruct= 1 ,-1
  1881.6 2151.12   130.2
Bank Sta=2225.41,2411.37
XS Rating Curve= 0 ,0
Exp/Cntr=0.3,0.1

Type RM Length L Ch R = 1 ,53572.32,142.05,41.33,9.31
Node Name=AA
XS GIS Cut Line= 6
 2999672.289550213865170.25703392998234.1031221213864413.1538894
2998060.1392311913864357.14153422997977.0846072713864295.5202664
 2997380.469002613864287.85066232996741.2196249413863733.4275585
#Sta/Elev= 30
       0  137.09  109.68  134.82  304.12  137.47   413.8  133.82  488.59     137
  568.35  136.88   623.2  127.05   658.1  126.61 1211.49  126.97 1256.36   133.7
 1405.93  131.15 1495.67  134.12 1612.58  134.57 1674.69  130.86 1714.21  123.66
 1793.24  131.07 1824.68  130.11 1830.85   124.4 1848.32  119.63 1856.14  113.65
  1873.1  111.17 1887.54  113.02 1898.55  120.59 1916.43  125.82 1956.22  131.13
 2547.96  130.59 2617.64  133.23 2682.35  130.65  3191.2  134.38 3354.31  134.62
#Mann= 5 ,-1 , 0
       0     .15       0 1612.58     .07       0 1793.24     .04       0
 1956.22     .07       0  3191.2     .15       0
#XS Ineff= 2 ,-1
       0 1793.24   130.3  2478.3 3354.31  131.92
Permanent Ineff=
       F       F
#Block Obstruct= 2 ,-1
  568.35 1261.35  132.88 1664.81 1793.24  130.07
Bank Sta=1793.24,1956.22
XS Rating Curve= 0 ,0
Exp/Cntr=0.5,0.3

Type RM Length L Ch R = 1 ,53530.98,93.85,107.96,111.39
BEGIN DESCRIPTION:
Upstream Section - CLAY ROAD
END DESCRIPTION:
XS GIS Cut Line= 6
2999971.4415109513864378.29601942998686.9778725213864324.1478338
2998417.78352903 13864311.609473 2997872.8285822 13864287.219758
2997409.0450609513864263.26770622996930.5437213613863665.8325493
#Sta/Elev= 30
       0  134.65   468.4  133.88  478.36   132.7  528.19  133.67  782.33  131.14
 1260.69  130.65 1470.25  128.72  1664.1  128.95 1713.65  131.86 1783.02  129.57
 1879.15  129.89 1924.99  112.89 1935.34  112.47  1953.5  114.29 1964.41  121.08
 1989.83  128.12 2016.13  130.26 2055.88   131.4 2470.11  130.57 2485.09  131.94
 2500.07  130.35 2624.63  133.06 2674.33  130.78 2689.24  132.02 2982.49   132.2
 3096.82  134.29 3231.01  133.86 3270.77  130.45  3315.5  131.23 3330.41  132.88
#Mann= 4 ,-1 , 0
       0     .07       0 1879.15     .04       0 2016.13     .07       0
 3096.82     .15       0
#XS Ineff= 3 ,-1
       0 1882.12  130.53 1976.87 2619.66  131.51 2619.66 3330.41     132
Permanent Ineff=
       F       F       F
#Block Obstruct= 2 , 0
       0 1876.83  130.53               0
Bank Sta=1879.15,2016.13
XS Rating Curve= 0 ,0
Exp/Cntr=0.5,0.3

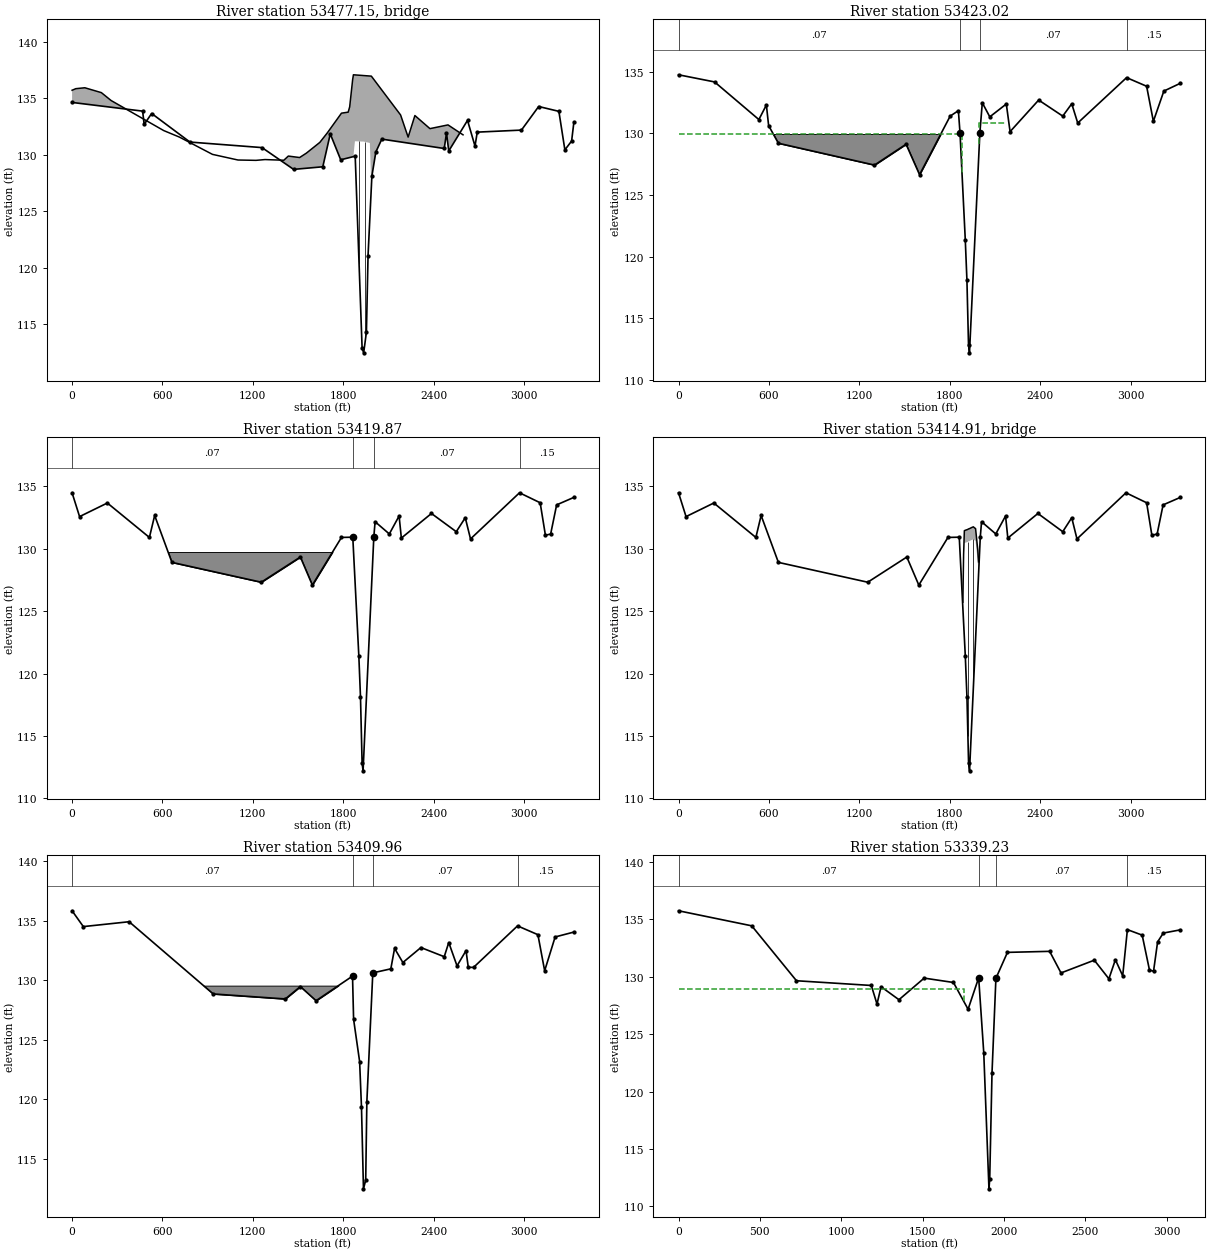
Type RM Length L Ch R = 3 ,53477.15,,,
BEGIN DESCRIPTION:
CLAY ROAD
END DESCRIPTION:
Node Name=CLAY ROAD
Bridge Culvert--1,0,-1,-1, 0
Deck Dist Width WeirC Skew NumUp NumDn MinLoCord MaxHiCord MaxSubmerge Is_Ogee
10,87,2.6,0, 32, 33, , , 0.98, 0, 0,0,,
       0   24.91   84.71  194.34  259.11  607.92  712.56  931.81 1101.24 1220.83
 1280.62 1405.38 1435.32 1510.18 1555.09 1644.28 1693.83 1787.98 1832.57 1842.48
  1862.3 1867.26 1877.17 1936.64 1976.39 1986.32 2180.49 2230.42 2275.36 2375.23
 2495.08 2594.81
  135.73  135.87  135.95  135.52  134.82  132.16  131.58  130.05  129.55  129.52
  129.59  129.53   129.9  129.77  130.16  131.11  131.95   133.7  133.79  134.26
  136.68   137.1  137.09  137.03  136.99  136.98  133.54  131.58  133.49  132.33
  132.66  131.78
       0       0       0       0       0       0       0       0       0       0
       0       0       0       0       0       0       0       0       0       0
       0       0  131.21  131.18  131.06       0       0       0       0       0
       0       0
       0   24.91   84.71  194.34  259.11  607.92  712.56  931.81 1101.24 1220.83
 1280.62 1405.38 1435.32 1510.18 1555.09 1644.28 1693.83 1787.98 1832.57 1842.48
 1867.26 1877.17 1882.12 1916.81 1956.51 1996.26 2001.23 2180.49 2230.42 2275.36
 2375.23 2495.08 2594.81
  135.73  135.87  135.95  135.52  134.82  132.16  131.58  130.05  129.55  129.52
  129.59  129.53   129.9  129.77  130.16  131.11  131.95   133.7  133.79  134.11
  136.19  136.91  136.92  136.98  137.04  137.11  137.05  133.54  131.58  133.49
  132.33  132.66  131.78
       0       0       0       0       0       0       0       0       0       0
       0       0       0       0       0       0       0       0       0       0
       0       0  130.97  131.08  130.95  130.95       0       0       0       0
       0       0       0
Pier Skew, UpSta & Num, DnSta & Num=  ,1904.91, 2 ,1918.09, 2 , 0 , 0 , 0 ,,
    1.35    1.35
     110     132
    1.35    1.35
     110     132
Pier Skew, UpSta & Num, DnSta & Num=  ,1945.85, 2 ,1958.78, 2 , 0 , 0 , 0 ,,
    1.35    1.35
     110     132
    1.35    1.35
     110     132
Abutment Skew #Up #Dn= , 2 , 2
 1845.72 1867.55
  133.33  131.49
 1854.82 1876.49
  133.39  131.34
Abutment Skew #Up #Dn= , 2 , 2
 1987.15 2008.78
  131.37  133.31
 1996.44 2018.22
   131.3  133.38
BR Coef=-1 , 1 , 1 ,0.9, 0 ,,,0.8,-1,1.2,0,
WSPro=,,,, 1 ,,,, 0 ,,,, 0 ,,,,-1 ,-1 ,-1 , 0 , 0 , 0 , 0 , 0
BC Design=,, 0 ,, 0 ,,,,,,
BC Use User HTab Curves=0
BC User HTab FreeFlow(D)= 0

Type RM Length L Ch R = 1 ,53423.02,3.15,3.15,3.94
BEGIN DESCRIPTION:
Downstream Section - CLAY ROAD
END DESCRIPTION:
XS GIS Cut Line= 6
3000027.7471726113864287.2217265 2998743.283534213864233.0735409
2998474.0891906913864220.53518012997929.1342438613864196.1454651
2997465.3507226113864172.19341332996986.8493830313863574.7582564
#Sta/Elev= 30
       0  134.74  239.18  134.16  533.18  131.11  583.01  132.29  597.96  130.62
  662.73  129.19 1300.58  127.42 1510.18  129.11 1599.68  126.64 1802.84  131.39
 1857.35  131.83 1868.35     130  1903.1  121.38    1914  118.11 1924.65  112.83
 1931.13   112.2  1999.8  130.01 2016.13  132.47 2065.81  131.33 2175.49  132.37
 2200.46  130.13 2390.21  132.69    2550  131.39 2609.72  132.39 2649.48  130.83
 2973.82  134.51 3106.75  133.81 3151.48  130.97 3221.07  133.42 3330.41  134.05
#Mann= 4 ,-1 , 0
       0     .07       0 1868.35     .04       0  1999.8     .07       0
 2973.82     .15       0
#XS Ineff= 3 ,-1
       0 1881.95  129.94 1996.33  2170.5   130.8  2170.5 3330.41   131.7
Permanent Ineff=
       F       F       F
#Block Obstruct= 2 , 0
       0 1857.35  129.94               0
Bank Sta=1868.35,1999.8
XS Rating Curve= 0 ,0
Exp/Cntr=0.5,0.3

Type RM Length L Ch R = 1 ,53419.87,9.89,9.91,12.4
BEGIN DESCRIPTION:
Upstream Section - 12" PIPELINE
END DESCRIPTION:
XS GIS Cut Line= 6
3000028.1730247713864284.09902932998743.7093863613864229.9508437
2998474.5150428613864217.41248292997929.5600960313864193.0227679
2997465.7765747813864169.07071612996987.2752351913863571.6355593
#Sta/Elev= 30
       0  134.49   49.83  132.58   234.2  133.67  513.25  130.91  548.13  132.67
  662.73  128.91 1255.71  127.32 1515.17  129.34 1594.73  127.09 1787.98  130.91
 1863.16  130.93 1903.38  121.38 1914.29  118.11 1924.94  112.83 1931.42   112.2
 2002.63  130.93 2011.16  132.17 2105.58  131.19  2170.5  132.63 2185.48  130.86
 2385.22  132.83    2550  131.37 2609.72  132.49 2644.51  130.79 2969.67  134.49
 3106.75  133.69 3141.54  131.09 3176.33  131.18  3216.1  133.52 3330.41  134.12
#Mann= 4 ,-1 , 0
       0     .07       0 1863.16     .04       0 2002.63     .07       0
 2969.67     .15       0
#XS Ineff= 2 ,-1
       0 1825.82  129.74  2170.5 3330.41   131.7
Permanent Ineff=
       F       F
#Block Obstruct= 2 , 0
       0 1857.35  129.74               0
Bank Sta=1863.16,2002.63
XS Rating Curve= 0 ,0
Exp/Cntr=0.4,0.2

Type RM Length L Ch R = 3 ,53414.91,,,
BEGIN DESCRIPTION:
12" PIPELINE
END DESCRIPTION:
Node Name=12" PIPELINE
Bridge Culvert--1,0,-1,-1, 0
Deck Dist Width WeirC Skew NumUp NumDn MinLoCord MaxHiCord MaxSubmerge Is_Ogee
4.7,1,2.6,0, 18, 18, , , 0.98, 0, 0,0,,
 1887.08 1892.03 1896.99 1901.94  1906.9 1911.85 1916.81 1926.72 1931.67 1936.64
 1941.61 1946.58 1956.51 1961.48 1966.45 1971.42 1986.32 1991.29
  125.72  129.56  131.45  131.48   131.5  131.52  131.54   131.6  131.62  131.65
  131.68  131.71  131.76  131.71  131.66  131.62  129.89  128.95
       0  128.56  130.45  130.48   130.5  130.52  130.54   130.6  130.62  130.65
  130.68  130.71  130.76  130.71  130.66  130.62  128.89       0
 1887.08 1892.03 1896.99 1901.94  1906.9 1911.85 1916.81 1926.72 1931.67 1936.64
 1941.61 1946.58 1956.51 1961.48 1966.45 1971.42 1986.32 1991.29
  125.72  129.56  131.45  131.48   131.5  131.52  131.54   131.6  131.62  131.65
  131.68  131.71  131.76  131.71  131.66  131.62  129.89  128.95
       0  128.56  130.45  130.48   130.5  130.52  130.54   130.6  130.62  130.65
  130.68  130.71  130.76  130.71  130.66  130.62  128.89       0
Pier Skew, UpSta & Num, DnSta & Num=  ,1920.5, 2 ,1920.5, 2 , 0 , 0 , 0 ,,
     1.5     1.5
     110     131
     1.5     1.5
     110     131
Pier Skew, UpSta & Num, DnSta & Num=  ,1956, 2 ,1956, 2 , 0 , 0 , 0 ,,
     1.5     1.5
     110     131
     1.5     1.5
     110     131
BR Coef=-1 , 1 , 1 ,0.9, 0 ,,,0.8,-1,1.2,0,
WSPro=,,,, 1 ,,,, 0 ,,,, 0 ,,,,-1 ,-1 ,-1 , 0 , 0 , 0 , 0 , 0
BC Design=,, 0 ,, 0 ,,,,,,
BC Use User HTab Curves=0
BC User HTab FreeFlow(D)= 0

Type RM Length L Ch R = 1 ,53409.96,22.51,70.73,109.83
BEGIN DESCRIPTION:
Downstream Section - 12" PIPELINE
END DESCRIPTION:
XS GIS Cut Line= 6
3000029.5122609413864274.27621432998745.0486225313864220.1280287
2998475.8542790313864207.5896679 2997930.899332213864183.1999529
2997467.1158109513864159.24790112996988.6144713613863561.8127443
#Sta/Elev= 30
       0  135.83   74.74   134.5  378.71  134.91   936.8  128.84 1415.36  128.42
 1515.17  129.46  1619.5  128.27  1861.4  130.34 1868.49  126.71 1908.49  123.16
 1920.79  119.35 1934.04  112.46 1948.89  113.19 1956.53  119.79 1995.96  130.61
 2115.57  130.95 2140.54  132.67 2195.47  131.48 2315.31  132.74 2470.11  131.97
 2500.07  133.16    2555   131.2 2614.69  132.48  2629.6  131.08 2664.39  131.07
 2956.64  134.56 3091.84  133.82 3136.57  130.79 3206.16  133.63 3330.41  134.04
#Mann= 4 ,-1 , 0
       0     .07       0  1861.4     .04       0 1995.96     .07       0
 2956.64     .15       0
#XS Ineff= 2 ,-1
       0 1805.64  129.54 2175.49 3330.41   131.7
Permanent Ineff=
       F       F
#Block Obstruct= 2 , 0
       0 1852.39  129.54               0
Bank Sta=1861.4,1995.96
XS Rating Curve= 0 ,0
Exp/Cntr=0.4,0.2

Type RM Length L Ch R = 1 ,53339.23,27.28,113.11,119.61
XS GIS Cut Line= 4
3000024.8501967813864239.79235942998181.5185816113864173.0933459
2998068.4902643613864071.62438872997109.9564202713863558.1076992
#Sta/Elev= 30
       0  135.73  449.89  134.42  724.82  129.64  1184.7  129.23 1219.69  127.61
 1244.69  129.12 1354.66  127.99 1509.62  129.87 1689.58  129.49 1779.55  127.16
 1844.54   129.9 1875.83  123.37 1907.77  111.53 1912.38  112.36 1926.51  121.62
 1950.48  129.85 2021.37  132.11 2280.76   132.2 2350.59  130.32 2555.11  131.43
  2644.9  129.81  2684.8  131.47  2729.7  130.07 2758.54  134.09 2849.42  133.61
 2894.31  130.57 2919.25  130.47 2944.19  133.02 2979.11  133.79 3083.86  134.07
#Mann= 4 ,-1 , 0
       0     .07       0 1844.54     .04       0 1950.48     .07       0
 2758.54     .15       0
#XS Ineff= 2 ,-1
       0 1752.35  128.94 2036.34 3083.86   131.5
Permanent Ineff=
       F       F
Bank Sta=1844.54,1950.48
XS Rating Curve= 0 ,0
Exp/Cntr=0.3,0.1

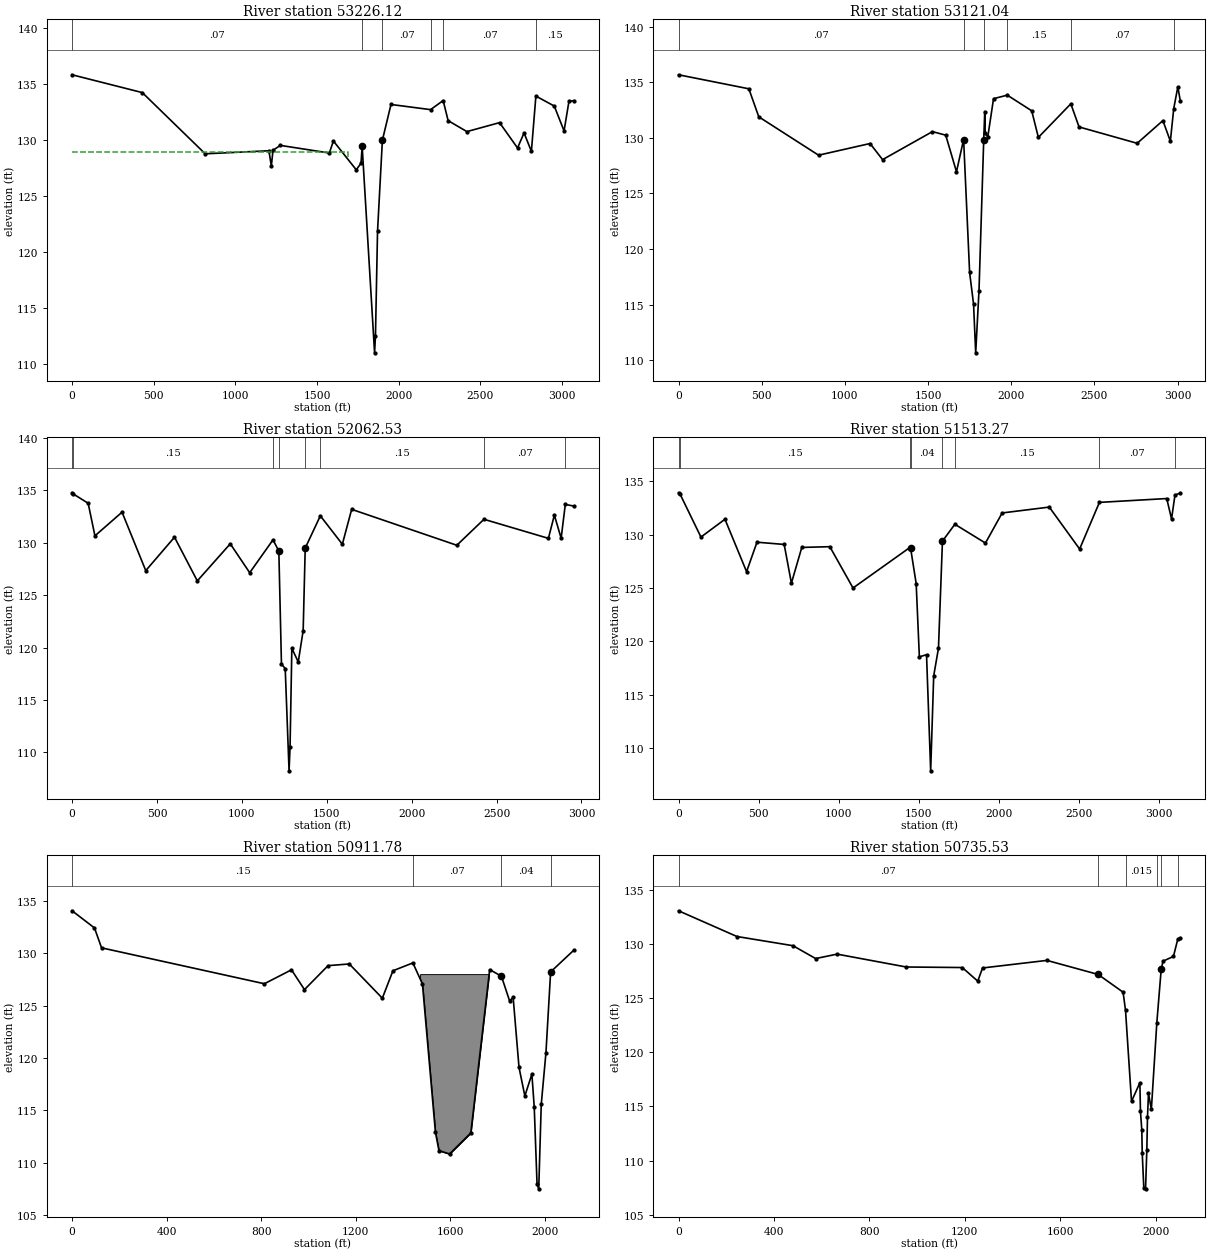
Type RM Length L Ch R = 1 ,53226.12,97.8,105.08,108.76
Node Name=Z
XS GIS Cut Line= 4
3000020.80132036  13864214.01518 2998297.234885613864150.0008724
2998145.0248881913863968.03502892997214.5585732813863363.5555948
#Sta/Elev= 30
       0  135.81  429.94  134.22  814.88  128.76 1204.83  129.03 1219.83  127.67
 1229.82  129.07 1274.82  129.51 1574.77  128.83 1599.77   129.9 1739.58  127.33
 1768.72  127.92  1775.7  129.42 1851.72     111 1857.19  112.54 1869.85  121.86
 1899.51  129.97  1952.1  133.16 2194.37   132.7 2271.56  133.51 2301.86  131.72
 2416.82  130.74 2616.74  131.54  2726.7  129.28 2766.69  130.62 2811.67  128.98
 2839.14  133.91 2951.62  133.02  3011.6   130.8 3041.58  133.45 3071.57   133.5
#Mann= 6 ,-1 , 0
       0     .07       0  1775.7     .04       0 1899.51     .07       0
 2194.37     .15       0 2271.56     .07       0 2839.14     .15       0
#XS Ineff= 2 ,-1
       0 1687.93  128.94 1981.98 3071.57   131.5
Permanent Ineff=
       F       F
Bank Sta=1775.7,1899.51
XS Rating Curve= 0 ,0
Exp/Cntr=0.3,0.1

Type RM Length L Ch R = 1 ,53121.04,1111.81,1058.51,984.7
XS GIS Cut Line= 5
3000016.7521158613864188.23800062999468.5327398613864124.3929839
2998384.6579391113864106.20174742998232.3898709413863898.7500625
2997398.4604364513863146.9894269
#Sta/Elev= 30
       0  135.67  422.65  134.41  482.31  131.89  841.66  128.44 1151.39  129.49
 1226.32  128.04 1526.05  130.56 1605.98  130.24 1670.59  126.95 1713.43  129.85
 1749.56   117.9 1773.18  115.05  1786.1  110.67 1805.96  116.27 1834.37  129.81
 1840.54  132.36 1843.16  130.43 1858.65  130.07 1893.29  133.52    1976  133.84
 2122.83  132.43 2162.75  130.04 2357.87  133.06 2407.26  130.98 2756.56  129.51
 2911.24  131.55 2956.15   129.7 2976.32  132.62 3001.06  134.59 3016.03  133.31
#Mann= 6 ,-1 , 0
       0     .07       0 1713.43     .04       0 1834.37     .07       0
    1976     .15       0 2357.87     .07       0 2976.32     .15       0
#XS Ineff= 2 ,-1
       0 1579.98  128.94 1908.26 3016.03   131.2
Permanent Ineff=
       F       F
Bank Sta=1713.43,1834.37
XS Rating Curve= 0 ,0
Exp/Cntr=0.3,0.1

Type RM Length L Ch R = 1 ,52062.53,556.34,549.26,533.6
XS GIS Cut Line= 5
3000160.2341123713863743.60306312999778.6518702813863488.6987173
2999086.0499090313863253.29006732998831.9798791113863219.0099522
2997405.6730204413862728.6585707
#Sta/Elev= 30
       0  134.77    4.82  134.68   94.77  133.77  134.67  130.66  294.29  132.92
  433.95  127.34   603.2  130.53  737.56  126.36  931.64   129.9  1046.1  127.14
 1183.34  130.28 1217.68   129.2 1233.07  118.43 1255.24  117.99 1277.88  108.23
 1283.71  110.51 1294.24  119.93 1331.97  118.62 1360.88  121.61    1373  129.49
 1462.04  132.57 1591.61  129.86 1646.55  133.19 2265.82  129.76 2425.56  132.24
  2805.2  130.42 2840.16  132.64 2880.11  130.43 2904.65  133.66 2955.03   133.5
#Mann= 8 ,-1 , 0
       0     .07       0    4.82     .15       0 1183.34     .07       0
 1217.68     .04       0    1373     .07       0 1462.04     .15       0
 2425.56     .07       0 2904.65     .15       0
#XS Ineff= 2 ,-1
       0 1185.43     128 1456.77 2955.03   130.8
Permanent Ineff=
       F       F
Bank Sta=1217.68,1373
XS Rating Curve= 0 ,0
Exp/Cntr=0.3,0.1

Type RM Length L Ch R = 1 ,51513.27,543.75,601.49,645.67
Node Name=Y
XS GIS Cut Line= 4
 3000274.874959213863549.36755922999184.7455777813862696.0283866
2998478.8421339413862696.02838662997460.1968615213862472.6413662
#Sta/Elev= 30
       0  133.93     8.1  133.85  139.94  129.78  289.87  131.45  424.82  126.54
  489.79   129.3  659.72  129.09   704.7  125.46  769.67  128.81  944.59  128.88
 1089.53  125.01 1443.24  128.79 1449.03  128.74 1483.83  125.42 1503.71  118.56
 1548.45  118.76 1574.31  107.88 1593.19  116.77 1623.02  119.37 1647.87   129.4
 1725.36  130.98 1916.31  129.22 2020.71  132.04 2314.84  132.59 2504.45  128.66
 2627.92  133.03 3048.32  133.39 3078.26  131.48 3099.85  133.73 3133.14  133.89
#Mann= 8 ,-1 , 0
       0     .07       0     8.1     .15       0 1443.24     .07       0
 1449.03     .04       0 1647.87     .07       0 1725.36     .15       0
 2627.92     .07       0 3099.85     .15       0
#XS Ineff= 2 ,-1
       0 1443.24     128 1737.35 3133.14   130.5
Permanent Ineff=
       F       F
Bank Sta=1449.03,1647.87
XS Rating Curve= 0 ,0
Exp/Cntr=0.3,0.1

Type RM Length L Ch R = 1 ,50911.78,167.84,176.25,182.48
XS GIS Cut Line= 4
3000324.1337189413863443.73259992998986.1823266113862260.5873284
2998777.2509859513862109.88257732998699.0182027813862115.3615689
#Sta/Elev= 30
       0  134.05   94.79  132.41  124.72  130.51   813.2  127.08  927.94  128.41
  982.82  126.52  1082.6  128.81  1172.4  128.97 1312.09   125.7 1356.99  128.32
 1441.28  129.07 1481.71  127.06 1536.59   112.9 1551.56  111.14 1596.46  110.82
 1686.26  112.83 1766.08  128.43 1815.76   127.8 1850.44  125.43  1865.3  125.78
 1890.07   119.1 1914.84  116.36 1944.57  118.45 1954.48  115.31 1966.44  107.93
 1973.51  107.49  1984.2  115.57 2004.02  120.49 2023.83  128.21 2122.07  130.29
#Mann= 4 ,-1 , 0
       0     .15       0 1441.28     .07       0 1815.76     .04       0
 2023.83     .07       0
#XS Ineff= 1 ,-1
       0 1766.08   128.1
Permanent Ineff=
       F
#Block Obstruct= 1 ,-1
 1471.74 1766.08     128
Bank Sta=1815.76,2023.83
XS Rating Curve= 0 ,0
Exp/Cntr=0.3,0.1

Type RM Length L Ch R = 1 ,50735.53,99.99,102.98,102.04
BEGIN DESCRIPTION:
CONFLUENCE WITH U101-08-00
END DESCRIPTION:
XS GIS Cut Line= 4
3000373.0552090313863351.13075092999044.7199391913862100.8701281
2998873.8465932813861951.89798512998872.9023694413861899.1743373
#Sta/Elev= 30
       0   133.1  244.89  130.72  479.78  129.87  574.74  128.68   664.7  129.09
  954.57   127.9 1189.46  127.85 1254.43  126.59 1274.42  127.81  1544.3  128.51
  1759.2  127.21  1863.6  125.57 1873.85  123.89 1898.96  115.47 1934.01  117.19
 1936.46  114.56 1942.06  112.84 1943.95  110.67 1950.45  107.48 1957.82  107.38
  1963.2  110.99 1965.94  114.01 1970.14  116.21 1982.16  114.72 2005.07  122.74
 2023.31  127.67 2031.15  128.44 2074.84  128.88 2092.94  130.48  2103.6   130.6
#Mann= 6 ,-1 , 0
       0     .07       0  1759.2     .04       0 1873.85    .015       0
 2005.07     .04       0 2023.31     .07       0 2092.94     .15       0
#XS Ineff= 1 ,-1
       0  1544.3   128.5
Permanent Ineff=
       F
Bank Sta=1759.2,2023.31
XS Rating Curve= 0 ,0
Exp/Cntr=0.3,0.1

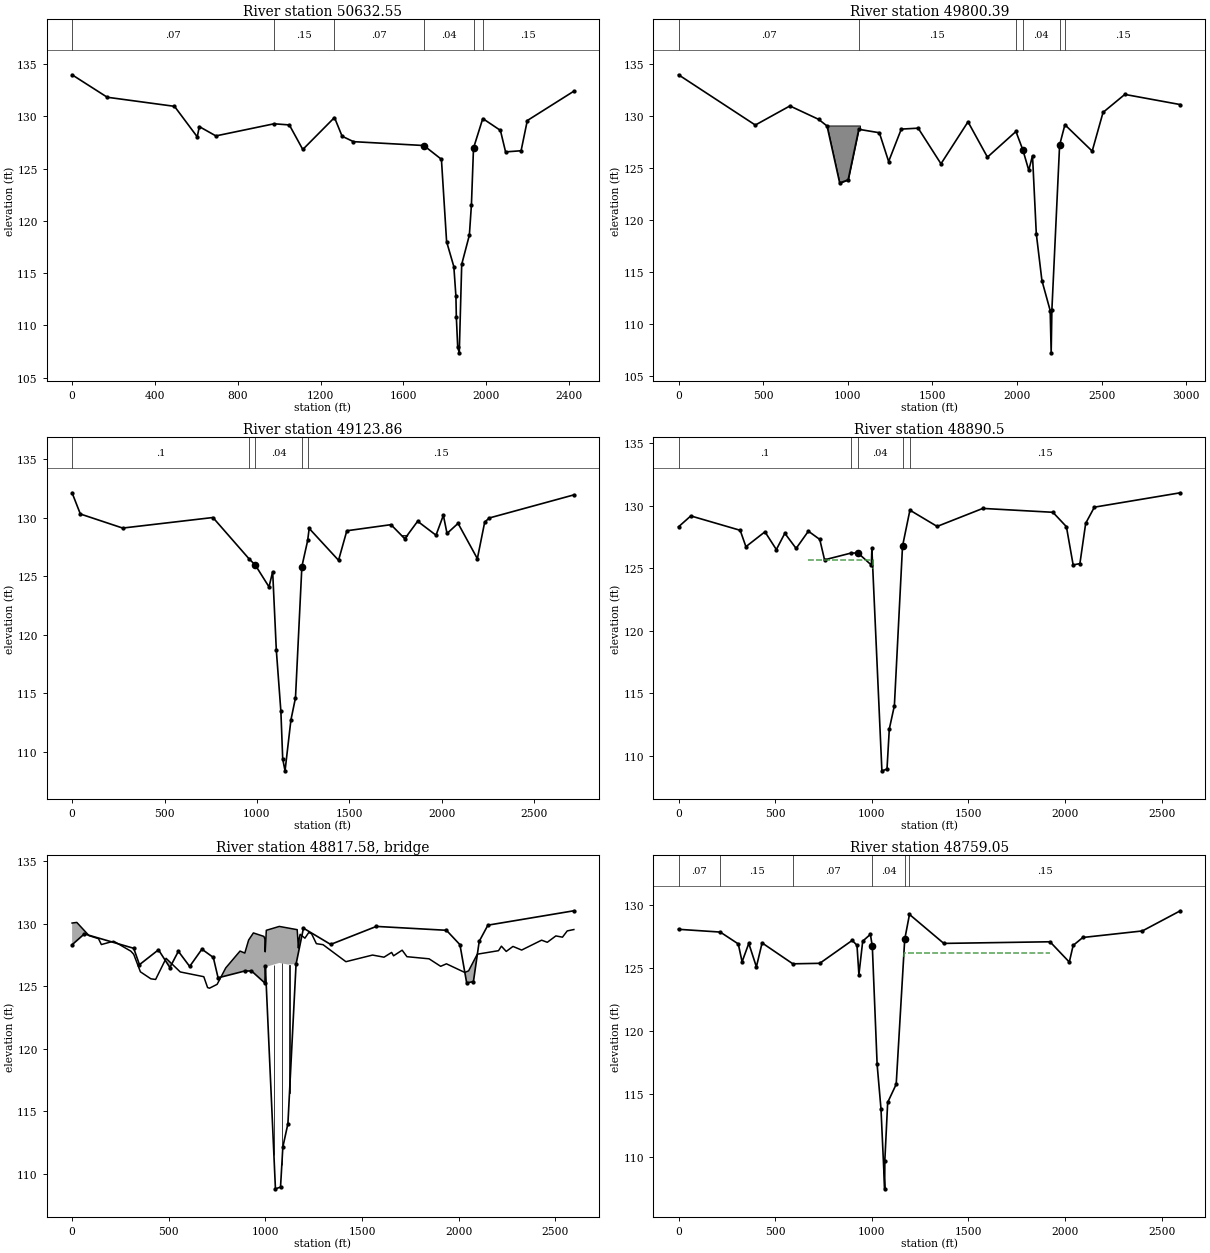
Type RM Length L Ch R = 1 ,50632.55,807.38,832.17,842.06
XS GIS Cut Line= 2
3000399.2631618513863185.14650292998596.90292144 13861565.681894
#Sta/Elev= 30
       0  133.97  169.86  131.82   494.6  130.95  604.51  128.03  614.51  129.01
  694.44  128.12  975.45  129.28 1049.15  129.17  1114.1  126.82 1267.14  129.88
 1303.95  128.09 1358.91  127.57 1698.63   127.2 1783.57  125.88 1808.55     118
 1843.52  115.61 1853.58  112.76 1855.51  110.82 1862.15  107.92 1869.68  107.36
 1881.52  115.83 1918.46  118.62 1928.45  121.54 1938.44  126.95 1983.22  129.78
 2068.34  128.65 2093.32  126.59 2168.26   126.7 2198.23  129.59 2423.05   132.4
#Mann= 6 ,-1 , 0
       0     .07       0  975.45     .15       0 1267.14     .07       0
 1698.63     .04       0 1938.44     .07       0 1983.22     .15       0
#XS Ineff= 2 ,-1
       0 1267.14  127.86 1973.41 2423.05  127.86
Permanent Ineff=
       F       F
Bank Sta=1698.63,1938.44
XS Rating Curve= 0 ,0
Exp/Cntr=0.3,0.1

Type RM Length L Ch R = 1 ,49800.39,696.46,676.53,658.5
Node Name=X
XS GIS Cut Line= 6
3000602.4835559413862975.10394392999758.6086032813861863.1708004
2999421.7998936913861314.43994242999277.6200639513861102.6998803
2999100.6952209513860858.8614573 2998789.9858686 13860662.356929
#Sta/Elev= 30
       0  133.98  453.67  129.14  658.06  130.98  827.56  129.69  877.42  129.05
   952.2  123.56 1002.05  123.87 1064.98  128.73 1186.51   128.4 1241.35  125.63
 1316.13  128.75 1415.86  128.84 1550.62  125.41 1710.33  129.45 1825.12  126.05
 1993.56  128.52 2034.75  126.73  2069.3  124.79 2091.48  126.19 2113.83  118.68
 2147.01  114.17 2195.85  111.28 2201.74  107.21 2205.93  111.35 2251.57  127.21
 2282.85  129.17 2444.07  126.63 2508.28  130.36 2636.92  132.09 2964.81  131.11
#Mann= 6 ,-1 , 0
       0     .07       0 1064.98     .15       0 1993.56     .07       0
 2034.75     .04       0 2251.57     .07       0 2282.85     .15       0
#XS Ineff= 1 ,-1
       0  2004.8     127
Permanent Ineff=
       F
#Block Obstruct= 1 ,-1
  862.46 1071.85   129.1
Bank Sta=2034.75,2251.57
XS Rating Curve= 0 ,0
Exp/Cntr=0.3,0.1

Type RM Length L Ch R = 1 ,49123.86,251.26,233.36,214.6
XS GIS Cut Line= 6
3000650.16521911 13861869.496247 3000377.260581213861338.2249998
2999832.4700041113860830.9399252 2999664.303345713860627.4308178
2999258.3668216213860020.00749192999001.5681226113859742.8505659
#Sta/Elev= 30
       0  132.11   44.79   130.3  273.75   129.1   761.9     130  956.47  126.49
  991.24  125.94 1065.28  124.08 1085.03  125.38 1104.77  118.69 1129.46  113.46
 1139.33  109.41 1151.97  108.39 1183.76  112.73 1208.44  114.62 1242.99  125.82
 1274.33  128.04 1282.49  129.07 1441.35  126.35 1486.18  128.87    1725  129.39
 1799.55  128.19 1869.13  129.68 1968.53  128.49 2008.29  130.19 2028.17  128.64
  2087.8   129.5 2192.17  126.49 2231.93  129.61 2256.78  129.96 2714.14  131.93
#Mann= 5 ,-1 , 0
       0      .1       0  956.47     .07       0  991.24     .04       0
 1242.99     .07       0 1274.33     .15       0
#XS Ineff= 2 ,-1
 1282.49 2008.29     127 2008.29 2714.14     129
Permanent Ineff=
       F       F
#Block Obstruct= 1 ,-1
 1754.82 1849.25   128.5
Bank Sta=991.24,1242.99
XS Rating Curve= 0 ,0
Exp/Cntr=0.5,0.3

Type RM Length L Ch R = 1 ,48890.5 ,132.55,131.45,131.77
BEGIN DESCRIPTION:
Upstream Section - LAKES OF BRIDGE DR
END DESCRIPTION:
XS GIS Cut Line= 6
3000758.3556195213861572.70517393000708.9498784413861353.2853372
3000562.8022048613861114.75595862999685.4286315313860504.3556046
 2999255.680147213859883.51038962999063.0827633613859708.6911854
#Sta/Elev= 30
       0  128.31    63.5  129.18  318.93  128.03  348.58  126.72  447.05  127.91
  506.05  126.49  549.91  127.79  608.38  126.58  671.72  127.96  730.71   127.3
   755.4  125.67  892.41  126.21   928.2  126.22  997.68  125.25 1000.22  126.58
 1052.13   108.8 1078.47  108.94 1090.47  112.15  1116.7  114.01 1158.79  126.76
 1197.04  129.64 1337.88  128.34 1574.18  129.78 1936.81  129.47 2006.65  128.32
 2041.57  125.26  2076.5  125.37 2106.43  128.59 2151.33  129.88 2596.03  131.03
#Mann= 5 ,-1 , 0
       0      .1       0  892.41     .07       0   928.2     .04       0
 1158.79     .07       0 1197.04     .15       0
#XS Ineff= 4 ,-1
       0  671.72   127.5  671.72 1004.92  125.67 1158.35  1941.8  126.15
  1941.8 2596.03   127.5
Permanent Ineff=
       F       F       F       F
Bank Sta=928.2,1158.79
XS Rating Curve= 0 ,0
Exp/Cntr=0.5,0.3

Type RM Length L Ch R = 3 ,48817.58,,,
BEGIN DESCRIPTION:
LAKES OF BRIDGE DR
END DESCRIPTION:
Node Name=LAKES OF BRIDGE
Bridge Culvert--1,0,-1,-1, 0
Deck Dist Width WeirC Skew NumUp NumDn MinLoCord MaxHiCord MaxSubmerge Is_Ogee
26.5,91,2.6,0, 60, 60, , , 0.98, 0, 0,0,,
       0   24.42   87.92  136.84  151.53  215.22   304.1  318.93  353.53  407.72
   432.3  486.39  559.65  681.47  701.09  710.96  750.46  794.89  868.95  893.64
  913.39  938.07  992.56  997.54  999.31 1004.92 1072.19 1164.71 1170.93 1175.05
 1179.99 1204.66  1224.4  1239.2 1263.87 1298.41 1416.71 1554.49 1613.73 1653.31
 1663.21 1707.74 1732.47 1847.01 1906.88 1936.81  2031.6 2051.55 2096.45 2206.21
 2221.18 2246.12 2281.04 2325.94 2429.17 2458.61 2502.78 2537.14 2561.68 2596.03
  130.05   130.1  129.04   128.8  128.33   128.6   127.8  127.55  126.15  125.59
  125.54  127.23  126.14  125.76  124.89  124.84  125.15  126.46  127.81  127.65
  128.69  129.26  128.98  128.76  127.75  129.47  129.78  129.52  128.05  128.81
  129.15  128.84  129.29  129.19   128.4  128.32  126.96  127.49  127.32   127.7
  127.43  127.88  127.36  127.19  126.59  126.79   126.1  126.23  127.56  127.84
   128.2  127.78  128.18  127.89  128.68  128.51  129.02  128.92  129.42  129.53
       0       0       0       0       0       0       0       0       0       0
       0       0       0       0       0       0       0       0       0       0
       0       0       0       0       0  126.55  126.86   126.6       0       0
       0       0       0       0       0       0       0       0       0       0
       0       0       0       0       0       0       0       0       0       0
       0       0       0       0       0       0       0       0       0       0
       0   24.42   87.92  136.84  151.53  215.22   304.1  318.93  353.53  407.72
   432.3  486.39  559.65  681.47  701.09  710.96  750.46  794.89  868.95  893.64
  913.39  938.07  992.56  997.54  999.31 1004.92 1072.19 1164.71 1170.93 1175.05
 1179.99 1204.66  1224.4  1239.2 1263.87 1298.41 1416.71 1554.49 1613.73 1653.31
 1663.21 1707.74 1732.47 1847.01 1906.88 1936.81  2031.6 2051.55 2096.45 2206.21
 2221.18 2246.12 2281.04 2325.94 2429.17 2458.61 2502.78 2537.14 2561.68 2596.03
  130.05   130.1  129.04   128.8  128.33   128.6   127.8  127.55  126.15  125.59
  125.54  127.23  126.14  125.76  124.89  124.84  125.15  126.46  127.81  127.65
  128.69  129.26  128.98  128.76  127.75  129.47  129.78  129.52  128.05  128.81
  129.15  128.84  129.29  129.19   128.4  128.32  126.96  127.49  127.32   127.7
  127.43  127.88  127.36  127.19  126.59  126.79   126.1  126.23  127.56  127.84
   128.2  127.78  128.18  127.89  128.68  128.51  129.02  128.92  129.42  129.53
       0       0       0       0       0       0       0       0       0       0
       0       0       0       0       0       0       0       0       0       0
       0       0       0       0       0   126.5  126.81  126.55       0       0
       0       0       0       0       0       0       0       0       0       0
       0       0       0       0       0       0       0       0       0       0
       0       0       0       0       0       0       0       0       0       0
Pier Skew, UpSta & Num, DnSta & Num=  ,1044.32, 2 ,1044.32, 2 , 0 , 0 , 0 ,,
     1.3     1.3
     105     128
     1.3     1.3
     105     128
Pier Skew, UpSta & Num, DnSta & Num=  ,1085.12, 2 ,1085.12, 2 , 0 , 0 , 0 ,,
     1.3     1.3
     105     128
     1.3     1.3
     105     128
Pier Skew, UpSta & Num, DnSta & Num=  ,1124.92, 2 ,1124.92, 2 , 0 , 0 , 0 ,,
     1.3     1.3
     105     128
     1.3     1.3
     105     128
Abutment Skew #Up #Dn= , 2 , 2
 1004.72 1029.42
  126.55  114.72
 1004.72 1029.42
   126.5  114.67
Abutment Skew #Up #Dn= , 2 , 2
 1125.02 1164.91
  113.58   126.6
 1125.02 1164.91
  113.53  126.55
BR Coef=-1 , 1 , 1 ,0.9, 0 ,,,0.8,-1,1.2,0,
WSPro=,,,, 1 ,,,, 0 ,,,, 0 ,,,,-1 ,-1 ,-1 , 0 , 0 , 0 , 0 , 0
BC Design=,, 0 ,, 0 ,,,,,,
BC Use User HTab Curves=0
BC User HTab FreeFlow(D)= 0

Type RM Length L Ch R = 1 ,48759.05,640.67,659.79,685.02
BEGIN DESCRIPTION:
Downstream Section - LAKES OF BRIDGE DR
END DESCRIPTION:
Node Name=W
XS GIS Cut Line= 6
3000826.3541711913861460.30579243000776.9484301113861240.8859557
3000630.8007565313861002.3565771 2999753.427183213860391.9562231
2999323.6786988713859771.11100812999131.0813150313859596.2918039
#Sta/Elev= 30
       0  128.05  215.88  127.83  309.04  126.89  328.81  125.47  363.41  126.93
   402.8  125.07   432.3  126.97  591.39  125.31  730.71  125.35  898.58  127.17
  923.26  126.78  933.14  124.45  952.89  127.11  992.56  127.65 1002.53   126.7
 1027.44  117.32 1047.36   113.8 1066.42  107.45 1067.29  109.69 1081.99  114.31
 1126.07  115.75 1170.16  127.25 1194.79  129.23 1372.42  126.93 1921.84  127.06
 2021.62  125.45 2041.58  126.77 2091.46   127.4 2399.72  127.92 2596.03  129.52
#Mann= 6 ,-1 , 0
       0     .07       0  215.88     .15       0  591.39     .07       0
 1002.53     .04       0 1170.16     .07       0 1194.79     .15       0
#XS Ineff= 4 ,-1
       0   432.3   126.5   432.3 1004.92  125.67 1164.71 1921.84  126.15
 1921.84 2596.03   126.5
Permanent Ineff=
       F       F       F       F
Bank Sta=1002.53,1170.16
XS Rating Curve= 0 ,0
Exp/Cntr=0.5,0.3