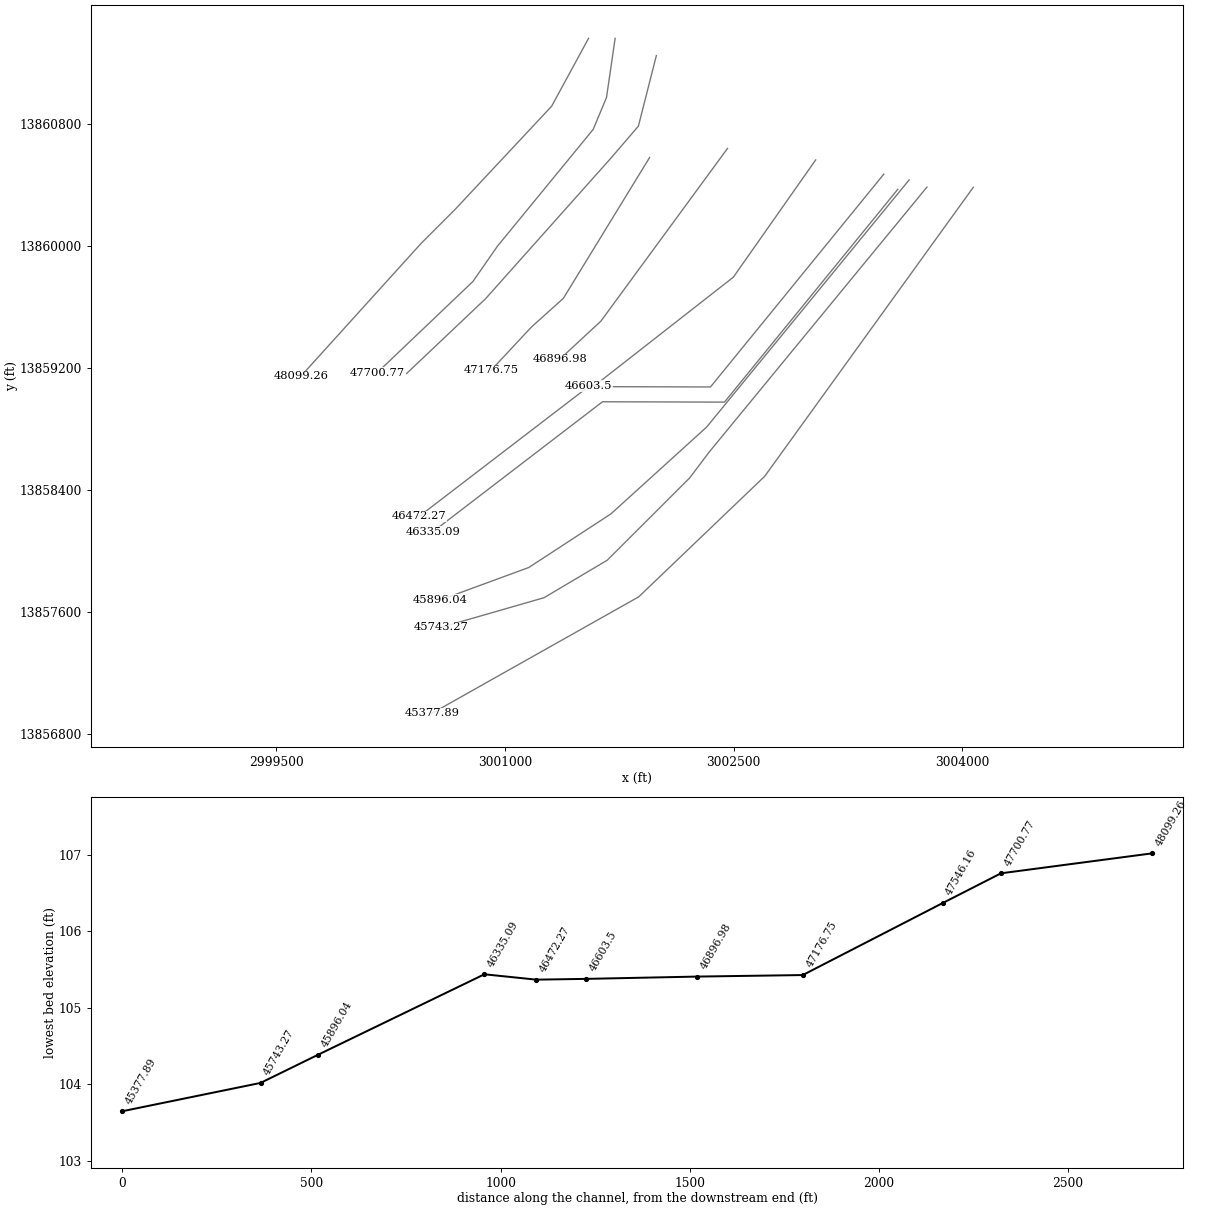
HEC-RAS study U101-00-00.prj: U101-00-00 2019 (Re-Study)

--- U101-00-00.g01 (geometry) --- (continued)

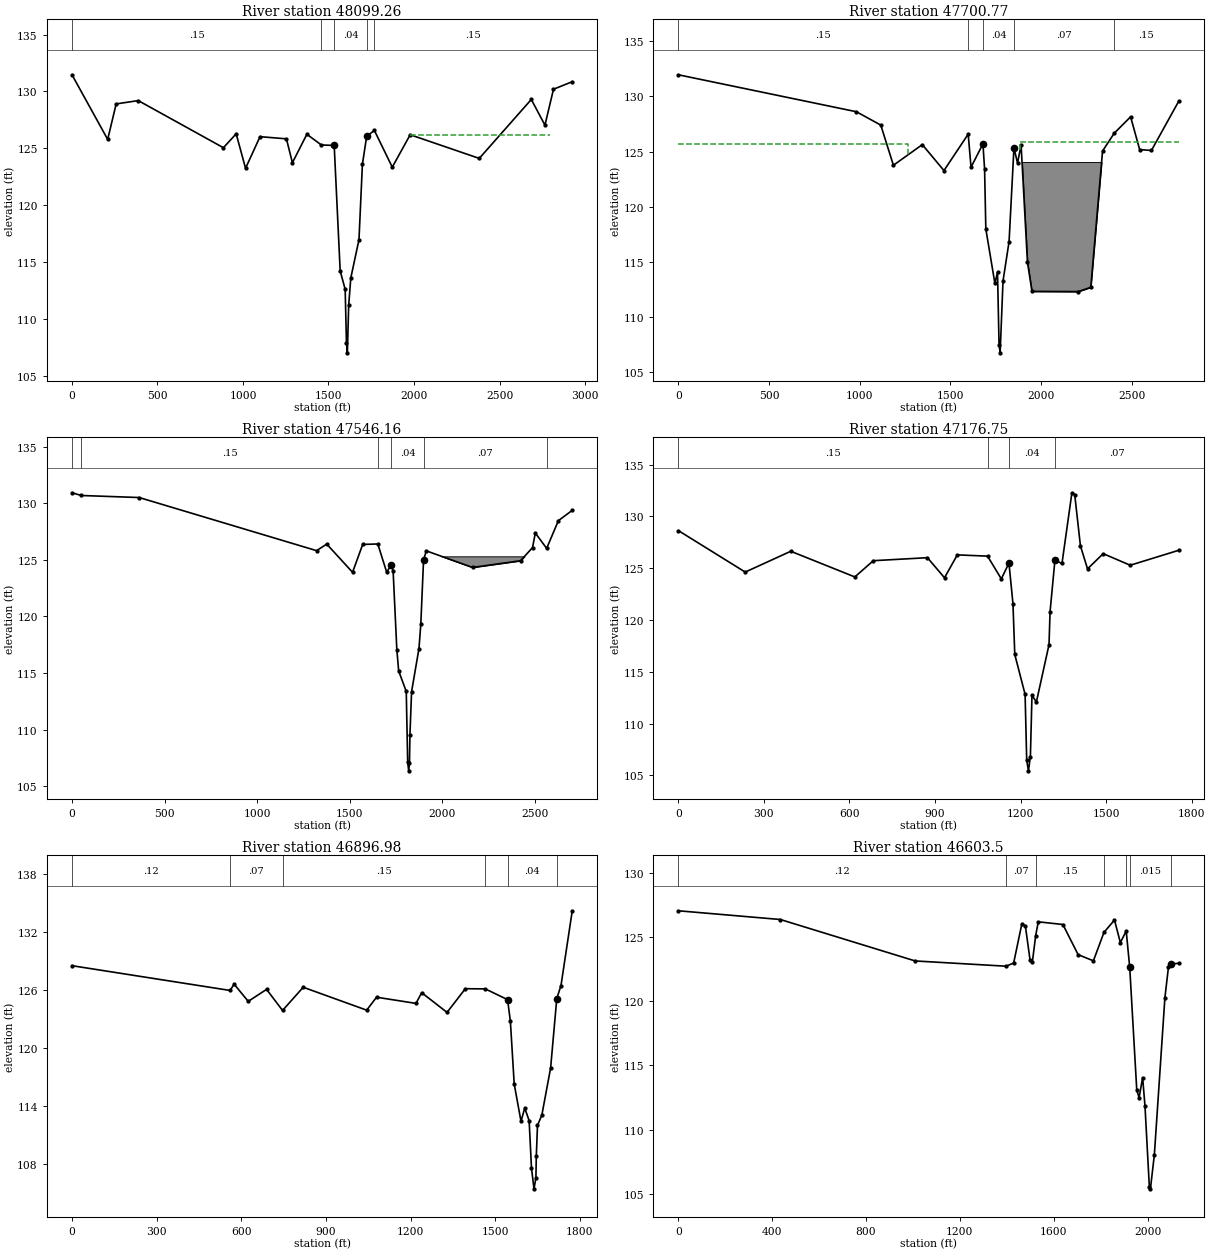
Type RM Length L Ch R = 1 ,48099.26,385.7,398.49,413.66
XS GIS Cut Line= 5
3001549.05121662 13861363.1350553001306.9234200313860917.8669167
3000677.4200858613860244.90008683000451.2200789513860018.7000799
 2999661.340425113859145.9108149
#Sta/Elev= 30
       0  131.46   208.7  125.78  258.39   128.9  387.59  129.19   885.4  125.05
  960.12  126.27 1014.91  123.24 1099.59  126.02 1254.01  125.83 1288.87  123.73
 1373.55  126.23 1458.35  125.29 1533.31  125.25  1568.3  114.22 1597.51   112.6
 1604.94  107.91 1610.25  107.02 1618.11  111.22 1630.43   113.6 1678.26  116.97
 1698.26  123.59 1723.25  126.05 1768.19  126.57 1872.94  123.34 1977.68  126.19
 2381.71  124.11 2685.97  129.29 2765.78  127.03 2815.66  130.19  2925.4  130.85
#Mann= 5 ,-1 , 0
       0     .15       0 1458.35     .07       0 1533.31     .04       0
 1723.25     .07       0 1768.19     .15       0
#XS Ineff= 3 ,-1
       0  263.36     128  263.36 1189.25   125.5 1977.68 2795.34   126.2
Permanent Ineff=
       F       F       F
Bank Sta=1533.31,1723.25
XS Rating Curve= 0 ,0
Exp/Cntr=0.3,0.1

Type RM Length L Ch R = 1 ,47700.77,163.8,154.61,144.99
XS GIS Cut Line= 6
3001723.41569728 13861363.1350553001666.7471754413860975.1735606
3001579.4556833713860765.96367723000951.3099580313859999.6899473
3000790.9999111913859768.79998913000162.0940167813859169.6151638
#Sta/Elev= 30
       0  131.96  982.24  128.61 1116.67   127.4 1186.38  123.76 1345.71  125.63
 1465.21  123.28 1598.88  126.58 1614.53  123.58 1680.17   125.7 1689.27  123.41
 1696.18  117.98 1746.17  113.05 1760.55  114.07 1769.03  107.51  1775.1  106.76
 1790.92  113.27 1824.34  116.84 1851.24  125.34 1870.96  123.96 1890.69  125.59
 1925.63  114.99  1950.6  112.33  2205.2  112.31 2275.09   112.7 2339.98  125.05
  2404.6  126.67 2494.74  128.15 2544.66  125.18 2609.56   125.1 2759.32  129.54
#Mann= 5 ,-1 , 0
       0     .15       0 1598.88     .07       0 1680.17     .04       0
 1851.24     .07       0  2404.6     .15       0
#XS Ineff= 2 ,-1
       0 1266.06  125.67 1885.76 2759.32  125.85
Permanent Ineff=
       F       F
#Block Obstruct= 1 ,-1
 1885.76 2339.98  124.05
Bank Sta=1680.17,1851.24
XS Rating Curve= 0 ,0
Exp/Cntr=0.3,0.1

Type RM Length L Ch R = 1 ,47546.16,372.08,369.41,354.45
XS GIS Cut Line= 5
3001993.6809047813861249.79801133001875.9098148613860787.1811544
3001696.2602397813860578.02409243000874.1014510213859655.9344012
3000356.2776835313859165.3645162
#Sta/Elev= 30
       0  130.92   50.74  130.68     363   130.5 1320.97  125.81 1375.77  126.39
 1515.25   123.9 1570.04  126.36 1651.59   126.4 1699.56  123.91 1724.47  124.56
 1734.43  123.98 1754.36  117.08 1764.32  115.19 1805.25  113.38 1813.06  107.11
 1818.64  106.37 1822.71  107.08 1825.17  109.53 1834.06  113.36 1873.91  117.17
 1883.87  119.31 1898.82  125.01 1913.76  125.79 2163.07  124.33 2422.46  124.92
  2487.3  126.08 2502.27  127.37 2563.59  126.01 2626.97  128.46 2701.79  129.37
#Mann= 6 ,-1 , 0
       0     .07       0   50.74     .15       0 1651.59     .07       0
 1724.47     .04       0 1898.82     .07       0 2563.59     .15       0
#XS Ineff= 2 ,-1
       0 1644.77   125.7 1913.76 2701.79   125.7
Permanent Ineff=
       F       F
#Block Obstruct= 1 ,-1
 1913.76 2482.31  125.31
Bank Sta=1724.47,1898.82
XS Rating Curve= 0 ,0
Exp/Cntr=0.3,0.1

Type RM Length L Ch R = 1 ,47176.75,278.35,279.77,280.56
XS GIS Cut Line= 4
3001949.4943133613860581.68320593001383.8399328613859657.8901059
3001174.1277538513859469.34914443000908.6384554513859184.8900677
#Sta/Elev= 30
       0  128.64  234.61  124.63  394.35  126.64  618.98  124.16  683.87  125.73
  873.56  126.02  933.46  124.08  978.39  126.29 1084.45  126.17 1132.69  123.97
 1159.45   125.5 1173.52  121.58 1179.88  116.67 1216.05  112.82 1221.72  106.45
 1227.84  105.43 1234.65  106.81 1240.21  112.72 1255.69  112.08 1299.95  117.62
 1303.63   120.8 1320.69  125.78 1345.43  125.46 1380.19  132.29 1390.16   132.1
 1410.12  127.16 1435.06  124.94 1489.93  126.41 1584.71  125.29 1754.32  126.73
#Mann= 4 ,-1 , 0
       0     .15       0 1084.45     .07       0 1159.45     .04       0
 1320.69     .07       0
#XS Ineff= 1 ,-1
       0  978.39     125
Permanent Ineff=
       F
Bank Sta=1159.45,1320.69
XS Rating Curve= 0 ,0
Exp/Cntr=0.3,0.1

Type RM Length L Ch R = 1 ,46896.98,299.52,293.47,284.35
Node Name=V
XS GIS Cut Line= 3
3002460.4181602713860641.06727343001630.1133904513859508.4934231
3001359.4991022813859257.8475989
#Sta/Elev= 30
       0  128.49  560.28  125.93  574.72  126.58   624.7   124.8  689.67  126.04
  746.34  123.86  819.61  126.26  1044.5  123.89 1079.48  125.23 1219.42  124.59
 1239.41   125.7 1329.36  123.66 1394.33  126.11 1464.96  126.09  1543.9  124.98
 1553.86  122.76 1567.46  116.25 1591.49   112.4 1604.89  113.76 1620.37  112.46
 1628.67  107.56 1637.62  105.41 1644.43  106.56 1645.79  108.79 1649.99  111.97
 1665.46  113.04 1696.56  117.92 1718.36  125.09 1733.31  126.44 1773.19  134.17
#Mann= 6 ,-1 , 0
       0     .12       0  560.28     .07       0  746.34     .15       0
 1464.96     .07       0  1543.9     .04       0 1718.36     .07       0
#XS Ineff= 1 ,-1
       0  819.61     125
Permanent Ineff=
       F
Bank Sta=1543.9,1718.36
XS Rating Curve= 0 ,0
Exp/Cntr=0.3,0.1

Type RM Length L Ch R = 1 ,46603.5 ,170.02,131.23,21.91
BEGIN DESCRIPTION:
CONFLUENCE WITH U101-07-00
END DESCRIPTION:
XS GIS Cut Line= 4
3003038.4731065313860565.44406513002498.5414436213859796.5587918
3001593.1685824413859088.5565989 3001550.275951713859082.7032642
#Sta/Elev= 30
       0  127.05  434.78  126.37 1009.49  123.14  1397.5  122.73 1429.24  122.98
 1464.22  126.04 1479.22  125.87  1499.2   123.2  1509.2  123.09  1523.1  125.12
 1534.18  126.19 1639.12  125.98 1704.09  123.63 1769.05  123.15 1814.25  125.37
    1859  126.33 1883.98  124.57 1908.97  125.47 1923.96  122.63 1953.94  113.07
 1963.94  112.49 1978.93  114.05 1988.92  111.85 2007.47  105.56 2012.14  105.38
  2028.9  108.03 2073.87  120.28 2088.87  122.64 2098.49  122.89 2132.16  122.96
#Mann= 7 ,-1 , 0
       0     .12       0  1397.5     .07       0  1523.1     .15       0
 1814.25     .07       0 1908.97     .04       0 1923.96    .015       0
 2098.49     .07       0
#XS Ineff= 1 ,-1
       0 1549.18     125
Permanent Ineff=
       F
Bank Sta=1923.96,2098.49
XS Rating Curve= 0 ,0
Exp/Cntr=0.5,0.3

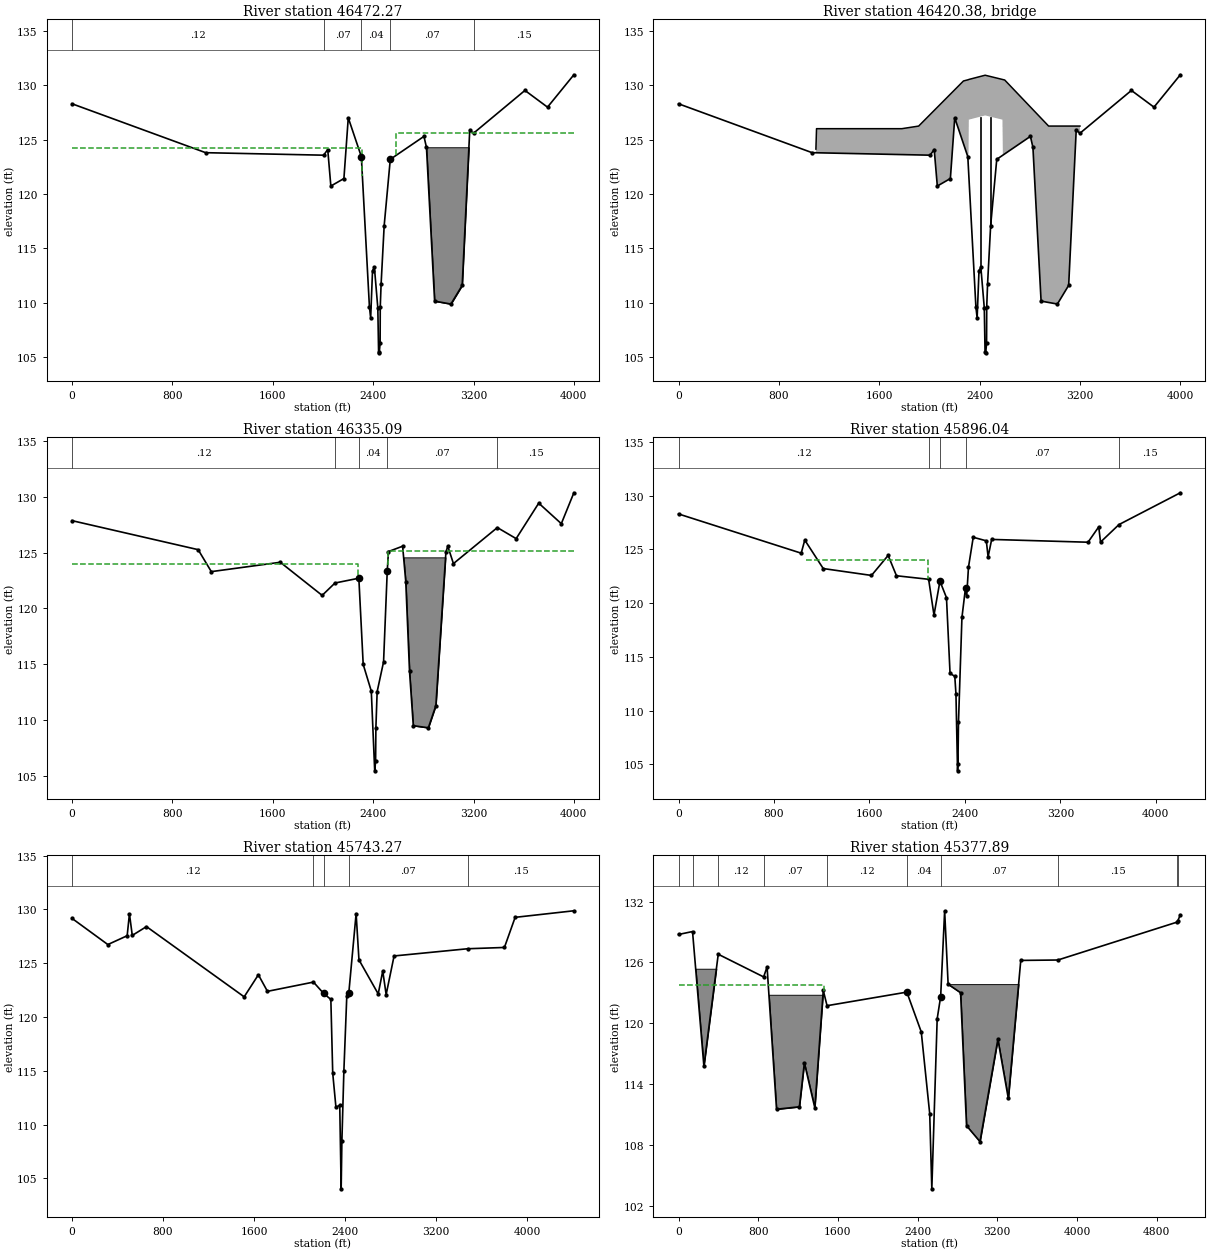
Type RM Length L Ch R = 1 ,46472.27,252.26,137.18,150.22
BEGIN DESCRIPTION:
Upstream Section - MORTON ROAD
END DESCRIPTION:
XS GIS Cut Line= 5
  3003485.39478413860472.3648549 3002348.767136913859076.6294574
 3001738.769669213859078.4096376 3001548.770377313859078.9640984
 3000437.523912113858227.4179013
#Sta/Elev= 30
       0  128.29    1065  123.79  2005.4  123.56 2038.05  124.08 2062.85  120.72
 2166.99  121.41 2201.71     127 2305.85  123.43 2370.32  109.61 2380.24  108.57
 2395.12  112.94 2409.99  113.24 2437.31   109.5 2443.34  105.49 2448.54  105.37
 2455.54  106.24  2456.7   109.6 2463.58  111.73 2487.94  117.08 2536.66  123.18
    2805  125.29    2825  124.28    2890  110.13    3020  109.86    3110  111.58
 3170.01  125.85 3200.01  125.58 3610.01  129.52 3790.01  127.98    4000  130.96
#Mann= 5 ,-1 , 0
       0     .12       0  2005.4     .07       0 2305.85     .04       0
 2536.66     .07       0 3200.01     .15       0
#XS Ineff= 2 ,-1
       0    2314  124.25    2582    4000  125.58
Permanent Ineff=
       F       F
#Block Obstruct= 1 ,-1
    2805 3170.01  124.29
Bank Sta=2305.85,2536.66
XS Rating Curve= 0 ,0
Exp/Cntr=0.5,0.3

Type RM Length L Ch R = 3 ,46420.38,,,
BEGIN DESCRIPTION:
MORTON ROAD
END DESCRIPTION:
Node Name=MORTON ROAD
Bridge Culvert--1,0,-1,-1, 0
Deck Dist Width WeirC Skew NumUp NumDn MinLoCord MaxHiCord MaxSubmerge Is_Ogee
10,110,2.6,0, 13, 12, , , 0.98, 0, 0,0,,
    1095    1100    1780 1914.06 2271.14 2310.81    2314  2444.1    2582 2585.38
    2600    2950    3200
  124.12     126     126  126.24  130.39  130.51  130.53  130.92  130.53  130.52
  130.48  126.24  126.24
       0       0       0       0       0       0  126.83  127.22  126.83       0
       0       0       0
    1095    1740 1874.39 2231.46 2276.09 2277.93 2409.99 2545.93 2546.41    2600
    2950    3200
     126     126  126.23  130.35  130.52  130.53  130.93  130.53  130.53  130.37
  126.24  126.24
       0       0       0       0       0  126.83  127.23     126       0       0
       0       0
Pier Skew, UpSta & Num, DnSta & Num=  ,2407, 4 ,2370.93, 4 , 3 , 3 , 0 ,,
       2       2     2.5     2.5
     105   127.3   127.3   130.3
       2       2     2.5     2.5
     105   127.3   127.3   130.3
Pier Skew, UpSta & Num, DnSta & Num=  ,2487, 4 ,2450.93, 4 , 3 , 3 , 0 ,,
       2       2     2.5     2.5
     105   127.3   127.3   130.3
       2       2     2.5     2.5
     105   127.3   127.3   130.3
Abutment Skew #Up #Dn= , 3 , 3
  2313.5    2314 2320.99
  126.83  126.83  125.39
 2277.43 2277.93 2338.37
  126.83  126.83  123.24
Abutment Skew #Up #Dn= , 3 , 4
 2553.63    2582  2582.5
  122.78  126.83  126.83
 2486.55 2487.07 2515.17    2546
  123.51  123.51  126.32  126.32
BR Coef=-1 , 1 , 1 ,0.9, 0 ,,,0.8,-1,1.2,0,
WSPro=,,,, 1 ,,,, 0 ,,,, 0 ,,,,-1 ,-1 ,-1 , 0 , 0 , 0 , 0 , 0
BC Design=,, 0 ,, 0 ,,,,,,
BC Use User HTab Curves=0
BC User HTab FreeFlow(D)= 0

Type RM Length L Ch R = 1 ,46335.09,288.36,439.05,528.88
BEGIN DESCRIPTION:
Downstream Section - MORTON ROAD
END DESCRIPTION:
XS GIS Cut Line= 5
   3003577.21153 13860372.991366 3002440.583882413858977.2559685
 3001830.586414713858979.0361487 3001640.587122813858979.5906095
 3000529.340657613858128.0444124
#Sta/Elev= 30
       0  127.87    1005  125.27    1110   123.3    1660  124.14 1993.42  121.17
 2095.95  122.28 2286.01  122.71 2320.73  114.98  2385.2  112.59 2412.47  105.44
 2419.62  106.31 2421.88   109.3  2431.9  112.54 2483.07  115.21  2512.3  123.33
 2522.05   125.1    2635  125.58    2660   122.4    2690  114.36    2720  109.49
    2840   109.3    2900  111.29    2980  125.05    2995  125.58    3040  124.02
 3390.01  127.25 3540.01  126.26 3720.01  129.44 3900.01   127.6    4000  130.37
#Mann= 5 ,-1 , 0
       0     .12       0 2095.95     .07       0 2286.01     .04       0
  2512.3     .07       0 3390.01     .15       0
#XS Ineff= 2 ,-1
       0 2277.93     124 2515.17    4000  125.11
Permanent Ineff=
       F       F
#Block Obstruct= 1 ,-1
    2635    2995  124.58
Bank Sta=2286.01,2512.3
XS Rating Curve= 0 ,0
Exp/Cntr=0.5,0.3

Type RM Length L Ch R = 1 ,45896.04,123.12,152.77,167.52
Node Name=U
XS GIS Cut Line= 5
3003651.7622342713860434.81178043002323.4138411113858813.4232909
 3001695.887865213858244.2938518 3001157.233430713857892.6882558
3000576.2454194413857679.3566614
#Sta/Elev= 30
       0  128.29 1028.06  124.64    1058  125.86 1212.71  123.21 1616.95  122.57
 1756.69  124.43 1826.56  122.54 2096.05  122.21  2140.9  118.88 2190.73  122.04
 2245.55   120.5 2275.45  113.46 2315.31  113.18 2324.97  111.54 2338.34  104.39
 2341.81  105.05 2346.15   108.9 2375.11  118.66 2405.01  121.41 2414.98  120.65
 2429.93  123.34 2469.79  126.12 2579.43  125.79 2594.38   124.3 2624.28  125.92
 3431.88  125.66 3521.63  127.09 3536.59  125.67 3690.99   127.3 4205.37  130.26
#Mann= 5 ,-1 , 0
       0     .12       0 2096.05     .07       0 2190.73     .04       0
 2405.01     .07       0 3690.99     .15       0
#XS Ineff= 3 ,-1
       0 1067.99   125.5 1067.99 2094.25     124 2469.79 4205.37   125.5
Permanent Ineff=
       F       F       F
Bank Sta=2190.73,2405.01
XS Rating Curve= 0 ,0
Exp/Cntr=0.3,0.1

Type RM Length L Ch R = 1 ,45743.27,399.99,365.39,375.87
XS GIS Cut Line= 6
3003768.2577361913860387.35058933002341.08014436 13858650.920007
3002211.2900496113858479.0299308 3001671.819015713857940.5175564
3001256.9533756113857694.40256313000579.4481689513857499.3589899
#Sta/Elev= 30
       0  129.16  314.67  126.73   484.5  127.55  504.48  129.59  529.45  127.58
  654.32   128.4 1513.43  121.87  1638.3  123.92 1718.22  122.38  2122.8  123.24
 2212.71  122.18 2275.72  121.63 2292.18  114.77 2320.48   111.6  2353.9  111.79
 2366.47  104.02 2372.76  108.45 2390.37  115.02 2415.96  121.96 2433.69  122.24
 2497.93  129.61 2522.84  125.31 2692.23  122.14 2732.08  124.27 2761.97  122.08
 2831.72  125.67 3478.24  126.34 3802.01  126.46 3896.34  129.26  4412.7  129.87
#Mann= 5 ,-1 , 0
       0     .12       0  2122.8     .07       0 2212.71     .04       0
 2433.69     .07       0 3478.24     .15       0
#XS Ineff= 1 ,-1
 2497.93  4412.7   124.5
Permanent Ineff=
       F
Bank Sta=2212.71,2433.69
XS Rating Curve= 0 ,0
Exp/Cntr=0.3,0.1

Type RM Length L Ch R = 1 ,45377.89,1080.73,1026.27,1061.77
Node Name=T
XS GIS Cut Line= 4
3004072.42018561 13860386.1724423002704.4183284513858490.9196709
 3001877.917028713857700.04329993000521.0355561113856935.8450251
#Sta/Elev= 30
       0  128.76  140.59  129.05  254.72  115.76  398.77  126.81   854.5  124.57
  889.01  125.56   983.9  111.51 1213.65  111.75 1263.59  116.09 1368.47  111.65
 1453.38  123.24 1491.19  121.73 2292.44  123.07  2437.3  119.14 2522.22  111.06
  2543.3  103.65 2597.15  120.44 2632.12  122.63 2672.08   131.1 2707.05  123.85
 2831.94  123.01 2891.88  109.88 3026.76  108.31  3206.6  118.41  3311.5  112.57
 3436.39   126.2 3809.05  126.24 5008.83  129.99    5011  130.06 5038.62   130.7
#Mann= 10 ,-1 , 0
       0     .15       0  140.59     .07       0  398.77     .12       0
   854.5     .07       0 1491.19     .12       0 2292.44     .04       0
 2632.12     .07       0 3809.05     .15       0 5008.83     .07       0
    5011     .15       0
#XS Ineff= 2 ,-1
       0 1463.37  123.81 2672.08 5038.62   124.5
Permanent Ineff=
       F       F
#Block Obstruct= 3 ,-1
  140.59  398.77  125.38  874.02 1463.37  122.81 2672.08 3471.36  123.86
Bank Sta=2292.44,2632.12
XS Rating Curve= 0 ,0
Exp/Cntr=0.3,0.1