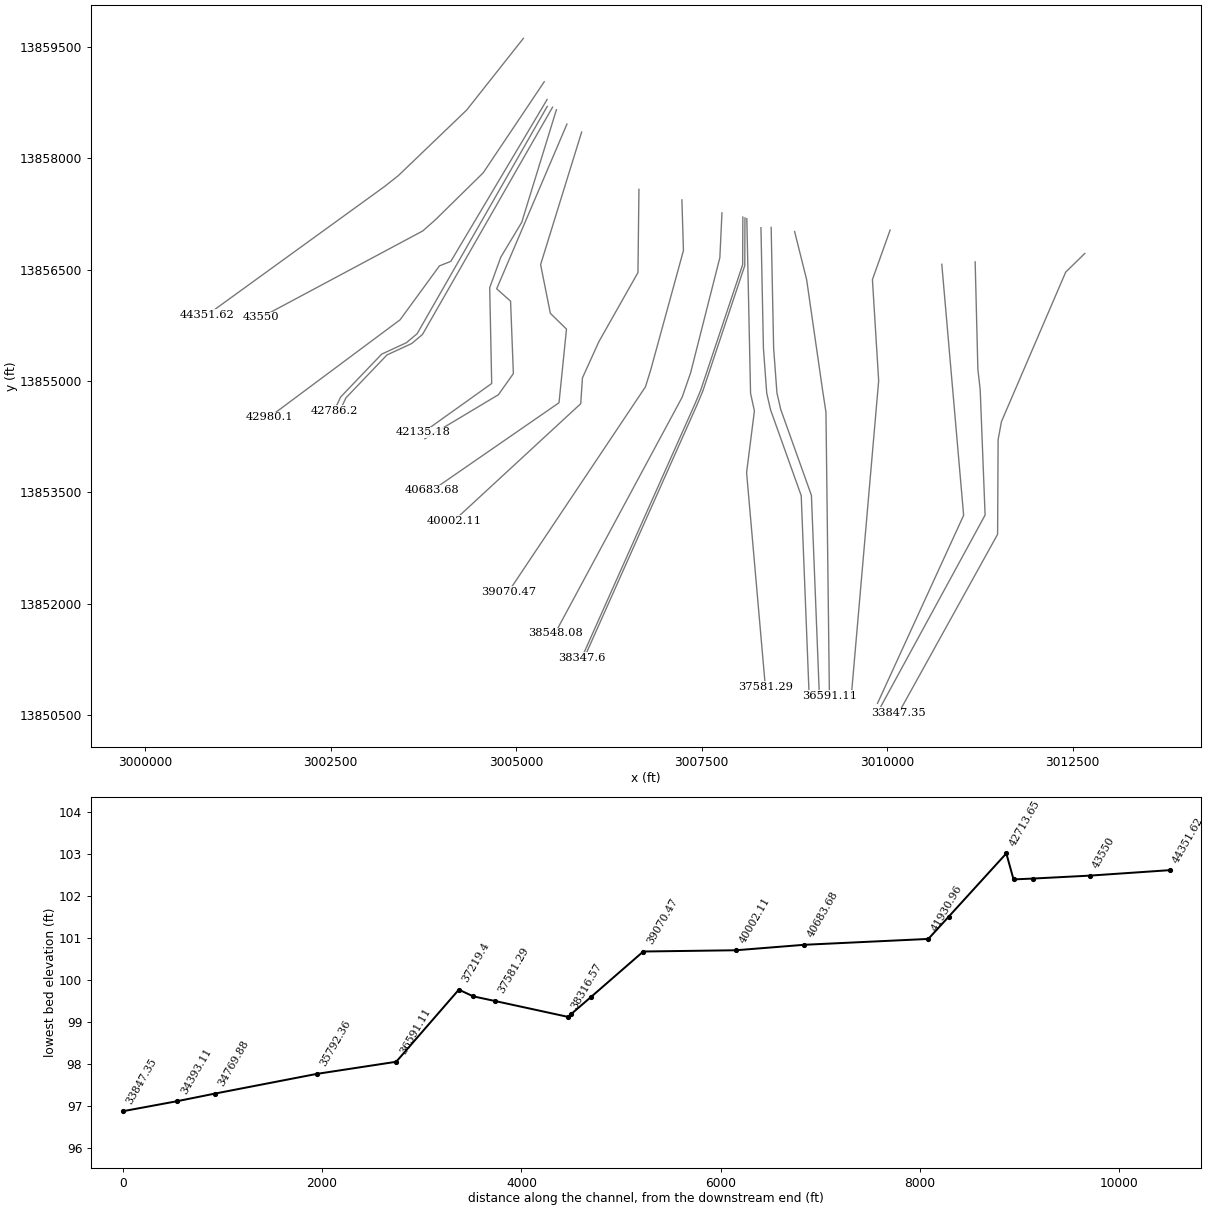
HEC-RAS study U101-00-00.prj: U101-00-00 2019 (Re-Study)

--- U101-00-00.g01 (geometry) --- (continued)

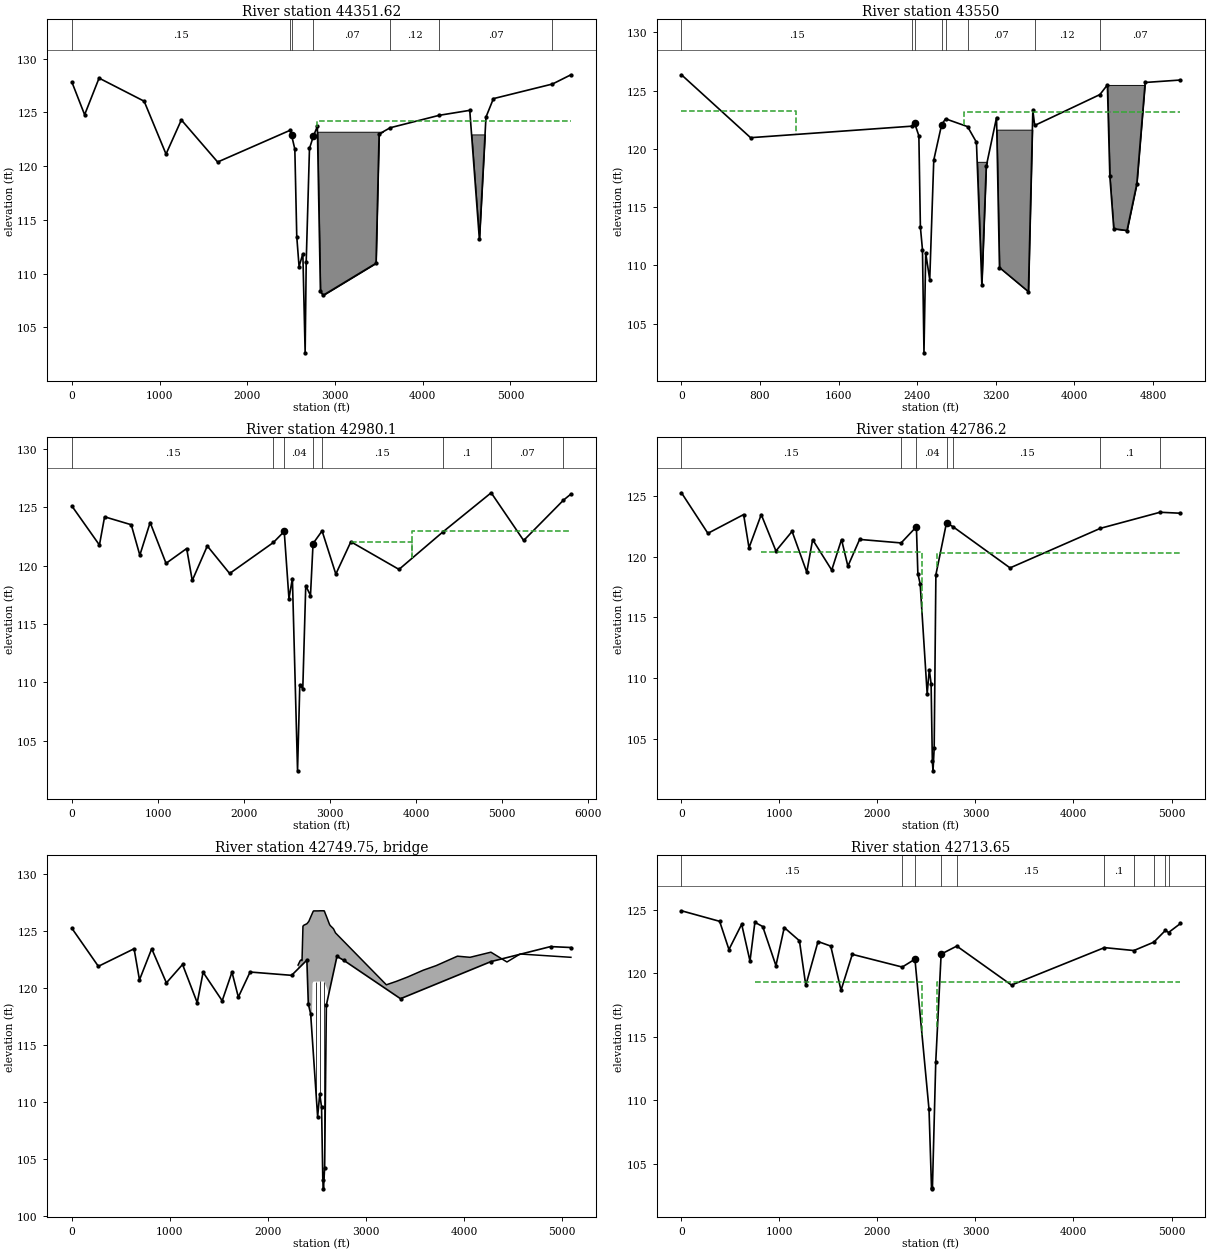
Type RM Length L Ch R = 1 ,44351.62,787.61,801.62,795.17
Node Name=S
XS GIS Cut Line= 5
3005098.9273189513859618.18841373004334.1745833613858651.4892316
3003412.7600876113857767.78988353003225.0898592813857619.5798781
3000842.8885869413855894.7312937
#Sta/Elev= 30
       0  127.81  144.72  124.78   309.4  128.19  823.41  126.04 1072.93  121.12
 1247.58   124.3 1661.51  120.38 2489.37  123.34 2504.33  122.88 2541.53  121.58
 2563.56  113.43 2589.82  110.65 2632.99  111.84 2659.08  102.62 2671.32   111.1
  2708.6  121.65 2753.45  122.79 2798.39   123.7 2833.34  108.36  2863.3  107.97
 3467.49  110.96 3502.45  122.99 3629.07  123.57 4189.39  124.73 4536.07  125.19
 4645.93  113.17 4720.83  124.56 4805.72  126.28 5479.05  127.64 5689.55   128.5
#Mann= 7 ,-1 , 0
       0     .15       0 2489.37     .07       0 2504.33     .04       0
 2753.45     .07       0 3629.07     .12       0 4189.39     .07       0
 5479.05      .1       0
#XS Ineff= 2 ,-1
       0 1247.58   124.3  2793.4 5689.55   124.2
Permanent Ineff=
       F       F
#Block Obstruct= 2 ,-1
  2793.4 3562.37   123.2 4536.07 4730.81  122.95
Bank Sta=2504.33,2753.45
XS Rating Curve= 0 ,0
Exp/Cntr=0.3,0.1

Type RM Length L Ch R = 1 ,43550   ,582.14,569.9,587.11
Node Name=R
XS GIS Cut Line= 5
3005379.4333196113859032.78472893004557.09835011 13857806.079177
3003910.0199198613857170.56010693003741.6298366913857022.3501014
3001562.1076209413855857.4223132
#Sta/Elev= 30
       0  126.36  703.49  120.96 2348.24  121.95 2373.84  122.19 2416.57  121.12
  2432.1  113.28 2453.21  111.35 2468.58  102.49 2486.37  111.06  2527.2  108.77
 2568.24  119.04 2648.08  122.07 2688.02  122.58 2912.34  121.91 3002.55  120.57
 3057.47  108.35  3102.4   118.5 3207.25  122.69  3237.2  109.81 3531.76  107.74
  3576.7  123.31 3595.35  122.01 4259.26  124.66 4335.56  125.49 4360.53  117.63
 4400.47  113.14 4535.26  112.99 4635.11  116.99 4719.99   125.7 5079.45  125.91
#Mann= 8 ,-1 , 0
       0     .15       0 2348.24     .07       0 2373.84     .04       0
 2648.08     .07       0 2688.02     .15       0 2912.34     .07       0
 3595.35     .12       0 4259.26     .07       0
#XS Ineff= 2 ,-1
       0  1167.5  123.21 2872.74 5079.45  123.14
Permanent Ineff=
       F       F
#Block Obstruct= 3 ,-1
 3002.55 3112.39  118.89 3202.25  3576.7  121.65 4335.56 4719.99  125.49
Bank Sta=2373.84,2648.08
XS Rating Curve= 0 ,0
Exp/Cntr=0.3,0.1

Type RM Length L Ch R = 1 ,42980.1 ,104.83,193.9,232.44
XS GIS Cut Line= 5
3005418.1218905313858793.69432783004121.2599829413856613.3499352
3003967.6700670313856552.31987353003437.8158117813855826.3590551
3001675.0598228613854513.8830055
#Sta/Elev= 30
       0  125.12  319.61  121.78  379.53   124.2  689.15  123.52  789.03  120.91
  908.88  123.71 1093.65  120.21 1333.36  121.48 1398.28  118.74 1573.06   121.7
 1832.74  119.34 2341.33     122 2466.97  122.95  2521.9  117.19 2561.99  118.91
 2621.75  102.42 2647.88  109.76 2682.71  109.46 2717.13   118.3 2772.06  117.45
 2802.01  121.91 2906.87  122.99 3066.65  119.29 3241.41  122.06 3800.71  119.69
 4308.61  122.89 4871.86  126.26 5249.18  122.17 5712.11  125.63  5798.6  126.15
#Mann= 8 ,-1 , 0
       0     .15       0 2341.33     .07       0 2466.97     .04       0
 2802.01     .07       0 2906.87     .15       0 4308.61      .1       0
 4871.86     .07       0 5712.11     .15       0
#XS Ineff= 3 ,-1
       0  908.88   123.5 3241.41 3950.56  122.06 3950.56  5798.6  122.95
Permanent Ineff=
       F       F       F
Bank Sta=2466.97,2802.01
XS Rating Curve= 0 ,0
Exp/Cntr=0.5,0.3

Type RM Length L Ch R = 1 ,42786.2 ,74.89,72.54,70.98
BEGIN DESCRIPTION:
Upstream Section - RAINTREE VILLAGE DR
END DESCRIPTION:
XS GIS Cut Line= 6
3005420.15141402 13858701.5655753003667.0728991913855638.3594311
3003521.2775871213855516.36754913003189.2106659413855363.1929867
3002636.76393619 13854785.7820683002548.3166065213854599.9395919
#Sta/Elev= 30
       0  125.24  269.68  121.91  634.25  123.45  689.18  120.72  814.03  123.45
  963.86  120.46 1128.66  122.07 1278.48  118.72 1338.41  121.39 1533.18  118.89
 1633.06   121.4 1697.99  119.21 1817.84  121.41 2241.26  121.12 2397.16  122.45
 2412.05   118.6 2435.72  117.74 2506.99  108.73 2528.63  110.71 2547.08  109.57
 2559.86   103.2 2566.64   102.4 2578.52  104.26 2595.97  118.51 2704.35  122.78
 2774.54  122.43  3352.7  119.07 4274.46  122.32  4883.4  123.64 5091.48  123.56
#Mann= 7 ,-1 , 0
       0     .15       0 2241.26     .07       0 2397.16     .04       0
 2704.35     .07       0 2774.54     .15       0 4274.46      .1       0
  4883.4     .07       0
#XS Ineff= 3 ,-1
       0  809.04   122.6  809.04 2454.74  120.34 2612.11 5091.48  120.29
Permanent Ineff=
       F       F       F
Bank Sta=2397.16,2704.35
XS Rating Curve= 0 ,0
Exp/Cntr=0.5,0.3

Type RM Length L Ch R = 3 ,42749.75,,,
BEGIN DESCRIPTION:
RAINTREE VILLAGE DR
END DESCRIPTION:
Node Name=RAINTREE VILLAGE
Bridge Culvert--1,0,-1,-1, 0
Deck Dist Width WeirC Skew NumUp NumDn MinLoCord MaxHiCord MaxSubmerge Is_Ogee
10.5,54,2.6,0, 60, 60, , , 0.98, 0, 0,0,,
 2307.27 2327.24 2337.23 2347.22 2348.33 2357.21 2367.19 2372.19 2377.18 2392.16
 2397.16    2417 2431.85 2446.69 2454.74 2461.54 2466.49 2471.44 2476.39 2481.34
 2491.24 2496.19 2501.13 2506.08 2511.03 2515.98 2530.83 2540.73 2545.68 2550.62
 2555.57 2560.52 2565.39 2570.26 2575.14 2580.01 2584.88 2589.75 2594.62 2612.11
 2614.57 2619.56 2624.55 2629.53 2639.51 2649.48 2664.45 2669.43 2689.45  3208.1
 3312.84 3426.88 3584.35 3715.96 3933.33 4061.82    4275 4438.68 4572.78 5091.47
  122.02  122.38  122.47  122.41   122.6  125.43  125.52  125.54  125.56  125.62
  125.64  125.85  126.15  126.44   126.6  126.73  126.77  126.77  126.77  126.77
  126.77  126.77  126.77  126.77  126.77  126.77  126.78  126.78  126.78  126.78
  126.78  126.78  126.78  126.78  126.77  126.66  126.55  126.44  126.34  125.95
  125.89  125.78  125.67  125.56  125.45  125.37  125.24  125.19  124.84  120.29
   120.6  120.98  121.57  121.97   122.8   122.7  123.15  122.29  122.99   122.7
       0       0       0       0       0       0       0       0       0       0
       0       0       0       0   120.4  120.53  120.57  120.57  120.57  120.57
  120.57  120.57  120.57  120.57  120.57  120.57  120.58  120.58  120.58  120.58
  120.58  120.58  120.58  120.58  120.57  120.46  120.35  120.24  120.14  119.75
       0       0       0       0       0       0       0       0       0       0
       0       0       0       0       0       0       0       0       0       0
 2307.27 2327.24 2337.23 2347.22 2348.33 2357.21 2367.19 2372.19 2377.18 2392.16
 2397.16    2417 2431.85 2446.69 2454.74 2461.54 2466.49 2471.44 2476.39 2481.34
 2491.24 2496.19 2501.13 2506.08 2511.03 2515.98 2530.83 2540.73 2545.68 2550.62
 2555.57 2560.52 2565.39 2570.26 2575.14 2580.01 2584.88 2589.75 2594.62 2612.11
 2614.57 2619.56 2624.55 2629.53 2639.51 2649.48 2664.45 2669.43 2689.45  3208.1
 3312.84 3426.88 3584.35 3715.96 3933.33 4061.82    4275 4438.68 4572.78 5091.47
  122.02  122.38  122.47  122.41   122.6  125.43  125.52  125.54  125.56  125.62
  125.64  125.85  126.15  126.44   126.6  126.73  126.77  126.77  126.77  126.77
  126.77  126.77  126.77  126.77  126.77  126.77  126.78  126.78  126.78  126.78
  126.78  126.78  126.78  126.78  126.77  126.66  126.55  126.44  126.34  125.95
  125.89  125.78  125.67  125.56  125.45  125.37  125.24  125.19  124.84  120.29
   120.6  120.98  121.57  121.97   122.8   122.7  123.15  122.29  122.99   122.7
       0       0       0       0       0       0       0       0       0       0
       0       0       0       0  120.35  120.48  120.52  120.52  120.52  120.52
  120.52  120.52  120.52  120.52  120.52  120.52  120.53  120.53  120.53  120.53
  120.53  120.53  120.53  120.53  120.52  120.41   120.3  120.19  120.09   119.7
       0       0       0       0       0       0       0       0       0       0
       0       0       0       0       0       0       0       0       0       0
Pier Skew, UpSta & Num, DnSta & Num=  ,2493.74, 2 ,2493.74, 2 , 0 , 0 , 0 ,,
       2       2
     100     122
       2       2
     100     122
Pier Skew, UpSta & Num, DnSta & Num=  ,2532.54, 2 ,2532.54, 2 , 0 , 0 , 0 ,,
       2       2
     100     122
       2       2
     100     122
Pier Skew, UpSta & Num, DnSta & Num=  ,2572.54, 2 ,2572.54, 2 , 0 , 0 , 0 ,,
       2       2
     100     122
       2       2
     100     122
Abutment Skew #Up #Dn= , 3 , 3
 2453.54 2454.54  2455.6
   120.4   120.4  114.32
 2453.54 2454.54  2455.6
  120.35  120.35  114.27
Abutment Skew #Up #Dn= , 2 , 2
 2582.83 2612.31
  108.66  119.75
 2582.83 2612.31
  108.61   119.7
BR Coef=-1 , 1 , 1 ,0.9, 0 ,,,0.8,-1,1.2,0,
WSPro=,,,, 1 ,,,, 0 ,,,, 0 ,,,,-1 ,-1 ,-1 , 0 , 0 , 0 , 0 , 0
BC Design=,, 0 ,, 0 ,,,,,,
BC Use User HTab Curves=0
BC User HTab FreeFlow(D)= 0

Type RM Length L Ch R = 1 ,42713.65,516.14,578.48,589.5
BEGIN DESCRIPTION:
Downstream Section - RAINTREE VILLAGE DR
END DESCRIPTION:
Node Name=Q
XS GIS Cut Line= 6
3005491.7848009513858690.77655463003738.7062861213855627.5704107
3003592.9109740313855505.57852873003260.8440528713855352.4039663
3002708.3973231213854774.99304763002619.9499934513854589.1505715
#Sta/Elev= 30
       0  124.91  389.54  124.08  484.42  121.86  614.27  123.85  699.17  120.95
  749.11     124  829.02  123.67  963.86  120.59 1048.76  123.59 1203.57  122.55
 1268.49  119.04 1393.35  122.49 1523.19  122.13 1628.07  118.65 1742.93  121.48
  2252.7  120.48 2382.18   121.1 2525.88  109.27 2551.56  103.02 2560.52  103.06
 2594.62  113.02 2649.48   121.5 2809.28  122.13 3367.54  119.06 4315.42  122.01
 4615.92  121.78 4819.68  122.44  4938.6  123.37 4969.86   123.2 5091.47  123.91
#Mann= 10 ,-1 , 0
       0     .15       0  2252.7     .07       0 2382.18     .04       0
 2649.48     .07       0 2809.28     .15       0 4315.42      .1       0
 4615.92     .15       0 4819.68      .1       0  4938.6     .07       0
 4969.86     .15       0
#XS Ineff= 3 ,-1
       0  749.11   122.5  749.11 2454.74  119.34 2612.11 5091.47  119.29
Permanent Ineff=
       F       F       F
Bank Sta=2382.18,2649.48
XS Rating Curve= 0 ,0
Exp/Cntr=0.5,0.3

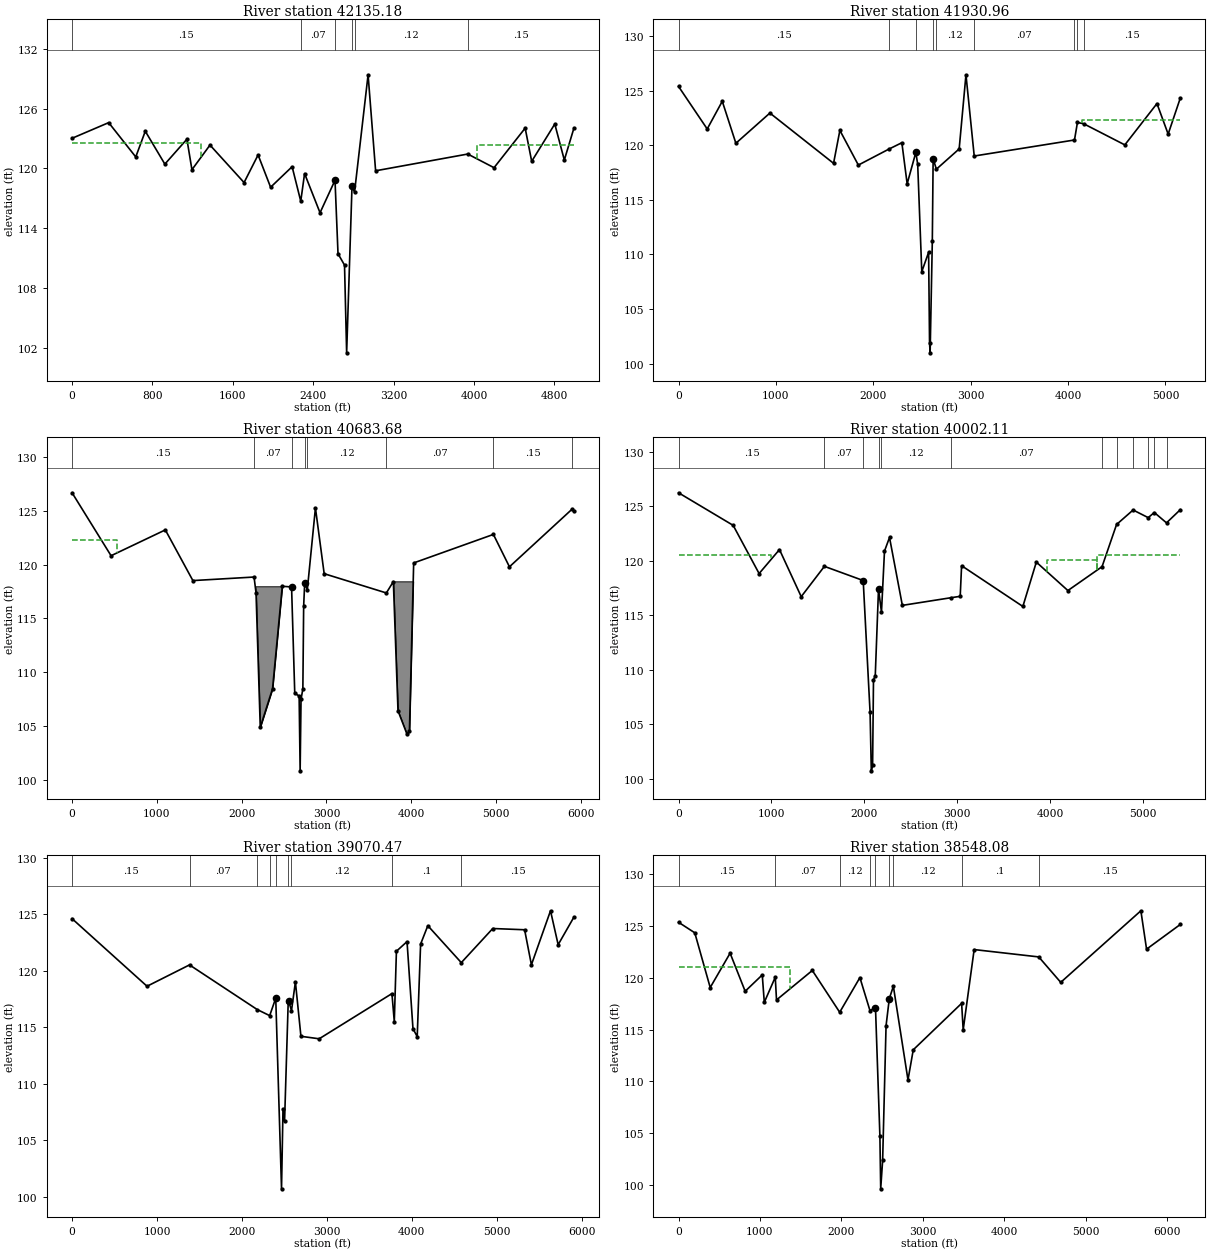
Type RM Length L Ch R = 1 ,42135.18,97.68,204.22,463.83
XS GIS Cut Line= 6
3005543.6616656913858656.43869683005076.2360913613857139.2435684
3004794.1516817813856669.10310453004644.7999463513856258.6498572
3004671.6168218613854967.53564153003752.4103269413854311.3535549
#Sta/Elev= 30
       0  123.03  364.44   124.6  634.03  121.16  728.88  123.74  923.58  120.44
 1143.25  122.94 1193.17  119.88  1372.9  122.35 1712.18  118.59 1851.74  121.36
 1976.35  118.12 2190.44  120.18 2276.47  116.72 2314.53  119.49 2468.39  115.56
 2617.47  118.82 2647.36  111.45 2712.14  110.31 2733.24  101.51 2786.88  118.29
  2811.8  117.62 2946.69   129.4 3021.61  119.77 3938.83  121.45 4200.53  120.08
 4510.35  124.05 4575.31  120.72 4805.18  124.46 4900.13  120.85 4995.07  124.03
#Mann= 6 ,-1 , 0
       0     .15       0 2276.47     .07       0 2617.47     .04       0
 2786.88     .07       0  2811.8     .12       0 3938.83     .15       0
#XS Ineff= 2 ,-1
       0 1288.03  122.53 4035.62 4995.07  122.38
Permanent Ineff=
       F       F
Bank Sta=2617.47,2786.88
XS Rating Curve= 0 ,0
Exp/Cntr=0.3,0.1

Type RM Length L Ch R = 1 ,41930.96,866.85,1247.28,974.69
XS GIS Cut Line= 6
3005685.6492426113858462.81900533004738.7699027813856243.5898479
3004925.8200536113856076.9701024 3004963.715975213855100.8690363
3004762.0631632813854816.17997313003771.3410633713854223.0089153
#Sta/Elev= 30
       0  125.41  294.44  121.51  449.14  124.05  588.88   120.2  938.21  122.97
 1591.96  118.36 1656.83  121.38 1846.47   118.2 2159.29  119.66  2293.3  120.25
 2347.75  116.48 2436.74  119.36  2455.9  118.27 2497.89  108.42 2567.98   110.2
 2577.63   101.9  2583.6  100.98 2606.04  111.21 2614.56  118.79 2647.62  117.82
 2881.82  119.68  2951.6  126.48 3036.47  119.03 4066.03   120.5  4096.4  122.11
 4162.24  121.98 4583.06  120.05 4912.97  123.84 5027.94  121.04 5152.91  124.35
#Mann= 9 ,-1 , 0
       0     .15       0 2159.29     .07       0 2436.74     .04       0
 2614.56     .07       0 2647.62     .12       0 3036.47     .07       0
 4066.03     .12       0  4096.4     .07       0 4162.24     .15       0
#XS Ineff= 2 ,-1
       0   888.3   122.3 4143.17 5152.91   122.3
Permanent Ineff=
       F       F
Bank Sta=2436.74,2614.56
XS Rating Curve= 0 ,0
Exp/Cntr=0.3,0.1

Type RM Length L Ch R = 1 ,40683.68,854.82,681.57,318.04
XS GIS Cut Line= 6
3005883.5714189413858355.25261943005330.6496245313856569.2105878
3005462.1099915213855912.80999773005679.2900033613855700.2598979
3005578.5671076913854707.91772243003872.3064126113853528.8725083
#Sta/Elev= 30
       0  126.68  459.92  120.83  1099.8  123.23 1424.75  118.52 2146.32  118.85
 2169.42  117.38 2219.37  104.89 2364.25  108.47 2479.15  117.99 2588.54  117.93
  2626.2  108.04 2677.73   107.8  2689.6  100.84  2700.2  107.48 2721.73  108.46
 2731.12  116.14 2743.13  118.26 2774.29  117.67 2870.04  125.27 2973.14  119.16
 3706.45  117.37 3788.94  118.43 3843.66  106.42 3948.61  104.27  3978.6   104.5
 4028.58  120.16 4968.65  122.81 5158.02   119.8 5901.15  125.19 5917.64  124.96
#Mann= 8 ,-1 , 0
       0     .15       0 2146.32     .07       0 2588.54     .04       0
 2743.13     .07       0 2774.29     .12       0 3706.45     .07       0
 4968.65     .15       0 5901.15      .1       0
#XS Ineff= 3 ,-1
       0  524.91   122.3 4433.38 4963.11  120.33 4963.11 5917.64     121
Permanent Ineff=
       F       F       F
#Block Obstruct= 2 ,-1
 2159.42 2479.15  117.99 3778.99 4033.57  118.45
Bank Sta=2588.54,2743.13
XS Rating Curve= 0 ,0
Exp/Cntr=0.3,0.1

Type RM Length L Ch R = 1 ,40002.11,916.11,931.63,801.16
XS GIS Cut Line= 6
3006655.6095730213857583.15212943006642.2657676913856462.2744499
3006115.6398524513855530.58996163005894.36831336 13855042.958719
3005871.3463777813854695.53585743004164.2326660313853119.1777897
#Sta/Elev= 30
       0  126.22  587.88  123.23  866.87  118.81 1086.08  121.01    1320  116.69
 1569.49  119.47 1986.89  118.17 2060.89  106.07  2074.2  100.71 2087.96   101.2
 2097.62  109.07 2116.52  109.41 2151.53  117.38 2183.53  115.27 2215.99  120.87
    2270  122.12 2408.09  115.89  2929.5  116.59 3030.58  116.72  3045.5  119.53
 3704.73  115.79 3849.58  119.86 4189.25  117.25 4556.67  119.44 4712.89  123.31
 4890.83  124.64 5053.31  123.94 5119.12  124.41 5250.29  123.46 5398.94  124.67
#Mann= 12 ,-1 , 0
       0     .15       0 1569.49     .07       0 1986.89     .04       0
 2151.53     .12       0 2183.53     .12       0  2929.5     .07       0
 4556.67      .1       0 4712.89     .15       0 4890.83      .1       0
 5053.31     .15       0 5119.12      .1       0 5250.29     .15       0
#XS Ineff= 3 ,-1
       0  991.43   120.5 3964.47 4503.94  120.02 4503.94 5398.94   120.5
Permanent Ineff=
       F       F       F
Bank Sta=1986.89,2151.53
XS Rating Curve= 0 ,0
Exp/Cntr=0.3,0.1

Type RM Length L Ch R = 1 ,39070.47,529.43,522.4,537.18
XS GIS Cut Line= 6
3007234.3872868613857441.55661213007255.2799616213856759.1698535
3006812.8500721913855145.59991793006743.5700270213854922.8398648
3005727.5438438713853402.66573983004899.9962863613852164.4923631
#Sta/Elev= 30
       0  124.59  882.48  118.61 1382.39   120.5 2179.17  116.55 2326.26  116.01
 2397.61  117.56 2465.62  100.68 2482.94  107.72 2501.38  106.65 2544.45  117.26
 2549.41   117.3 2582.99  116.46 2629.09  118.99 2694.03  114.18 2908.85  113.96
 3765.34  117.96  3793.1  115.48 3818.08  121.71 3942.98  122.56 4012.92  114.86
 4062.88  114.15 4102.84  122.34 4187.77  123.97 4581.73   120.7 4952.32  123.72
 5327.14  123.61  5407.1  120.51 5631.99  125.29 5721.95  122.29 5906.86  124.72
#Mann= 9 ,-1 , 0
       0     .15       0 1382.39     .07       0 2179.17     .12       0
 2326.26     .07       0 2397.61     .04       0 2544.45     .07       0
 2582.99     .12       0 3765.34      .1       0 4581.73     .15       0
#XS Ineff= 2 ,-1
       0 1382.39     120 3932.99 5906.86     120
Permanent Ineff=
       F       F
Bank Sta=2397.61,2549.41
XS Rating Curve= 0 ,0
Exp/Cntr=0.3,0.1

Type RM Length L Ch R = 1 ,38548.08,203,200.48,212.74
XS GIS Cut Line= 6
 3007774.2418502  13857266.548763007745.8692035213856663.6775904
3007352.2699251213855113.01008813007289.8999711113854932.4799374
3007237.3899055313854781.49008183005526.07311819 13851603.182134
#Sta/Elev= 30
       0  125.37  199.52  124.35  389.06  119.06  633.54  122.38  818.52   118.7
  1028.5  120.28 1053.49  117.63 1188.26  120.06 1203.48  117.86 1643.44  120.71
 1979.78  116.67 2227.88  120.02 2351.61  116.83 2419.37  117.13 2473.59  104.69
 2483.36    99.6 2507.15  102.34 2549.26  115.37 2589.16  117.99 2639.02  119.18
 2818.53  110.13 2883.35  113.04 3477.38  117.53 3496.67  114.97  3631.3  122.73
 4424.77  122.02 4694.94  119.56  5679.3  126.48 5749.26  122.77 6163.99  125.16
#Mann= 9 ,-1 , 0
       0     .15       0 1188.26     .07       0 1979.78     .12       0
 2351.61     .07       0 2419.37     .04       0 2589.16     .07       0
 2639.02     .12       0 3477.38      .1       0 4424.77     .15       0
#XS Ineff= 4 ,-1
       0 1373.46     121 1373.46 1928.98  115.68 2639.02 4470.08  113.66
 4470.08 6163.99     121
Permanent Ineff=
       F       F       F       F
Bank Sta=2419.37,2589.16
XS Rating Curve= 0 ,0
Exp/Cntr=0.5,0.3

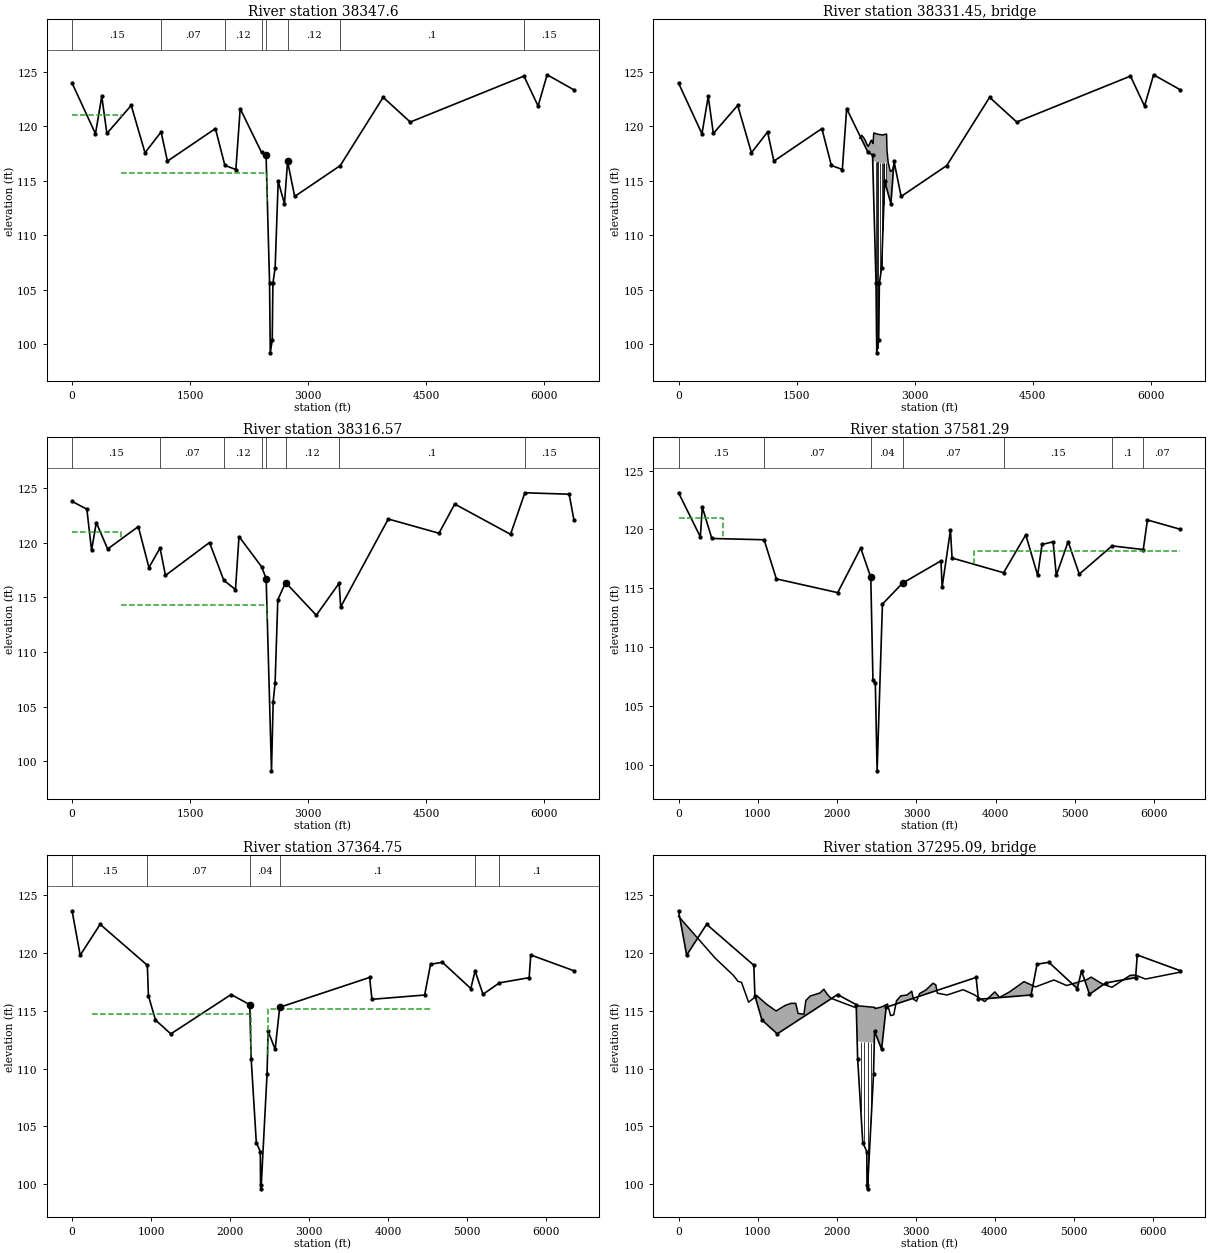
Type RM Length L Ch R = 1 ,38347.6 ,31.07,31.02,31.62
BEGIN DESCRIPTION:
Upstream Section - PRIVATE ROAD
END DESCRIPTION:
XS GIS Cut Line= 6
3008055.5792140213857209.68830943008053.0122900313856568.1964822
3007487.3976076113854876.1814935 3007444.915737213854775.4106977
3007404.9161452813854680.52768543005883.4100019513851268.0053109
#Sta/Elev= 30
       0  123.96  297.59   119.3  377.34  122.74  442.13  119.33  751.44  121.91
  926.34  117.56 1131.05  119.47 1211.19  116.79 1820.87  119.78 1941.13   116.4
 2080.73  116.02  2135.7  121.61 2406.77  117.59 2464.37  117.36 2508.66  105.64
 2517.84   99.19 2542.76  100.35 2550.99  105.56 2579.54     107 2618.27  114.96
 2697.82  112.87 2737.78  116.76  2827.7  113.55 3406.58  116.38 3951.61  122.65
 4296.27  120.38 5740.78   124.6 5919.68  121.85 6034.57  124.72 6374.24  123.34
#Mann= 8 ,-1 , 0
       0     .15       0 1131.05     .07       0 1941.13     .12       0
 2406.77     .07       0 2464.37     .04       0 2737.78     .12       0
 3406.58      .1       0 5740.78     .15       0
#XS Ineff= 3 ,-1
       0  626.54     121  626.54 2480.23  115.68 2642.87 6374.24  113.66
Permanent Ineff=
       F       F       F
Bank Sta=2464.37,2737.78
XS Rating Curve= 0 ,0
Exp/Cntr=0.5,0.3

Type RM Length L Ch R = 3 ,38331.45,,,
BEGIN DESCRIPTION:
PRIVATE ROAD
END DESCRIPTION:
Node Name=PRIVATE ROAD
Bridge Culvert--1,0,-1,-1, 0
Deck Dist Width WeirC Skew NumUp NumDn MinLoCord MaxHiCord MaxSubmerge Is_Ogee
9.5,14,2.6,0, 43, 43, , , 0.98, 0, 0,0,,
 2300.62 2310.61  2325.6 2355.59 2365.58 2380.57 2395.57 2410.56 2435.49 2440.46
  2450.4 2460.35 2465.32 2470.29 2480.23  2485.2 2490.17 2500.11 2510.06 2515.03
 2529.94 2544.72 2549.62 2559.43 2564.33 2569.23 2579.04 2583.94 2593.75 2598.65
 2608.46 2613.36 2618.27 2632.98 2642.87 2647.92 2662.85 2687.83 2692.83 2702.82
  2717.8  2722.8 2732.79
   118.9  118.95  119.17  118.91  118.79  118.56  118.28  118.16  118.51  118.62
  118.71  118.53  118.45  118.41  119.38  119.37  119.36  119.33  119.31   119.3
  119.27  119.24  119.24  119.23  119.23  119.22  119.21   119.2  119.19   119.2
  119.22  119.23  119.24  119.26  119.28   117.8  116.69  115.92  115.86  115.87
  116.01  116.07  116.41
       0       0       0       0       0       0       0       0       0       0
       0       0       0       0  116.78  116.77  116.76  116.73  116.71   116.7
  116.67  116.64  116.64  116.63  116.63  116.62  116.61   116.6  116.59   116.6
  116.62  116.63  116.64  116.66  116.68       0       0       0       0       0
       0       0       0
 2300.62 2310.61  2325.6 2355.59 2365.58 2380.57 2395.57 2410.56 2435.49 2440.46
  2450.4 2460.35 2465.32 2470.29 2480.23  2485.2 2490.17 2500.11 2510.06 2515.03
 2529.94 2544.72 2549.62 2559.43 2564.33 2569.23 2579.04 2583.94 2593.75 2598.65
 2608.46 2613.36 2618.27 2632.98 2642.87 2647.92 2662.85 2687.83 2692.83 2702.82
  2717.8  2722.8 2732.79
   118.9  118.95  119.17  118.91  118.79  118.56  118.28  118.16  118.51  118.62
  118.71  118.53  118.45  118.41  119.38  119.37  119.36  119.33  119.31   119.3
  119.27  119.24  119.24  119.23  119.23  119.22  119.21   119.2  119.19   119.2
  119.22  119.23  119.24  119.26  119.28   117.8  116.69  115.92  115.86  115.87
  116.01  116.07  116.41
       0       0       0       0       0       0       0       0       0       0
       0       0       0       0  116.71   116.7  116.69  116.66  116.64  116.63
   116.6  116.57  116.57  116.56  116.56  116.55  116.54  116.53  116.52  116.53
  116.55  116.56  116.57  116.59  116.61       0       0       0       0       0
       0       0       0
Pier Skew, UpSta & Num, DnSta & Num=  ,2510.23, 2 ,2510.23, 2 , 0 , 0 , 0 ,,
       1       1
      95  117.25
       1       1
      95  117.25
Pier Skew, UpSta & Num, DnSta & Num=  ,2527.73, 2 ,2527.73, 2 , 0 , 0 , 0 ,,
       1       1
      95  117.25
       1       1
      95  117.25
Pier Skew, UpSta & Num, DnSta & Num=  ,2561.73, 2 ,2561.73, 2 , 0 , 0 , 0 ,,
       1       1
      95  117.25
       1       1
      95  117.25
Pier Skew, UpSta & Num, DnSta & Num=  ,2579.13, 2 ,2579.13, 2 , 0 , 0 , 0 ,,
       1       1
      95  117.25
       1       1
      95  117.25
Pier Skew, UpSta & Num, DnSta & Num=  ,2596.23, 2 ,2596.23, 2 , 0 , 0 , 0 ,,
       1       1
      95  117.25
       1       1
      95  117.25
Pier Skew, UpSta & Num, DnSta & Num=  ,2607.53, 2 ,2607.53, 2 , 0 , 0 , 0 ,,
       1       1
      95  117.25
       1       1
      95  117.25
Pier Skew, UpSta & Num, DnSta & Num=  ,2613.63, 2 ,2613.63, 2 , 0 , 0 , 0 ,,
       1       1
      95  117.25
       1       1
      95  117.25
Pier Skew, UpSta & Num, DnSta & Num=  ,2630.33, 2 ,2630.33, 2 , 0 , 0 , 0 ,,
       1       1
      95  117.25
       1       1
      95  117.25
BR Coef=-1 , 1 , 1 ,0.9, 0 ,,,0.8,-1,1.2,0,
WSPro=,,,, 1 ,,,, 0 ,,,, 0 ,,,,-1 ,-1 ,-1 , 0 , 0 , 0 , 0 , 0
BC Design=,, 0 ,, 0 ,,,,,,
BC Use User HTab Curves=0
BC User HTab FreeFlow(D)= 0

Type RM Length L Ch R = 1 ,38316.57,678.85,735.29,852.49
BEGIN DESCRIPTION:
Downstream Section - PRIVATE ROAD
END DESCRIPTION:
Node Name=P
XS GIS Cut Line= 6
 3008084.150679213857197.9120863 3008081.5837552 13856556.420259
3007515.9690727713854864.40527043007473.4872023613854763.6344745
3007433.4876104413854668.75146223005911.9814671113851256.2290878
#Sta/Elev= 30
       0  123.76  187.94  123.05  247.75  119.28  307.56  121.82   452.1  119.41
  841.39  121.46  976.32  117.71 1117.82   119.5 1186.21  116.99 1745.91     120
 1927.84  116.54 2075.74   115.7 2120.71  120.55 2406.88  117.79 2465.32  116.71
 2533.33   99.12 2554.52  105.43 2579.04  107.15 2613.36  114.77 2712.81  116.34
 3102.43  113.35 3392.42  116.28 3412.13  114.11 4016.54  122.15 4660.91  120.85
 4860.72  123.52 5570.02  120.75 5751.84  124.55 6314.29  124.42 6374.23   122.1
#Mann= 8 ,-1 , 0
       0     .15       0 1117.82     .07       0 1927.84     .12       0
 2406.88     .07       0 2465.32     .04       0 2712.81     .12       0
 3392.42      .1       0 5751.84     .15       0
#XS Ineff= 3 ,-1
       0  621.56     121  621.56 2480.23   114.3 2642.87 6374.23   113.2
Permanent Ineff=
       F       F       F
Bank Sta=2465.32,2712.81
XS Rating Curve= 0 ,0
Exp/Cntr=0.5,0.3

Type RM Length L Ch R = 1 ,37581.29,258.84,216.53,398.28
XS GIS Cut Line= 6
3008109.2451171913857188.1361872 3008110.955743713857108.1366753
3008159.5301216113854836.61005043008211.2800181113854597.7699769
3008106.0800972713853766.43994663008358.7839881913850883.5257649
#Sta/Elev= 30
       0  123.11  274.76  119.37  299.73  121.89  419.58  119.23 1078.96  119.12
 1233.52   115.8 2007.51  114.63 2297.13  118.42 2424.56  115.93 2451.81  107.23
 2481.73     107 2504.48    99.5 2571.51  113.66 2825.89  115.44 3309.72  117.33
 3324.68  115.11 3429.43  119.95 3449.41  117.57 4099.45  116.32 4379.15  119.54
  4529.1   116.1 4584.09  118.72 4724.04  118.95 4764.03  116.11 4913.99  118.96
 5053.95   116.2 5467.38   118.6 5860.99  118.29 5913.59   120.8 6328.39  120.01
#Mann= 7 ,-1 , 0
       0     .15       0 1078.96     .07       0 2424.56     .04       0
 2825.89     .07       0 4099.45     .15       0 5467.38      .1       0
 5860.99     .07       0
#XS Ineff= 4 ,-1
       0  564.39     121  564.39 2006.48   114.6 2967.24 3729.33  114.71
 3729.33 6328.39   118.2
Permanent Ineff=
       F       F       F       F
Bank Sta=2424.56,2825.89
XS Rating Curve= 0 ,0
Exp/Cntr=0.5,0.3

Type RM Length L Ch R = 1 ,37364.75,189.87,145.35,236.05
BEGIN DESCRIPTION:
Upstream Section - FRY ROAD
END DESCRIPTION:
XS GIS Cut Line= 6
3008299.5537916913857066.41694243008332.9933573613855440.5018872
3008377.5142656913854836.83675593008428.7261055313854613.4963233
3008842.0336778613853456.25355913008947.5049236113850798.7719974
#Sta/Elev= 30
       0  123.64  102.83   119.8  355.34  122.47  953.02  118.93  966.45   116.3
 1055.95   114.2 1249.87     113 2013.03   116.4 2249.18  115.53 2267.37  110.85
 2332.32  103.61 2383.12  102.83 2386.12   99.93 2392.43   99.61 2468.54  109.57
 2481.53  113.23 2570.74  111.67 2628.52   115.3 3766.59  117.88 3796.24  115.99
 4463.29  116.36 4538.19  119.02 4687.99  119.19 5047.52  116.92 5101.69  118.44
 5202.32  116.42 5409.07  117.41 5786.55  117.86 5806.52  119.82 6352.22  118.46
#Mann= 6 ,-1 , 0
       0     .15       0  953.02     .07       0 2249.18     .04       0
 2628.52      .1       0 5101.69     .15       0 5409.07      .1       0
#XS Ineff= 4 ,-1
       0  255.98     121  255.98 2266.73  114.69 2474.39 4548.18  115.18
 4548.18 6352.22     118
Permanent Ineff=
       F       F       F       F
Bank Sta=2249.18,2628.52
XS Rating Curve= 0 ,0
Exp/Cntr=0.5,0.3

Type RM Length L Ch R = 3 ,37295.09,,,
BEGIN DESCRIPTION:
FRY ROAD
END DESCRIPTION:
Node Name=FRY ROAD
Bridge Culvert--1,0,-1,-1, 0
Deck Dist Width WeirC Skew NumUp NumDn MinLoCord MaxHiCord MaxSubmerge Is_Ogee
19,97,2.6,0, 60, 60, , , 0.98, 0, 0,0,,
       0  464.63  693.15  752.77  797.48   886.9  991.31 1115.62 1234.96 1349.32
 1423.91 1483.54 1513.17 1587.24 1611.93 1666.43 1790.45 1840.06 1879.74 1929.25
 2242.53 2262.46 2266.73 2477.52 2486.23 2486.48 2570.74 2645.09 2684.74 2724.41
 2759.11 2813.65 2892.97 2952.46 2972.41 3012.31  3052.2 3131.99 3221.75 3256.66
  3276.6 3399.91 3603.14 3741.88  3875.3 4003.89 4063.81 4188.65 4373.41 4518.22
 4752.91  4912.7 5172.36 5222.29 5372.09 5486.94 5716.64 5781.56 5910.87 6352.22
  123.16  119.54  118.07  117.54  117.45  115.74   116.3  115.56  114.98  115.46
  115.64  115.64  114.77  114.69  115.89  116.27  116.54  116.86  116.45  116.08
  115.27   115.4  115.43   115.3  115.26  115.18  115.33  115.58  114.58  114.65
  115.86  116.29  116.36  116.69  116.01  115.82  116.49   116.8  117.38  117.24
  116.52  116.36  116.82  116.39  115.79  116.63  116.16  116.62  117.52  117.06
  117.66  117.18   117.7  117.91  117.29  117.03  118.06  118.09  117.74  118.34
       0       0       0       0       0       0       0       0       0       0
       0       0       0       0       0       0       0       0       0       0
       0       0  112.35  112.22       0       0       0       0       0       0
       0       0       0       0       0       0       0       0       0       0
       0       0       0       0       0       0       0       0       0       0
       0       0       0       0       0       0       0       0       0       0
       0  464.63  693.15  752.77  797.48   886.9  991.31 1115.62 1234.96 1349.32
 1423.91 1483.54 1513.17 1587.24 1611.93 1666.43 1790.45 1840.06 1879.74 1929.25
 2242.53 2262.46 2266.73 2477.52 2486.23 2486.48 2570.74 2645.09 2684.74 2724.41
 2759.11 2813.65 2892.97 2952.46 2972.41 3012.31  3052.2 3131.99 3221.75 3256.66
  3276.6 3399.91 3603.14 3741.88  3875.3 4003.89 4063.81 4188.65 4373.41 4518.22
 4752.91  4912.7 5172.36 5222.29 5372.09 5486.94 5716.64 5781.56 5910.87 6352.22
  123.16  119.54  118.07  117.54  117.45  115.74   116.3  115.56  114.98  115.46
  115.64  115.64  114.77  114.69  115.89  116.27  116.54  116.86  116.45  116.08
  115.27   115.4  115.43   115.3  115.26  115.18  115.33  115.58  114.58  114.65
  115.86  116.29  116.36  116.69  116.01  115.82  116.49   116.8  117.38  117.24
  116.52  116.36  116.82  116.39  115.79  116.63  116.16  116.62  117.52  117.06
  117.66  117.18   117.7  117.91  117.29  117.03  118.06  118.09  117.74  118.34
       0       0       0       0       0       0       0       0       0       0
       0       0       0       0       0       0       0       0       0       0
       0       0  112.32  112.19       0       0       0       0       0       0
       0       0       0       0       0       0       0       0       0       0
       0       0       0       0       0       0       0       0       0       0
       0       0       0       0       0       0       0       0       0       0
Pier Skew, UpSta & Num, DnSta & Num=  ,2308.13, 2 ,2308.13, 2 , 0 , 0 , 0 ,,
     1.4     1.4
      95     114
     1.4     1.4
      95     114
Pier Skew, UpSta & Num, DnSta & Num=  ,2351.53, 2 ,2351.53, 2 , 0 , 0 , 0 ,,
     1.4     1.4
      95     114
     1.4     1.4
      95     114
Pier Skew, UpSta & Num, DnSta & Num=  ,2393.13, 2 ,2393.13, 2 , 0 , 0 , 0 ,,
     1.4     1.4
      95     114
     1.4     1.4
      95     114
Pier Skew, UpSta & Num, DnSta & Num=  ,2435.83, 2 ,2435.83, 2 , 0 , 0 , 0 ,,
     1.4     1.4
      95     114
     1.4     1.4
      95     114
BR Coef=-1 , 1 , 1 ,0.9, 0 ,,,0.8,-1,1.2,0,
WSPro=,,,, 1 ,,,, 0 ,,,, 0 ,,,,-1 ,-1 ,-1 , 0 , 0 , 0 , 0 , 0
BC Design=,, 0 ,, 0 ,,,,,,
BC Use User HTab Curves=0
BC User HTab FreeFlow(D)= 0

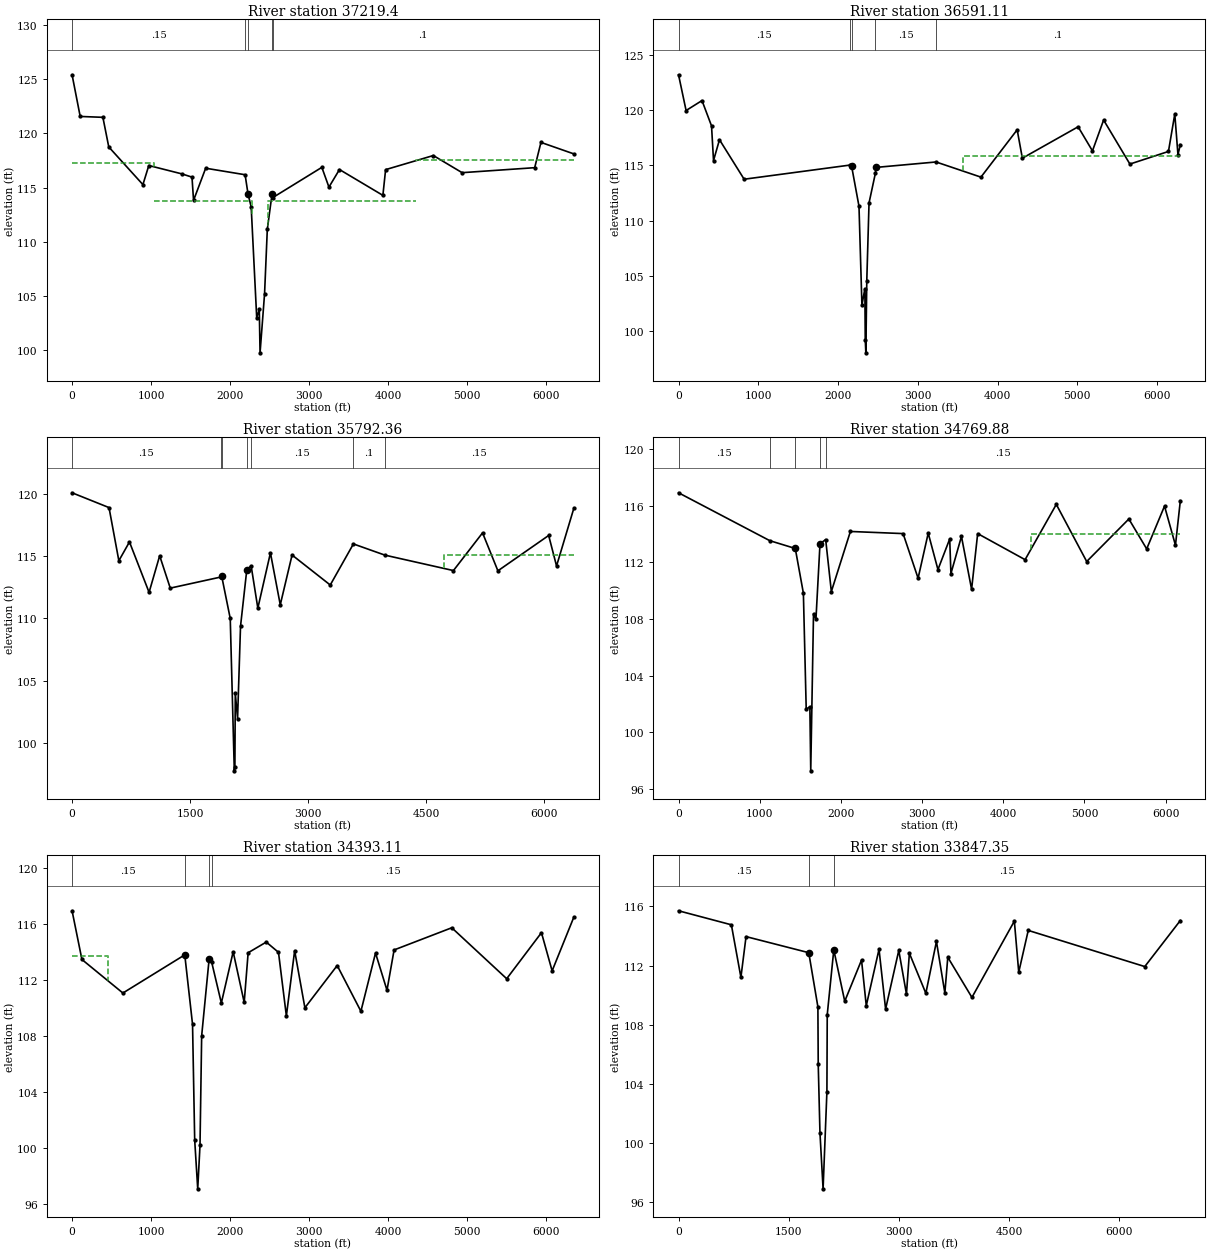
Type RM Length L Ch R = 1 ,37219.4 ,645.33,628.29,448.9
BEGIN DESCRIPTION:
Downstream Section - FRY ROAD
END DESCRIPTION:
Node Name=O
XS GIS Cut Line= 6
3008437.0111939513857070.4599134 3008470.450759613855444.5448581
3008514.9716679513854840.87972693008566.1835077713854617.5392943
3008979.49108011  13853460.296533009084.9623258613850802.8149683
#Sta/Elev= 30
       0  125.39  102.83  121.55  390.11  121.47  464.63  118.74  896.84  115.27
  971.42  117.03  1389.1  116.26 1518.11  115.96 1537.86  113.82 1691.23  116.78
 2190.49  116.18 2227.58   114.4 2267.49  113.22  2337.4     103 2370.16  103.78
  2379.7   99.77 2436.81  105.21 2471.62  111.15 2531.09  114.38  2539.7  114.07
 3161.91  116.86 3251.67  115.04 3385.11  116.66  3934.6  114.28  3969.2  116.65
 4573.14  117.95 4937.67  116.37 5856.32  116.83 5935.66  119.16 6352.22   118.1
#Mann= 5 ,-1 , 0
       0     .15       0 2190.49     .07       0 2227.58     .04       0
 2531.09     .07       0  2539.7      .1       0
#XS Ineff= 4 ,-1
       0 1036.06  117.28 1036.06 2272.79   113.8 2477.52 4353.43   113.8
 4353.43 6352.22   117.5
Permanent Ineff=
       F       F       F       F
Bank Sta=2227.58,2531.09
XS Rating Curve= 0 ,0
Exp/Cntr=0.5,0.3

Type RM Length L Ch R = 1 ,36591.11,837.64,798.75,731.13
XS GIS Cut Line= 6
3008753.0007194413857015.33961683008915.02172086 13856367.255283
3009131.6098703613854865.83997883009175.45984827 13854580.810037
3009218.3101562713851064.69010083009221.9987971913850762.0036983
#Sta/Elev= 30
       0  123.18   94.72  119.95  294.13  120.85  413.78  118.56  438.71  115.43
  513.49  117.31  822.72  113.74 2150.84  115.02 2170.02  114.93 2262.83   111.3
 2299.71  102.35 2336.51  103.85  2341.4   99.24 2348.84   98.05 2360.67  104.57
 2388.84   111.6 2469.71  114.32 2478.36  114.81 3229.13   115.3 3792.03  113.93
 4246.56  118.21  4311.5  115.64 5010.76  118.48 5190.57   116.3 5330.42  119.09
 5660.08  115.11 6143.56  116.25 6222.96  119.63 6262.66  115.96 6292.44  116.86
#Mann= 5 ,-1 , 0
       0     .15       0 2150.84     .07       0 2170.02     .04       0
 2469.71     .15       0 3229.13      .1       0
#XS Ineff= 2 ,-1
       0  548.38  115.84 3562.26 6292.44  115.84
Permanent Ineff=
       F       F
#Block Obstruct= 2 , 0
       0                 6222.96       0  119.63
Bank Sta=2170.02,2478.36
XS Rating Curve= 0 ,0
Exp/Cntr=0.3,0.1

Type RM Length L Ch R = 1 ,35792.36,989.46,1022.48,1087.37
XS GIS Cut Line= 4
3010040.0345626913857035.16766113009801.52552527 13856367.341897
 3009885.719910713855004.2701481 3009513.760024713850720.9299615
#Sta/Elev= 30
       0   120.1  469.43  118.91  594.28  114.64  729.08  116.15  978.29   112.1
 1112.86  115.04 1247.43  112.44 1889.13  113.33 1900.37  113.41 2009.34     110
 2060.97   97.76 2068.31   98.07 2073.45     104 2102.37  101.96 2139.81  109.37
  2219.8  113.93 2274.79  114.23 2359.78  110.83 2519.76  115.27 2644.74   111.1
 2794.72   115.1 3279.66  112.69  3573.8  115.99 3974.17  115.09 4844.47  113.85
 5214.44  116.88 5409.42  113.83 6054.35  116.67 6154.34  114.22 6374.32  118.86
#Mann= 7 ,-1 , 0
       0     .15       0 1889.13     .07       0 1900.37     .04       0
  2219.8     .07       0 2274.79     .15       0  3573.8      .1       0
 3974.17     .15       0
#XS Ineff= 2 ,-1
       0   659.2  115.07 4724.49 6374.32  115.07
Permanent Ineff=
       F       F
Bank Sta=1900.37,2219.8
XS Rating Curve= 0 ,0
Exp/Cntr=0.3,0.1

Type RM Length L Ch R = 1 ,34769.88,534.88,376.76,401.18
XS GIS Cut Line= 3
3010736.3051517813856573.74273093011030.4485923613853191.0926721
 3009870.216004713850658.1909138
#Sta/Elev= 30
       0  116.91 1124.41  113.53 1438.06  112.98 1537.92  109.83 1572.88  101.64
 1617.82  101.81 1628.59   97.29 1662.75  108.38 1692.71  107.98 1742.65  113.31
 1812.55  113.61 1882.46  109.94 2117.14  114.18 2766.26  114.03 2951.01  110.88
 3075.84  114.06 3195.68  111.49 3340.48  113.65 3355.46  111.21 3485.28  113.83
  3610.1   110.1 3684.99  114.03 4269.15  112.19  4653.6  116.09 5028.07  112.06
 5547.33  115.06 5767.02  112.95  5986.7  115.97 6121.51  113.21 6181.43  116.35
#Mann= 5 ,-1 , 0
       0     .15       0 1124.41     .07       0 1438.06     .04       0
 1742.65     .07       0 1812.55     .15       0
#XS Ineff= 1 ,-1
 4339.05 6181.43     114
Permanent Ineff=
       F
Bank Sta=1438.06,1742.65
XS Rating Curve= 0 ,0
Exp/Cntr=0.3,0.1

Type RM Length L Ch R = 1 ,34393.11,582.96,545.76,689.56
BEGIN DESCRIPTION:
CONFLUENCE WITH U101-13-00
END DESCRIPTION:
XS GIS Cut Line= 5
3011185.8869297813856605.87652493011222.3501114413855160.5001506
3011253.9199301913854878.98988693011319.6901398613853194.8498824
3009916.3806105313850617.7346299
#Sta/Elev= 30
       0  116.92  124.64  113.45  643.15  111.06 1425.89  113.78 1524.27  108.83
 1551.46  100.59 1589.87   97.11 1618.68  100.21 1639.66  108.01  1734.1  113.48
 1767.17  113.24 1888.68  110.35 2038.27     114 2177.89  110.39 2227.76  113.93
 2457.13  114.69 2611.71  113.96 2711.44  109.43 2816.16  114.08  2945.8  110.01
 3354.69  113.02 3654.48  109.76 3839.44  113.91 3984.41  111.26 4074.39  114.13
 4804.24  115.71  5499.1  112.08 5939.01  115.36 6073.98  112.64 6348.92  116.47
#Mann= 4 ,-1 , 0
       0     .15       0 1425.89     .04       0  1734.1     .07       0
 1767.17     .15       0
#XS Ineff= 2 ,-1
       0  458.68   113.7 3839.44 6348.92   113.7
Permanent Ineff=
       F       F
Bank Sta=1425.89,1734.1
XS Rating Curve= 0 ,0
Exp/Cntr=0.3,0.1

Type RM Length L Ch R = 1 ,33847.35,33.15,33.71,33.31
XS GIS Cut Line= 6
3012663.2789881113856720.00588983012405.8579150313856468.3426793
 3011540.389829713854454.76632583011495.1815867713854211.3376788
3011488.2265481913852935.83596483010151.92443077 13850522.688232
#Sta/Elev= 30
       0  115.71  719.72  114.76  849.62   111.2  919.56  113.96  1773.9  112.87
 1898.25   109.2 1902.74  105.32 1926.41  100.66    1969   96.87 2021.06  103.45
 2025.49  108.67 2114.79  113.06 2263.91  109.58 2492.56  112.37 2557.16  109.28
 2730.88   113.1  2820.5  109.05 2999.87  113.02 3104.51  110.07 3144.37  112.83
 3368.58  110.12 3513.07  113.63 3627.67  110.14 3667.53  112.56 3996.38  109.84
 4574.19  115.01 4633.96  111.55 4763.47  114.38  6350.8  111.93 6834.99  115.05
#Mann= 3 ,-1 , 0
       0     .15       0  1773.9     .04       0 2114.79     .15       0
#XS Ineff= 2 ,-1
       0  919.56  113.96 4574.19 6834.99  113.96
Permanent Ineff=
       F       F
Bank Sta=1773.9,2114.79
XS Rating Curve= 0 ,0
Exp/Cntr=0.5,0.3