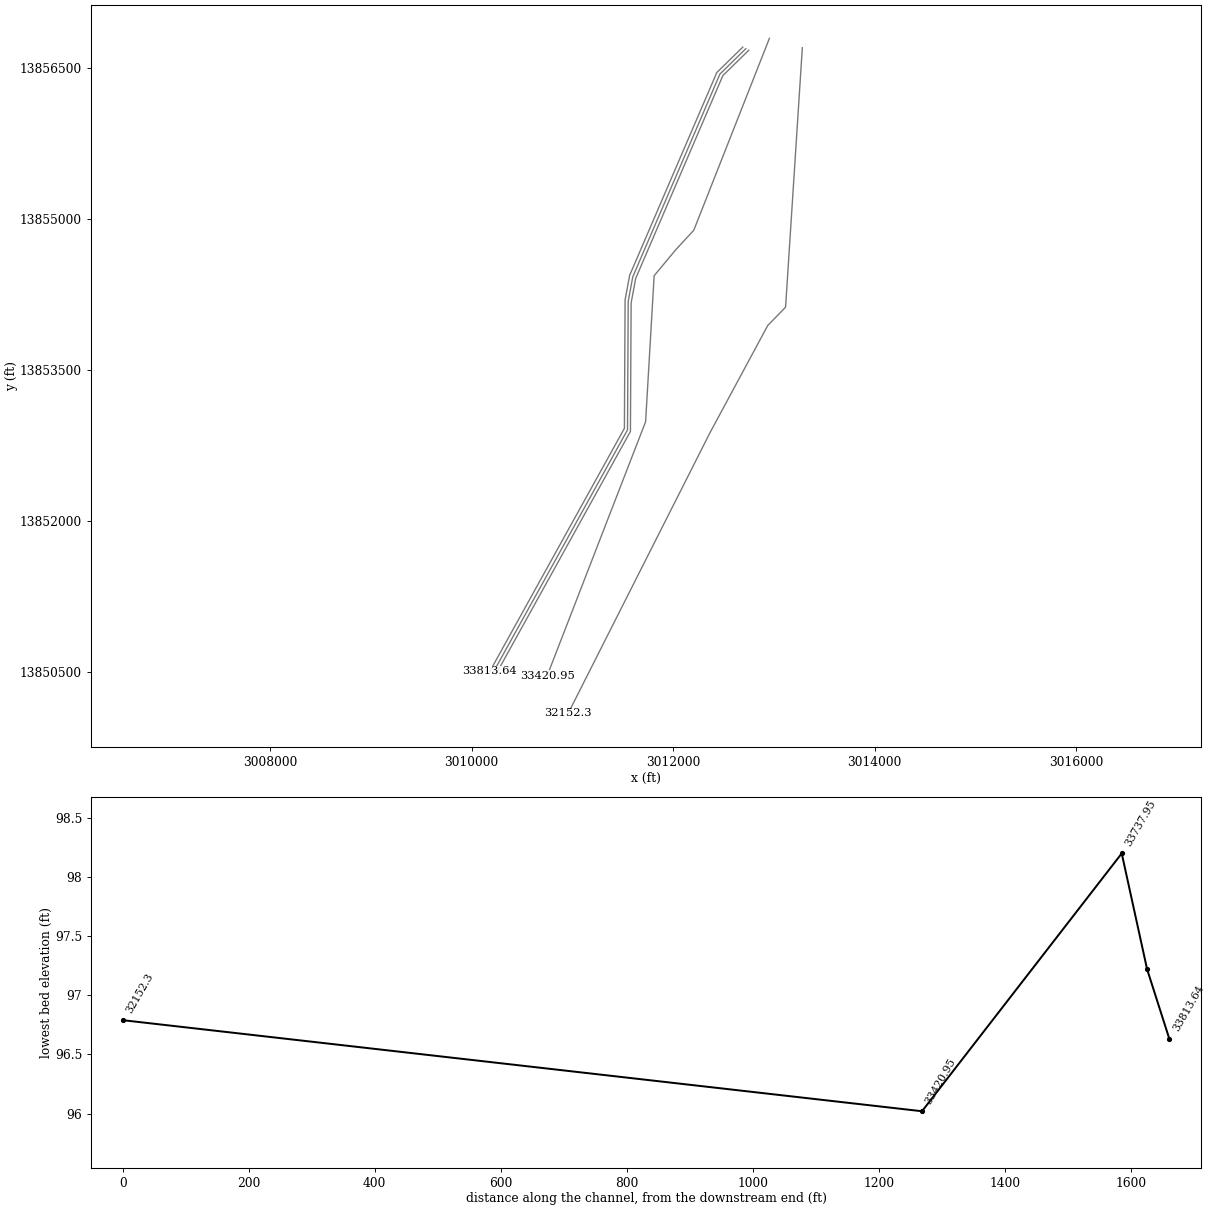
HEC-RAS study U101-00-00.prj: U101-00-00 2019 (Re-Study)

--- U101-00-00.g01 (geometry) --- (continued)

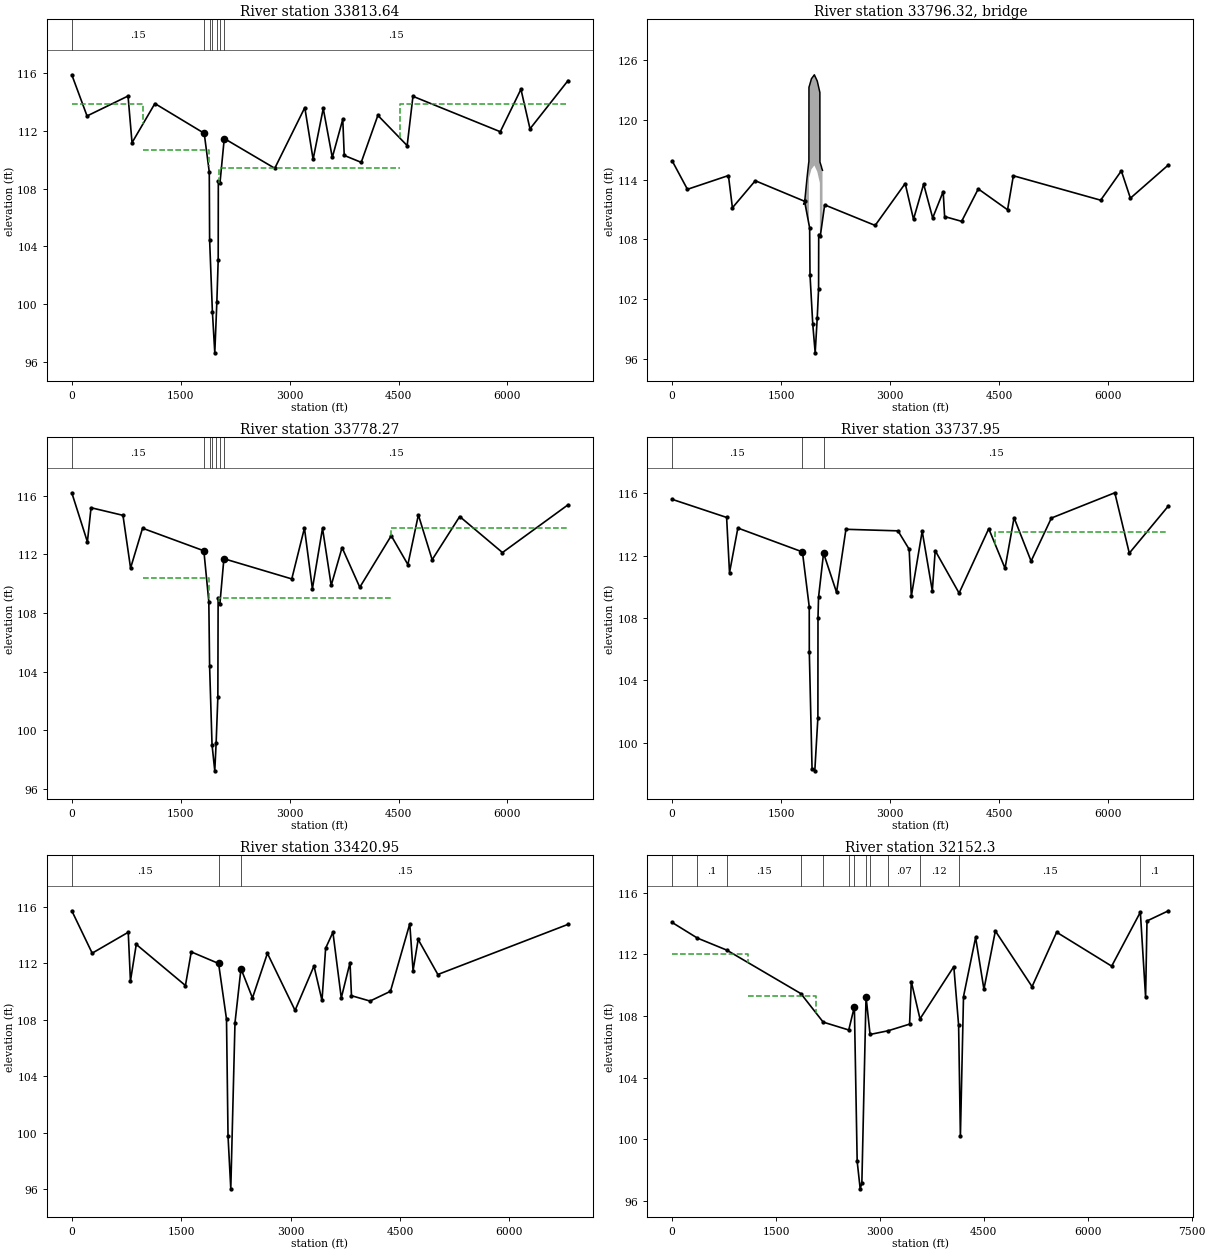
Type RM Length L Ch R = 1 ,33813.64,35.14,35.37,34.65
BEGIN DESCRIPTION:
Upstream Section - HEATHERGOLD
END DESCRIPTION:
XS GIS Cut Line= 6
3012692.0308991113856704.26084263012434.60982603 13856452.597632
3011569.1414126213854439.02127863011523.9334977713854195.5923035
3011516.9781311213852920.09058943010180.6760136913850506.9431848
#Sta/Elev= 30
       0  115.87     210  113.02  774.68   114.4  829.63  111.17 1144.39  113.88
 1823.86  111.82 1893.42  109.14 1898.15  104.46  1936.4   99.49 1969.46   96.63
 1997.66  100.12 2016.46  103.07 2018.17  108.49 2040.23  108.35 2099.88  111.46
 2795.59   109.4 3209.14   113.6 3323.74  110.02 3463.25  113.54 3587.81  110.15
 3732.31  112.79 3752.24  110.29 3986.41  109.81 4215.57  113.06 4619.02  110.97
 4698.71  114.38 5901.54  111.93 6186.07  114.87 6310.86  112.13 6834.99  115.47
#Mann= 7 ,-1 , 0
       0     .15       0 1823.86     .04       0 1898.15    .015       0
  1936.4     .04       0 1997.66    .015       0 2040.23     .04       0
 2099.88     .15       0
#XS Ineff= 4 ,-1
       0  979.51  113.85  979.51 1883.22  110.69 2034.22  4519.4  109.45
  4519.4 6834.99  113.85
Permanent Ineff=
       F       F       F       F
Bank Sta=1823.86,2099.88
XS Rating Curve= 0 ,0
Exp/Cntr=0.5,0.3

Type RM Length L Ch R = 3 ,33796.32,,,
BEGIN DESCRIPTION:
HEATHERGOLD PEDESTRIAN BRIDGE
END DESCRIPTION:
Node Name=HEATHERGOLD
Bridge Culvert--1,0,-1,-1, 0
Deck Dist Width WeirC Skew NumUp NumDn MinLoCord MaxHiCord MaxSubmerge Is_Ogee
10,16,2.6,0, 179, 179, , , 0.98, 0, 0,0,,
 1811.55 1816.19 1816.29 1816.37 1816.39 1816.49  1816.6 1816.71 1816.82 1816.93
 1817.05 1817.17 1817.29 1817.41 1817.54 1817.67  1817.8 1817.93 1818.07 1818.21
 1818.35 1818.49 1818.64 1818.79 1818.94 1819.09 1819.24 1821.17 1823.23 1823.27
 1823.37 1823.41 1823.51 1823.55 1823.65 1823.69  1823.8 1823.84 1823.95 1823.99
  1824.1 1824.14 1824.25 1824.29  1824.4 1824.44 1824.55 1824.59 1824.71 1824.75
 1824.87 1824.91 1825.03 1825.07 1825.19 1825.23 1825.35 1825.39 1825.51 1825.55
 1825.67 1825.71 1825.83 1825.87 1825.95 1825.99 1826.03 1826.16  1826.2 1826.33
 1826.37  1826.4 1826.44 1826.48 1830.76 1833.17 1835.58  1840.4 1845.22  1849.8
 1850.04 1854.86 1857.51 1859.67 1864.49 1869.31 1872.65 1874.12 1878.94 1879.74
    1882  1882.3 1882.49 1882.65 1882.74 1882.91 1883.22 1883.75  1885.2 1888.53
 1891.75 1893.31 1896.42 1898.09 1901.07 1902.87 1905.22 1907.65 1912.17 1912.43
 1916.79 1917.21 1918.33 1921.57 1921.99  1926.5 1926.77 1931.55 1932.61 1936.33
 1941.11 1944.52 1945.89 1949.65 1950.85  1955.1 1955.81 1958.24 1960.77 1961.18
 1964.51 1965.73 1967.45 1970.69 1972.69 1975.65 1980.61 1984.32 1985.57 1989.95
 1990.53  1993.6 1995.49 1996.96 1998.18 2000.45 2002.25 2005.41 2005.85 2010.37
 2010.79 2015.33 2016.36 2020.29 2021.32 2024.79 2025.25 2028.87 2030.21 2031.09
 2032.11 2032.78 2033.37 2033.66 2033.86 2034.05 2034.22 2034.47 2034.67 2035.18
 2037.15 2057.83 2058.12 2058.15 2058.18 2058.21 2060.35 2060.35 2070.26
  111.54  111.51  111.51  111.52  111.52  111.52  111.52  111.53  111.53  111.53
  111.54  111.54  111.55  111.55  111.56  111.56  111.57  111.57  111.58  111.58
  111.59   111.6   111.6  111.61  111.62  111.63  111.63  111.68  111.74  111.74
  111.75  111.75  111.75  111.76  111.76  111.76  111.77  111.77  111.78  111.78
  111.79  111.79   111.8   111.8   111.8   111.8  111.81  111.81  111.82  111.82
  111.83  111.83  111.84  111.84  111.85  111.85  111.86  111.85  111.86  111.86
  111.87  111.87  111.88  111.88  111.89  111.89  111.89   111.9   111.9  111.91
  111.91  111.91  111.91   111.9  112.23  112.42   112.6  112.97  113.33  113.68
   113.7  113.99  114.15  114.31  114.66     115  115.24  115.33   115.6  115.65
  115.78  115.78  115.79  115.78  115.78  115.79  123.24  123.25  123.28  123.36
  123.43  123.47  123.55  123.59  123.67  123.71  123.78  123.84  123.95  123.97
  124.08  124.09  124.11  124.15  124.15  124.19  124.19  124.24  124.25  124.28
  124.33  124.36  124.38  124.41  124.42  124.47  124.48   124.5  124.45  124.45
   124.4  124.38  124.35   124.3  124.27  124.23  124.14  124.08  124.07  123.99
  123.99  123.94  123.92  123.88  123.87   123.8  123.75  123.64  123.63  123.49
  123.48  123.33   123.3  123.18  123.14  123.04  123.02  122.91  122.87  122.83
   122.8   122.8  122.81  122.77  122.75  122.73  122.73  115.78  115.79  115.77
  115.71  115.23  115.18  115.17  115.17  115.16  115.13  115.13  114.93
                                                                                
                                                                                
                                                                                
                                                                                
                                                                                
                                                                                
                                                                                
                                                                                
                                                                                
                                                  114.16  114.17   114.2  114.28
  114.35  114.39  114.47  114.51  114.59  114.63   114.7  114.76  114.87  114.89
     115  115.01  115.03  115.07  115.07  115.11  115.11  115.16  115.17   115.2
  115.25  115.28   115.3  115.33  115.34  115.39   115.4  115.42  115.37  115.37
  115.32   115.3  115.27  115.22  115.19  115.15  115.06     115  114.99  114.91
  114.91  114.86  114.84   114.8  114.79  114.72  114.67  114.56  114.55  114.41
   114.4  114.25  114.22   114.1  114.06  113.96  113.94  113.83  113.79  113.75
  113.72  113.72  113.73  113.69  113.67  113.65  113.65
                                                                        
 1811.55 1816.19 1816.29 1816.37 1816.39 1816.49  1816.6 1816.71 1816.82 1816.93
 1817.05 1817.17 1817.29 1817.41 1817.54 1817.67  1817.8 1817.93 1818.07 1818.21
 1818.35 1818.49 1818.64 1818.79 1818.94 1819.09 1819.24 1821.17 1823.23 1823.27
 1823.37 1823.41 1823.51 1823.55 1823.65 1823.69  1823.8 1823.84 1823.95 1823.99
  1824.1 1824.14 1824.25 1824.29  1824.4 1824.44 1824.55 1824.59 1824.71 1824.75
 1824.87 1824.91 1825.03 1825.07 1825.19 1825.23 1825.35 1825.39 1825.51 1825.55
 1825.67 1825.71 1825.83 1825.87 1825.95 1825.99 1826.03 1826.16  1826.2 1826.33
 1826.37  1826.4 1826.44 1826.48 1830.76 1833.17 1835.58  1840.4 1845.22  1849.8
 1850.04 1854.86 1857.51 1859.67 1864.49 1869.31 1872.65 1874.12 1878.94 1879.74
    1882  1882.3 1882.49 1882.65 1882.74 1882.91 1883.22 1883.75  1885.2 1888.53
 1891.75 1893.31 1896.42 1898.09 1901.07 1902.87 1905.22 1907.65 1912.17 1912.43
 1916.79 1917.21 1918.33 1921.57 1921.99  1926.5 1926.77 1931.55 1932.61 1936.33
 1941.11 1944.52 1945.89 1949.65 1950.85  1955.1 1955.81 1958.24 1960.77 1961.18
 1964.51 1965.73 1967.45 1970.69 1972.69 1975.65 1980.61 1984.32 1985.57 1989.95
 1990.53  1993.6 1995.49 1996.96 1998.18 2000.45 2002.25 2005.41 2005.85 2010.37
 2010.79 2015.33 2016.36 2020.29 2021.32 2024.79 2025.25 2028.87 2030.21 2031.09
 2032.11 2032.78 2033.37 2033.66 2033.86 2034.05 2034.22 2034.47 2034.67 2035.18
 2037.15 2057.83 2058.12 2058.15 2058.18 2058.21 2060.35 2060.35 2070.26
  111.54  111.51  111.51  111.52  111.52  111.52  111.52  111.53  111.53  111.53
  111.54  111.54  111.55  111.55  111.56  111.56  111.57  111.57  111.58  111.58
  111.59   111.6   111.6  111.61  111.62  111.63  111.63  111.68  111.74  111.74
  111.75  111.75  111.75  111.76  111.76  111.76  111.77  111.77  111.78  111.78
  111.79  111.79   111.8   111.8   111.8   111.8  111.81  111.81  111.82  111.82
  111.83  111.83  111.84  111.84  111.85  111.85  111.86  111.85  111.86  111.86
  111.87  111.87  111.88  111.88  111.89  111.89  111.89   111.9   111.9  111.91
  111.91  111.91  111.91   111.9  112.23  112.42   112.6  112.97  113.33  113.68
   113.7  113.99  114.15  114.31  114.66     115  115.24  115.33   115.6  115.65
  115.78  115.78  115.79  115.78  115.78  115.79  123.24  123.25  123.28  123.36
  123.43  123.47  123.55  123.59  123.67  123.71  123.78  123.84  123.95  123.97
  124.08  124.09  124.11  124.15  124.15  124.19  124.19  124.24  124.25  124.28
  124.33  124.36  124.38  124.41  124.42  124.47  124.48   124.5  124.45  124.45
   124.4  124.38  124.35   124.3  124.27  124.23  124.14  124.08  124.07  123.99
  123.99  123.94  123.92  123.88  123.87   123.8  123.75  123.64  123.63  123.49
  123.48  123.33   123.3  123.18  123.14  123.04  123.02  122.91  122.87  122.83
   122.8   122.8  122.81  122.77  122.75  122.73  122.73  115.78  115.79  115.77
  115.71  115.23  115.18  115.17  115.17  115.16  115.13  115.13  114.93
                                                                                
                                                                                
                                                                                
                                                                                
                                                                                
                                                                                
                                                                                
                                                                                
                                                                                
                                                  114.16  114.17   114.2  114.28
  114.35  114.39  114.47  114.51  114.59  114.63   114.7  114.76  114.87  114.89
     115  115.01  115.03  115.07  115.07  115.11  115.11  115.16  115.17   115.2
  115.25  115.28   115.3  115.33  115.34  115.39   115.4  115.42  115.37  115.37
  115.32   115.3  115.27  115.22  115.19  115.15  115.06     115  114.99  114.91
  114.91  114.86  114.84   114.8  114.79  114.72  114.67  114.56  114.55  114.41
   114.4  114.25  114.22   114.1  114.06  113.96  113.94  113.83  113.79  113.75
  113.72  113.72  113.73  113.69  113.67  113.65  113.65
                                                                        
BR Coef=-1 , 0 , 0 ,, 0 ,,,0.8,-1,,0,
WSPro=,,,, 1 ,,,, 0 ,,,, 0 ,,,,-1 ,-1 ,-1 , 0 , 0 , 0 , 0 , 0
BC Design=,, 0 ,, 0 ,,,,,,
BC Use User HTab Curves=0
BC User HTab FreeFlow(D)= 0

Type RM Length L Ch R = 1 ,33778.27,32.89,40.31,33.48
BEGIN DESCRIPTION:
Downstream Section - HEATHERGOLD
END DESCRIPTION:
XS GIS Cut Line= 6
3012723.0091836213856689.39669913012465.5881105213856437.7334885
3011600.1196971113854424.1571351 3011554.9114542  13854180.72816
3011547.9564156113852905.22644593010211.6542981913850492.0790413
#Sta/Elev= 30
       0   116.2     215  112.85     265  115.18  704.73  114.66  809.65  111.06
  974.52  113.78 1818.86  112.24 1887.23  108.77 1898.11  104.35 1931.49   99.01
 1969.26   97.22 1988.12   99.14 2011.69  102.25 2015.46     109 2040.23  108.64
 2094.91   111.7 3029.77  110.32 3204.16  113.79 3313.77  109.65 3453.28  113.78
 3572.86  109.88 3722.34  112.46 3966.48  109.75 4399.86  113.27 4628.98   111.3
 4773.43  114.69  4963.1  111.63 5342.47  114.58 5931.49  112.12 6834.99  115.38
#Mann= 7 ,-1 , 0
       0     .15       0 1818.86     .04       0 1898.11    .015       0
 1931.49     .04       0 1988.12    .015       0 2040.23     .04       0
 2094.91     .15       0
#XS Ineff= 4 ,-1
       0  974.52  113.78  974.52 1883.22   110.4 2034.22 4399.86     109
 4399.86 6834.99  113.78
Permanent Ineff=
       F       F       F       F
Bank Sta=1818.86,2094.91
XS Rating Curve= 0 ,0
Exp/Cntr=0.5,0.3

Type RM Length L Ch R = 1 ,33737.95,323.51,317,292.43
XS GIS Cut Line= 6
3012752.0196242813856673.9072288 3012494.598551213856422.2440182
3011629.1304658713854408.66766483011583.9222229413854165.2386897
3011576.9671843613852889.73697563010240.6650669413850476.5892428
#Sta/Elev= 30
       0   115.6  749.69  114.44  789.66   110.9  904.57  113.76 1793.88  112.23
 1887.71  108.71 1888.54  105.83 1926.41   98.34 1964.27    98.2 2006.86  101.61
 2008.21  107.98 2015.72  109.32 2084.97  112.15 2263.91  109.64 2393.14  113.68
 3109.49  113.58 3263.95   112.4 3293.84  109.39 3443.32  113.56 3582.83  109.73
 3622.69  112.31 3951.54  109.59 4360.01  113.72 4584.16  111.18 4708.68  114.42
 4943.14  111.64 5222.67   114.4 6096.22  116.02 6295.89  112.15 6834.99  115.18
#Mann= 3 ,-1 , 0
       0     .15       0 1793.88     .04       0 2084.97     .15       0
#XS Ineff= 2 ,-1
       0  904.57   113.5 4449.67 6834.99   113.5
Permanent Ineff=
       F       F
Bank Sta=1793.88,2084.97
XS Rating Curve= 0 ,0
Exp/Cntr=0.3,0.1

Type RM Length L Ch R = 1 ,33420.95,1058.92,1268.65,1399.73
Node Name=N
XS GIS Cut Line= 6
3012956.6077977713856791.69636333012206.0000470313854886.9898708
3012029.5099144413854696.2500948 3011812.340073213854435.2801443
3011727.5498884513852986.13015553010750.3179190313850464.1145303
#Sta/Elev= 30
       0   115.7  279.63   112.7  773.97  114.18  803.93  110.73  883.82  113.32
 1557.93  110.41 1637.82  112.79 2012.32  111.97 2120.86  108.03 2141.77   99.75
 2179.57   96.02 2237.18  107.77 2319.29   111.6  2476.9  109.53 2681.58  112.69
  3060.7  108.65  3320.1  111.79 3429.85  109.35 3479.74  113.05  3579.5  114.18
 3694.24  109.53 3813.96  112.03 3833.92  109.69 4088.33  109.31 4368.28     110
 4633.26  114.78 4678.25  111.46 4748.25  113.67 5018.22  111.19 6803.06  114.74
#Mann= 3 ,-1 , 0
       0     .15       0 2012.32     .04       0 2319.29     .15       0
#XS Ineff= 2 ,-1
       0  883.82   112.7 4633.26 6803.06   112.7
Permanent Ineff=
       F       F
Bank Sta=2012.32,2319.29
XS Rating Curve= 0 ,0
Exp/Cntr=0.3,0.1

Type RM Length L Ch R = 1 ,32152.3 ,298.98,404.9,628.65
Node Name=M
XS GIS Cut Line= 5
 3013283.264296713856698.36584133013116.9700098613854122.9198767
3012940.4798772813853942.03998913012367.6365347813852879.0073383
 3010958.802410213850091.0371924
#Sta/Elev= 30
       0  114.06  363.75  113.05  787.93  112.27 1857.86  109.45 2180.44   107.6
 2549.26  107.09 2630.36   108.6 2670.87   98.57 2714.37   96.79 2738.46   97.17
 2798.83  109.26 2856.55   106.8 3117.72  107.04 3427.33  107.47 3452.28  110.23
 3577.96  107.81 4066.09   111.2 4135.39   107.4 4161.05  100.19 4206.03  109.26
 4380.96  113.09  4500.9  109.73 4665.84  113.51 5195.62   109.9 5550.47  113.43
 6345.14  111.23 6759.17  114.73 6834.94  109.22 6854.93  114.16  7164.8  114.82
#Mann= 13 ,-1 , 0
       0     .15       0  363.75      .1       0  787.93     .15       0
 1857.86     .07       0 2180.44     .12       0 2549.26     .07       0
 2630.36     .04       0 2798.83     .07       0 2856.55     .12       0
 3117.72     .07       0 3577.96     .12       0 4135.39     .15       0
 6759.17      .1       0
#XS Ineff= 3 ,-1
       0 1093.23     112 1093.23 2071.79  109.28 4066.09  7164.8   110.5
Permanent Ineff=
       F       F       F
Bank Sta=2630.36,2798.83
XS Rating Curve= 0 ,0
Exp/Cntr=0.3,0.1