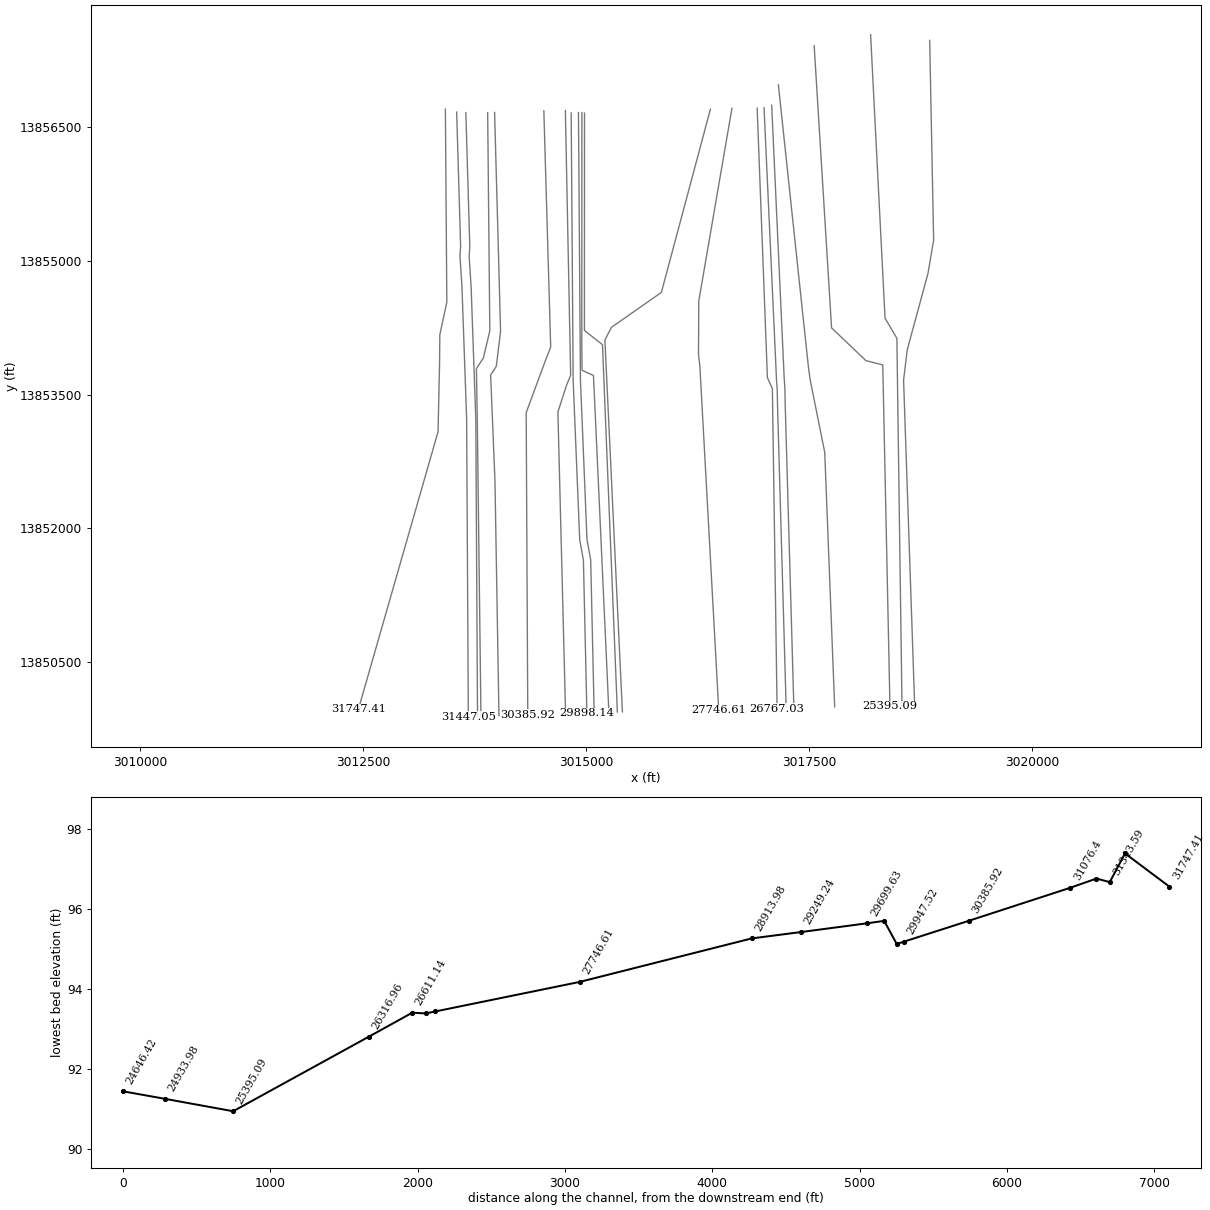
HEC-RAS study U101-00-00.prj: U101-00-00 2019 (Re-Study)

--- U101-00-00.g01 (geometry) --- (continued)

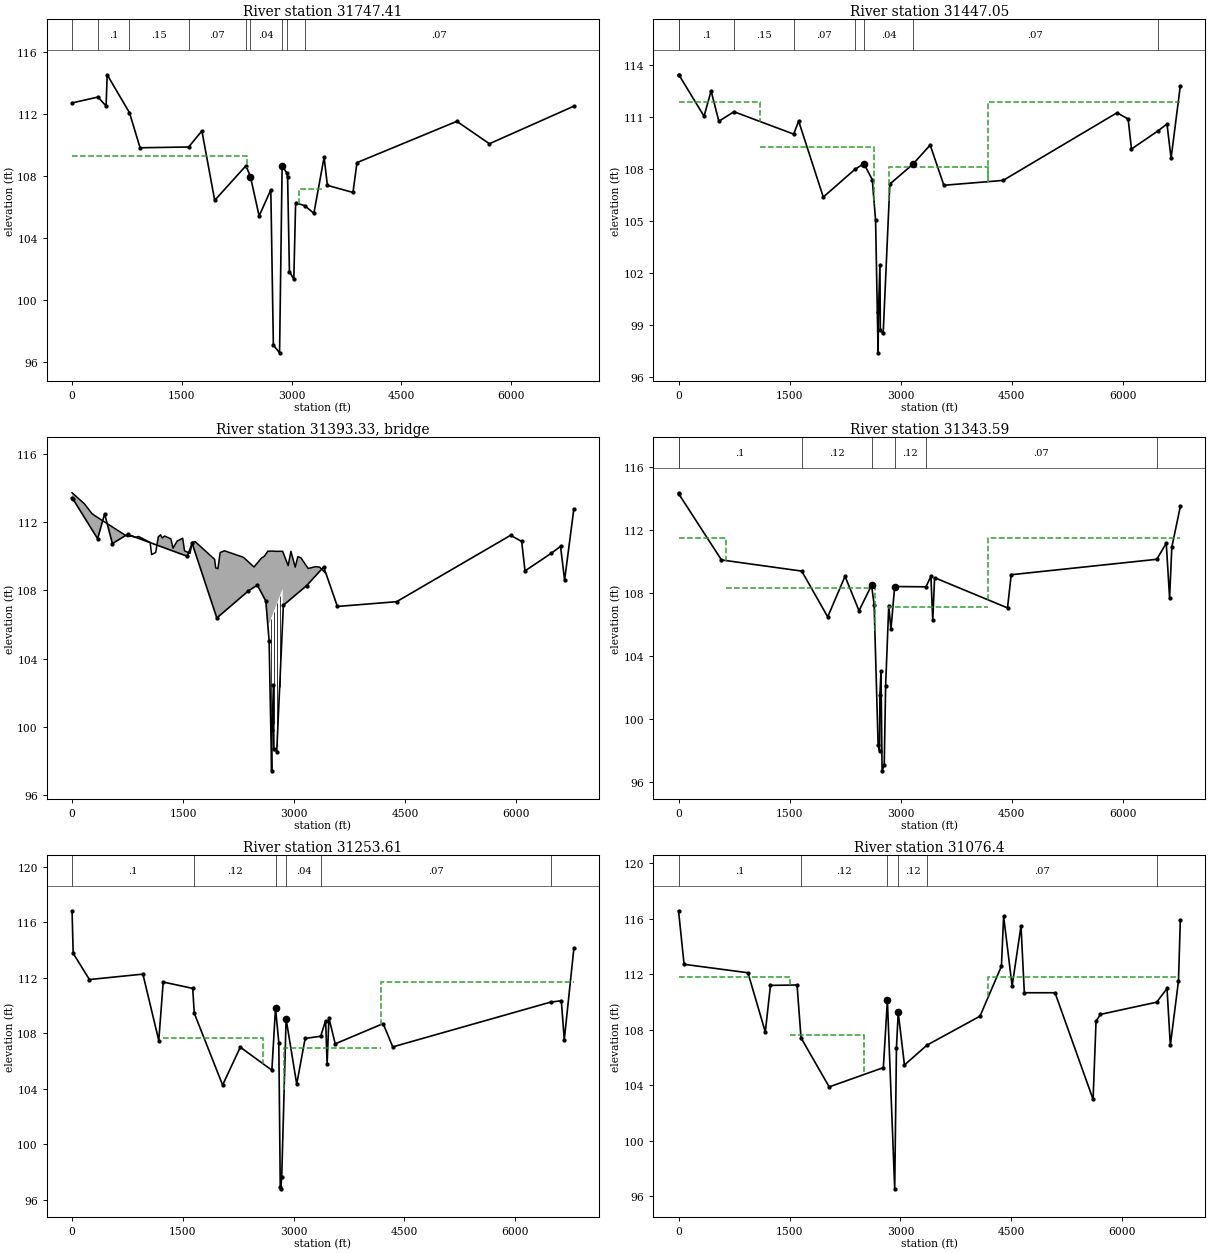
Type RM Length L Ch R = 1 ,31747.41,181.57,300.35,306.36
XS GIS Cut Line= 6
 3013423.260079713856698.3658413 3013439.510047213854534.7799454
3013361.1099415313854170.78985973013357.7900662713853831.7298423
3013341.1001390213853083.81992083012449.1767260313849976.2637999
#Sta/Elev= 30
       0  112.73  354.38  113.11  464.71  112.53   479.7  114.55  783.88   112.1
  929.42  109.83 1593.17  109.88 1773.89  110.92 1948.78  106.43  2376.1  108.67
 2436.69  107.97 2555.92  105.42 2715.49  107.11 2750.39   97.07 2835.16   96.57
 2870.06  108.67 2934.09   108.2 2944.87  107.94 2969.81  101.82 3029.65  101.34
 3054.59  106.27 3178.11  106.09 3303.96  105.59  3443.6  109.22 3488.49   107.4
 3838.02  106.94 3892.98  108.87 5257.14  111.54 5701.86  110.09 6856.15  112.52
#Mann= 9 ,-1 , 0
       0     .15       0  354.38      .1       0  783.88     .15       0
 1593.17     .07       0  2376.1     .12       0 2436.69     .04       0
 2870.06     .07       0 2934.09     .12       0 3178.11     .07       0
#XS Ineff= 3 ,-1
       0 2389.13  109.28 3103.38  3443.6  107.16  3443.6 6856.15  109.22
Permanent Ineff=
       F       F       F
Bank Sta=2436.69,2870.06
XS Rating Curve= 0 ,0
Exp/Cntr=0.5,0.3

Type RM Length L Ch R = 1 ,31447.05,162.55,103.46,103.36
BEGIN DESCRIPTION:
Upstream Section - GREENHOUSE ROAD
END DESCRIPTION:
XS GIS Cut Line= 6
 3013549.559039713856664.36590933013594.0123628713855161.4223928
3013586.6035850213855053.46460353013608.8299185313854711.5978332
3013661.3075038613853224.6418176 3013680.348148213849892.2177082
#Sta/Elev= 30
       0  113.43    9.85  113.39  344.68  111.04  439.59   112.5  544.49  110.75
  748.43   111.3 1554.26  110.01 1621.74  110.76  1954.4  106.38 2379.44  107.97
 2501.56  108.31 2615.96  107.38 2660.29  105.05 2694.48    97.4 2699.37   99.78
 2719.39  102.44 2724.72    98.7 2763.15   98.53 2852.87  107.13 3165.75  108.28
 3397.45  109.38  3582.3  107.06  4381.7  107.34 5920.54  111.24 6070.42  110.88
 6115.39  109.15 6468.07  110.18 6595.03  110.59 6649.98  108.61 6774.89   112.8
#Mann= 8 ,-1 , 0
       0     .15       0    9.85      .1       0  748.43     .15       0
 1554.26     .07       0 2379.44     .12       0 2501.56     .04       0
 3165.75     .07       0 6468.07     .12       0
#XS Ineff= 4 ,-1
       0 1103.97  111.86 1103.97 2642.72  109.28 2842.92    4184   108.1
    4184 6774.89  111.86
Permanent Ineff=
       F       F       F       F
Bank Sta=2501.56,3165.75
XS Rating Curve= 0 ,0
Exp/Cntr=0.5,0.3

Type RM Length L Ch R = 3 ,31393.33,,,
BEGIN DESCRIPTION:
GREENHOUSE ROAD
END DESCRIPTION:
Node Name=GREENHOUSE ROAD
Bridge Culvert--1,0,-1,-1, 0
Deck Dist Width WeirC Skew NumUp NumDn MinLoCord MaxHiCord MaxSubmerge Is_Ogee
11,79,2.6,0, 57, 57, , , 0.98, 0, 0,0,,
       0  164.85  269.75   319.7   749.3  799.26  854.21  899.16 1054.02    1074
 1128.95 1163.92 1193.89 1218.86 1248.84 1333.76 1363.73 1418.68 1493.61 1518.35
 1592.14 1621.74 1661.46 1924.61  1939.5 1969.32 1999.17 2058.86 2312.54 2456.79
 2556.27 2596.07 2640.75 2642.72 2709.14 2718.91 2728.68 2743.34 2748.22 2767.76
 2781.84 2791.23 2810.01 2824.09 2833.48 2842.92 2847.87 2872.85 2917.81 2955.02
 3012.74 3047.71 3087.68 3187.61 3287.53 3342.49 3412.43
  113.74   113.1  112.51  112.36  111.16   111.2  111.12  111.17  110.82  110.11
  110.23  111.15  111.27  111.08   111.2  111.03  110.49   110.9  111.07  110.33
  110.18  110.82  110.87  109.83  109.33  109.28  110.23  110.33  109.95  109.38
   109.9  110.01  110.29  110.31  110.31  110.31  110.31   110.3   110.3   110.3
   110.3   110.3   110.3   110.3   110.3   110.3  110.25  109.96  109.46   110.3
  109.37  109.98  109.93  109.29   109.4  109.37  109.06
       0       0       0       0       0       0       0       0       0       0
       0       0       0       0       0       0       0       0       0       0
       0       0       0       0       0       0       0       0       0       0
       0       0       0  105.85   106.6  106.71  106.82  106.98  107.04  107.26
  107.41  107.52  107.73  107.89  107.99   108.1       0       0       0       0
       0       0       0       0       0       0       0
       0  164.85  269.75   319.7   749.3  799.26  854.21  899.16 1054.02    1074
 1128.95 1163.92 1193.89 1218.86 1248.84 1333.76 1363.73 1418.68 1493.61 1518.35
 1592.14 1621.74 1661.46 1924.61  1939.5 1969.32 1999.17 2058.86 2312.54 2456.79
 2556.27 2596.07 2640.75 2642.72 2709.14 2718.91 2728.68 2743.34 2748.22 2767.76
 2781.84 2791.23 2810.01 2824.09 2833.48 2842.92 2847.87 2872.85 2917.81 2955.02
 3012.74 3047.71 3087.68 3187.61 3287.53 3342.49 3412.43
  113.74   113.1  112.51  112.36  111.16   111.2  111.12  111.17  110.82  110.11
  110.23  111.15  111.27  111.08   111.2  111.03  110.49   110.9  111.07  110.33
  110.18  110.82  110.87  109.83  109.33  109.28  110.23  110.33  109.95  109.38
   109.9  110.01  110.29  110.31  110.31  110.31  110.31   110.3   110.3   110.3
   110.3   110.3   110.3   110.3   110.3   110.3  110.25  109.96  109.46   110.3
  109.37  109.98  109.93  109.29   109.4  109.37  109.06
       0       0       0       0       0       0       0       0       0       0
       0       0       0       0       0       0       0       0       0       0
       0       0       0       0       0       0       0       0       0       0
       0       0       0  105.85  106.56  106.67  106.77  106.93  106.98  107.19
  107.34  107.44  107.65   107.8   107.9     108       0       0       0       0
       0       0       0       0       0       0       0
Pier Skew, UpSta & Num, DnSta & Num=  ,2682.72, 2 ,2682.72, 2 , 0 , 0 , 0 ,,
     1.4     1.4
      95     109
     1.4     1.4
      95     109
Pier Skew, UpSta & Num, DnSta & Num=  ,2722.62, 2 ,2722.62, 2 , 0 , 0 , 0 ,,
     1.4     1.4
      95     109
     1.4     1.4
      95     109
Pier Skew, UpSta & Num, DnSta & Num=  ,2766.52, 2 ,2766.52, 2 , 0 , 0 , 0 ,,
     1.4     1.4
      95     109
     1.4     1.4
      95     109
Pier Skew, UpSta & Num, DnSta & Num=  ,2802.62, 2 ,2802.62, 2 , 0 , 0 , 0 ,,
     1.4     1.4
      95     109
     1.4     1.4
      95     109
Abutment Skew #Up #Dn= , 2 , 2
 2610.82 2616.02
  107.85  106.57
 2610.82 2616.02
  107.75  106.47
Abutment Skew #Up #Dn= , 2 , 2
 2869.32 2874.41
   106.3  107.74
 2869.32 2874.41
   106.2  107.64
BR Coef=-1 , 1 , 1 ,0.9, 0 ,,,0.8,-1,1.2,0,
WSPro=,,,, 1 ,,,, 0 ,,,, 0 ,,,,-1 ,-1 ,-1 , 0 , 0 , 0 , 0 , 0
BC Design=,, 0 ,, 0 ,,,,,,
BC Use User HTab Curves=0
BC User HTab FreeFlow(D)= 0

Type RM Length L Ch R = 1 ,31343.59,222.57,89.98,22.72
BEGIN DESCRIPTION:
Downstream Section - GREENHOUSE ROAD
END DESCRIPTION:
Node Name=L
XS GIS Cut Line= 6
3013652.3846214413856659.26847853013696.8379446113855156.3249621
3013689.4291667813855048.36717283013711.6555002813854706.5004024
3013764.1330856113853219.54438683013783.1737299413849887.1202774
#Sta/Elev= 30
       0  114.36    2.72  114.29  579.46  110.09 1663.28  109.38 2014.09  106.47
 2247.88  109.05 2436.89  106.86 2606.01  108.48 2640.74  107.25 2694.48   98.35
 2714.02   97.95 2718.91  101.51 2733.56  103.01 2748.22   96.68 2777.15   97.06
 2795.93  102.08 2838.18  107.19 2867.85  105.67 2917.82   108.4 3340.45  108.38
 3407.44  109.05 3432.42  106.25  3457.4  108.96 4441.65  107.04 4491.62  109.15
 6456.29  110.13 6585.03  111.15    6630  107.66 6659.98   110.9 6774.89  113.49
#Mann= 7 ,-1 , 0
       0     .15       0    2.72      .1       0 1663.28     .12       0
 2606.01     .04       0 2917.82     .12       0 3340.45     .07       0
 6456.29     .12       0
#XS Ineff= 4 ,-1
       0   644.4  111.47   644.4 2651.51  108.28 2842.92    4184   107.1
    4184 6774.89  111.47
Permanent Ineff=
       F       F       F       F
Bank Sta=2606.01,2917.82
XS Rating Curve= 0 ,0
Exp/Cntr=0.5,0.3

Type RM Length L Ch R = 1 ,31253.61,118.99,177.21,168.05
XS GIS Cut Line= 6
3013897.0271767813856657.80391453013921.0327061913854213.9190385
3013849.0216953613853910.39044613013770.64652403 13853790.417917
3013780.6789842713853215.27700693013821.8659097713849892.7206599
#Sta/Elev= 30
       0  116.83   14.99  113.76   234.9  111.87  959.61  112.26 1174.52  107.47
  1234.5  111.69 1634.33  111.23 1655.28  109.44 2039.17  104.26 2279.07  106.99
 2706.45  105.33 2755.96  109.82 2800.37  107.32  2820.1   96.92 2825.04   96.77
 2839.87    97.6 2899.27  109.03 3043.07  104.32 3157.13  107.62 3367.86  107.78
 3434.82  108.91 3454.66  105.79 3479.49  109.09 3564.43  107.23    4214  108.69
 4343.92  107.01 6481.85  110.24 6627.35  110.34 6667.33  107.52 6797.24  114.11
#Mann= 6 ,-1 , 0
       0      .1       0 1655.28     .12       0 2755.96     .06       0
 2899.27     .04       0 3367.86     .07       0 6481.85     .12       0
#XS Ineff= 4 ,-1
       0  1234.5  111.69  1234.5 2583.01  107.66 2872.44    4184   106.9
    4184 6797.24  111.72
Permanent Ineff=
       F       F       F       F
Bank Sta=2755.96,2899.27
XS Rating Curve= 0 ,0
Exp/Cntr=0.3,0.1

Type RM Length L Ch R = 1 ,31076.4 ,611.66,690.48,421.95
XS GIS Cut Line= 6
3013974.6575989413856660.29373893014041.6174387813854205.7661677
3013993.3921415213853816.21510953013930.1767167713853719.2392536
3013978.7996510313852534.97620223014023.4166877713849902.1363235
#Sta/Elev= 30
       0  116.59   74.86  112.73  938.26  112.12 1172.82  107.85  1242.7  111.21
 1602.03  111.24 1655.63  107.43 2036.23  103.89 2768.48  105.28 2823.13  110.13
 2921.94   96.54 2945.54  106.71 2969.14  109.26  3053.8  105.47 3357.75   106.9
 4074.73  108.99 4364.28  112.59 4394.26  116.18 4509.18  111.16  4629.1   115.5
 4674.07  110.68 5088.79  110.68 5603.43  102.99 5643.41  108.63 5703.37  109.12
 6463.62     110 6602.75  110.99 6647.72  106.89 6757.64  111.53 6782.63  115.92
#Mann= 6 ,-1 , 0
       0      .1       0 1655.63     .12       0 2823.13     .06       0
 2969.14     .12       0 3357.75     .07       0 6463.62     .12       0
#XS Ineff= 4 ,-1
       0 1502.21  111.79 1502.21 2512.83  107.66 3007.88  4184.4   106.9
  4184.4 6782.63  111.78
Permanent Ineff=
       F       F       F       F
Bank Sta=2823.13,2969.14
XS Rating Curve= 0 ,0
Exp/Cntr=0.3,0.1

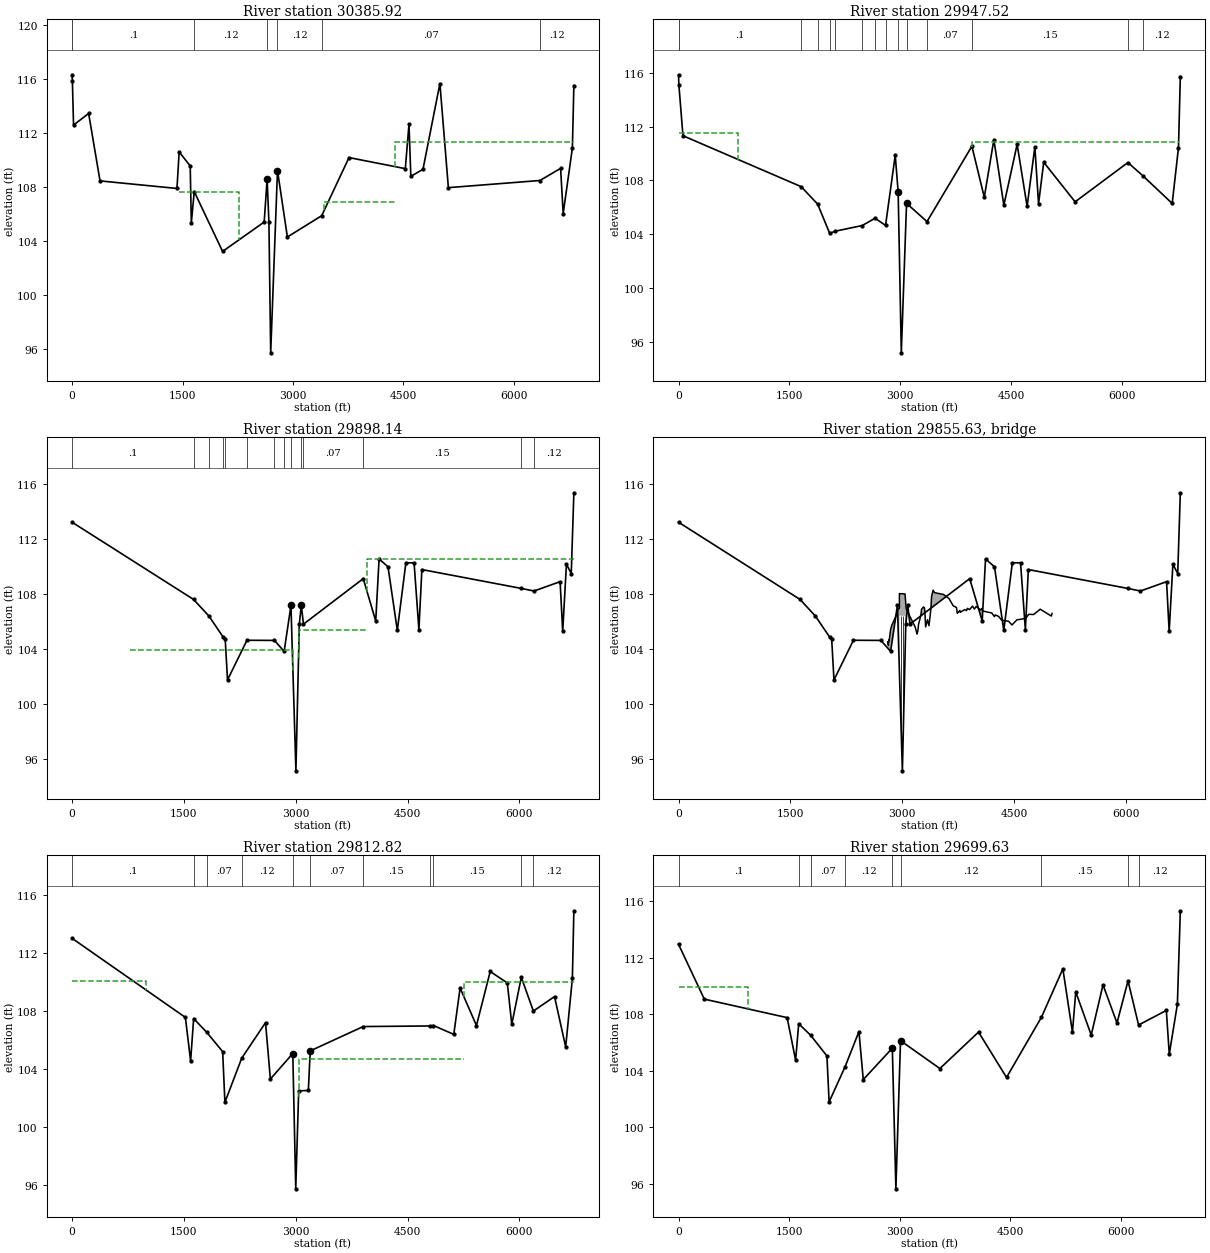
Type RM Length L Ch R = 1 ,30385.92,233.54,438.4,453.15
Node Name=K
XS GIS Cut Line= 6
3014526.3546582813856678.19855883014603.0034551213854035.1244486
3014583.48741803 13853979.850609 3014552.279147113853903.8379658
3014328.5036760313853297.35328643014346.2027876113849913.6723897
#Sta/Elev= 30
       0  116.33     4.4  115.86   19.99   112.6  224.93  113.46  379.88  108.46
 1424.56   107.9 1454.56  110.61 1604.51  109.57 1619.51  105.35 1659.59  107.66
 2044.38  103.23 2609.21  105.41 2649.08  108.59 2673.51   105.4 2697.61   95.71
 2789.96  109.23 2924.23   104.3 3390.53  105.88 3761.32  110.19 4526.03  109.37
 4576.01  112.66    4601   108.8 4765.93  109.32 4995.85  115.68  5110.8  107.96
 6354.35  108.49 6635.22  109.39 6670.21  106.04 6795.16   110.9 6815.15  115.53
#Mann= 7 ,-1 , 0
       0     .15       0     4.4      .1       0 1659.59     .12       0
 2649.08     .06       0 2789.96     .12       0 3390.53     .07       0
 6354.35     .12       0
#XS Ineff= 4 ,-1
       0 1454.56  110.61 1454.56 2261.78  107.66 3425.89 4391.08   106.9
 4391.08 6815.15  111.31
Permanent Ineff=
       F       F       F       F
Bank Sta=2649.08,2789.96
XS Rating Curve= 0 ,0
Exp/Cntr=0.3,0.1

Type RM Length L Ch R = 1 ,29947.52,42.33,49.38,190.41
XS GIS Cut Line= 6
3014767.37090853 13856682.9711873014826.72741711 13853716.693655
3014808.7523874513853672.98967423014783.3210078613853612.0078408
 3014683.743451113853305.56422793014769.8203786913849919.8639784
#Sta/Elev= 30
       0  115.85    4.42  115.11   59.94  111.32 1658.31  107.54 1882.39  106.24
 2044.98  104.07 2122.57  104.23 2486.14  104.65 2658.87  105.19  2800.9  104.66
 2931.92  109.87 2971.61  107.15 3014.05   95.19 3085.17   106.3 3361.62  104.94
  3969.1  110.54 4136.74  106.75 4266.63  111.03  4401.5  106.16 4581.34  110.68
 4716.22  106.07 4821.12  110.49 4871.08  106.27 4941.01  109.35 5365.63  106.41
 6080.34  109.33 6281.26  108.35 6679.43  106.29 6764.36  110.44 6789.33  115.72
#Mann= 15 ,-1 , 0
       0     .15       0    4.42      .1       0 1658.31     .12       0
 1882.39     .07       0 2044.98     .12       0 2122.57     .07       0
 2486.14     .12       0 2658.87     .07       0  2800.9     .12       0
 2971.61     .06       0 3085.17     .12       0 3361.62     .07       0
  3969.1     .15       0 6080.34     .07       0 6281.26     .12       0
#XS Ineff= 4 ,-1
       0  809.15  111.51  809.15 2856.82  102.93 3132.22  3971.9   105.4
  3971.9 6789.33  110.82
Permanent Ineff=
       F       F       F       F
Bank Sta=2971.61,3085.17
XS Rating Curve= 0 ,0
Exp/Cntr=0.5,0.3

Type RM Length L Ch R = 1 ,29898.14,85.52,85.31,81.67
BEGIN DESCRIPTION:
Upstream Section - WEST PARK VIEW DR
END DESCRIPTION:
XS GIS Cut Line= 6
3014832.5827203513856655.03161043014854.6571512813853655.1904972
3014857.0508472813853600.84218073014928.2252456113851869.9263512
3014969.5447167813851645.45829623015008.5183921213849930.6208466
#Sta/Elev= 30
       0   113.2 1628.94  107.59 1835.79  106.38 2029.24  104.83 2053.88  104.72
 2084.82  101.74 2345.72  104.62 2714.28  104.61 2844.42  103.81 2935.81  107.15
 3002.32   95.13 3047.64  105.77  3074.3  107.15 3103.62  105.79 3905.35   109.1
 4072.79  106.02 4117.73  110.53 4237.54  109.96 4362.35  105.34 4477.17  110.25
    4587  110.25  4651.9   105.4 4691.84  109.76 6024.09  108.39 6195.87   108.2
 6545.73  108.88 6580.63  105.27  6630.5  110.15 6695.32  109.47 6730.22  115.34
#Mann= 14 ,-1 , 0
       0      .1       0 1628.94     .12       0 1835.79     .07       0
 2029.24     .12       0 2053.88     .07       0 2345.72     .12       0
 2714.28     .07       0 2844.42     .12       0 2935.81     .06       0
  3074.3     .12       0 3103.62     .07       0 3905.35     .15       0
 6024.09     .07       0 6195.87     .12       0
#XS Ineff= 4 ,-1
       0  774.93  110.48  774.93 2962.22  103.92 3037.11 3957.97   105.4
 3957.97 6730.22  110.56
Permanent Ineff=
       F       F       F       F
Bank Sta=2935.81,3074.3
XS Rating Curve= 0 ,0
Exp/Cntr=0.5,0.3

Type RM Length L Ch R = 3 ,29855.63,,,
BEGIN DESCRIPTION:
WEST PARK VIEW DR
END DESCRIPTION:
Node Name=WEST PARK VIEW
Bridge Culvert--1,0,-1,-1, 0
Deck Dist Width WeirC Skew NumUp NumDn MinLoCord MaxHiCord MaxSubmerge Is_Ogee
31.5,36,2.6,0, 60, 60, , , 0.98, 0, 0,0,,
 2804.75 2814.75 2819.75 2824.75 2844.75 2859.75 2917.24 2940.75 2962.12 2962.22
 3037.11 3037.22 3054.33 3174.15 3199.11  3209.1 3219.08 3249.04 3259.02 3283.98
 3298.96 3303.95 3313.94  3338.9 3358.87 3383.83 3393.82 3413.79 3433.76 3553.58
 3628.46 3683.38 3728.31  3738.3 3773.25 3778.24 3838.15 3863.11  3873.1 3903.05
 3942.99 3967.95 3992.91 4047.83  4067.8 4077.79 4202.59 4237.54 4247.52 4292.46
 4332.39 4427.25 4472.18 4537.08 4656.89 4696.83 4761.73 4851.19 5000.04 5009.96
   104.5  104.25  104.63  104.58  105.41   105.7  106.39  106.84  106.96  108.01
  107.99  107.99  106.89  105.58  105.07  105.27  105.77  106.41  106.87  107.04
  106.98  106.71  105.59  106.11  105.68  106.85   107.8  108.26  108.08  107.95
  107.65  107.13     107  106.58  106.79  106.65  106.85  106.77  106.94  106.85
   107.1  106.89  107.08  106.83  106.93  106.75   106.6  106.33  106.46  106.36
  106.09     106  105.73   106.1  106.21  106.51  106.49  106.88  106.38  106.57
       0       0       0       0       0       0       0       0       0  106.41
  106.39       0       0       0       0       0       0       0       0       0
       0       0       0       0       0       0       0       0       0       0
       0       0       0       0       0       0       0       0       0       0
       0       0       0       0       0       0       0       0       0       0
       0       0       0       0       0       0       0       0       0       0
 2804.75 2814.75 2819.75 2824.75 2844.75 2859.75 2917.24 2940.75 2962.12 2962.22
 3037.11 3037.22 3054.33 3174.15 3199.11  3209.1 3219.08 3249.04 3259.02 3283.98
 3298.96 3303.95 3313.94  3338.9 3358.87 3383.83 3393.82 3413.79 3433.76 3553.58
 3628.46 3683.38 3728.31  3738.3 3773.25 3778.24 3838.15 3863.11  3873.1 3903.05
 3942.99 3967.95 3992.91 4047.83  4067.8 4077.79 4202.59 4237.54 4247.52 4292.46
 4332.39 4427.25 4472.18 4537.08 4656.89 4696.83 4761.73 4851.19 5000.04 5009.96
   104.5  104.25  104.63  104.58  105.41   105.7  106.39  106.84  106.96  108.01
  107.99  107.99  106.89  105.58  105.07  105.27  105.77  106.41  106.87  107.04
  106.98  106.71  105.59  106.11  105.68  106.85   107.8  108.26  108.08  107.95
  107.65  107.13     107  106.58  106.79  106.65  106.85  106.77  106.94  106.85
   107.1  106.89  107.08  106.83  106.93  106.75   106.6  106.33  106.46  106.36
  106.09     106  105.73   106.1  106.21  106.51  106.49  106.88  106.38  106.57
       0       0       0       0       0       0       0       0       0  106.39
  106.37       0       0       0       0       0       0       0       0       0
       0       0       0       0       0       0       0       0       0       0
       0       0       0       0       0       0       0       0       0       0
       0       0       0       0       0       0       0       0       0       0
       0       0       0       0       0       0       0       0       0       0
Pier Skew, UpSta & Num, DnSta & Num=  ,2987.72, 2 ,2987.72, 2 , 0 , 0 , 0 ,,
     1.4     1.4
      95   106.5
     1.4     1.4
      95   106.5
Pier Skew, UpSta & Num, DnSta & Num=  ,3012.32, 2 ,3012.32, 2 , 0 , 0 , 0 ,,
     1.4     1.4
      95   106.5
     1.4     1.4
      95   106.5
Abutment Skew #Up #Dn= , 2 , 2
 2962.02 2976.52
  106.41   101.7
 2962.02 2976.52
  106.39  101.68
Abutment Skew #Up #Dn= , 2 , 2
 3028.02 3037.31
  102.43  106.39
 3028.02 3037.31
  102.41  106.37
BR Coef=-1 , 1 , 1 ,0.9, 0 ,,,0.8,-1,1.2,0,
WSPro=,,,, 1 ,,,, 0 ,,,, 0 ,,,,-1 ,-1 ,-1 , 0 , 0 , 0 , 0 , 0
BC Design=,, 0 ,, 0 ,,,,,,
BC Use User HTab Curves=0
BC User HTab FreeFlow(D)= 0

Type RM Length L Ch R = 1 ,29812.82,24.34,113.19,151.5
BEGIN DESCRIPTION:
Downstream Section - WEST PARK VIEW DR
END DESCRIPTION:
XS GIS Cut Line= 6
3014914.13997194 13856658.9082433014936.2144028513853659.0671299
3014938.6080988613853604.7188134 3015009.782497213851873.8029839
3015051.1019683613851649.33492893015090.0756436913849934.4974793
#Sta/Elev= 30
       0     113 1519.86  107.54 1589.86  104.54 1630.75  107.46 1803.39  106.53
 2019.82  105.18 2049.82  101.68 2275.45  104.73 2594.77  107.18 2659.77  103.29
 2960.47  105.05 2999.93   95.71 3039.49  102.47 3169.16   102.5 3194.12  105.23
 3904.43  106.91 4794.41  106.95  4847.3  106.98 5119.64  106.37 5204.41  109.57
  5423.8  106.98  5608.3  110.71 5837.67  109.92 5897.51  107.06 6025.27  110.31
 6187.15  107.98 6470.93  108.98 6620.52   105.5 6710.28  110.23 6730.22   114.9
#Mann= 11 ,-1 , 0
       0      .1       0 1630.75     .12       0 1803.39     .07       0
 2275.45     .12       0 2960.47     .06       0 3194.12     .07       0
 3904.43     .15       0 4794.41     .12       0  4847.3     .15       0
 6025.27     .07       0 6187.15     .12       0
#XS Ineff= 4 ,-1
       0  984.91  110.03  984.91 2962.22  102.93 3037.11 5254.27  104.67
 5254.27 6730.22  110.01
Permanent Ineff=
       F       F       F       F
Bank Sta=2960.47,3194.12
XS Rating Curve= 0 ,0
Exp/Cntr=0.5,0.3

Type RM Length L Ch R = 1 ,29699.63,30.89,450.4,111.14
XS GIS Cut Line= 6
 3014952.394816713856659.98402833014951.4243461913854021.0614846
3014954.6182374513853772.78475023015006.9143926913853747.2690532
3015082.2495438613853714.31669133015255.3344995213849934.8944601
#Sta/Elev= 30
       0  112.95  349.82  109.07 1474.24  107.76 1589.18  104.75 1631.13  107.33
 1793.57  106.51 2013.96  105.05 2043.94   101.8 2257.55  104.25 2448.73  106.77
 2507.42  103.38 2901.76   105.6 2950.32   95.65 3013.12  106.13 3547.41  104.16
 4072.18  106.74 4452.02  103.53 4925.97  107.79 5216.68  111.21 5346.63  106.74
 5391.61  109.58 5601.52  106.53 5761.45  110.08 5951.37  107.38 6100.96  110.36
 6244.38  107.24 6621.08  108.27 6661.06  105.18 6771.01  108.71 6810.99  115.32
#Mann= 9 ,-1 , 0
       0      .1       0 1631.13     .12       0 1793.57     .07       0
 2257.55     .12       0 2901.76     .06       0 3013.12     .12       0
 4925.97     .15       0 6100.96     .07       0 6244.38     .12       0
#XS Ineff= 4 ,-1
       0  949.51  109.91  949.51  2840.7  102.93 3345.85 5216.68  104.67
 5216.68 6810.99  111.21
Permanent Ineff=
       F       F       F       F
Bank Sta=2901.76,3013.12
XS Rating Curve= 0 ,0
Exp/Cntr=0.3,0.1

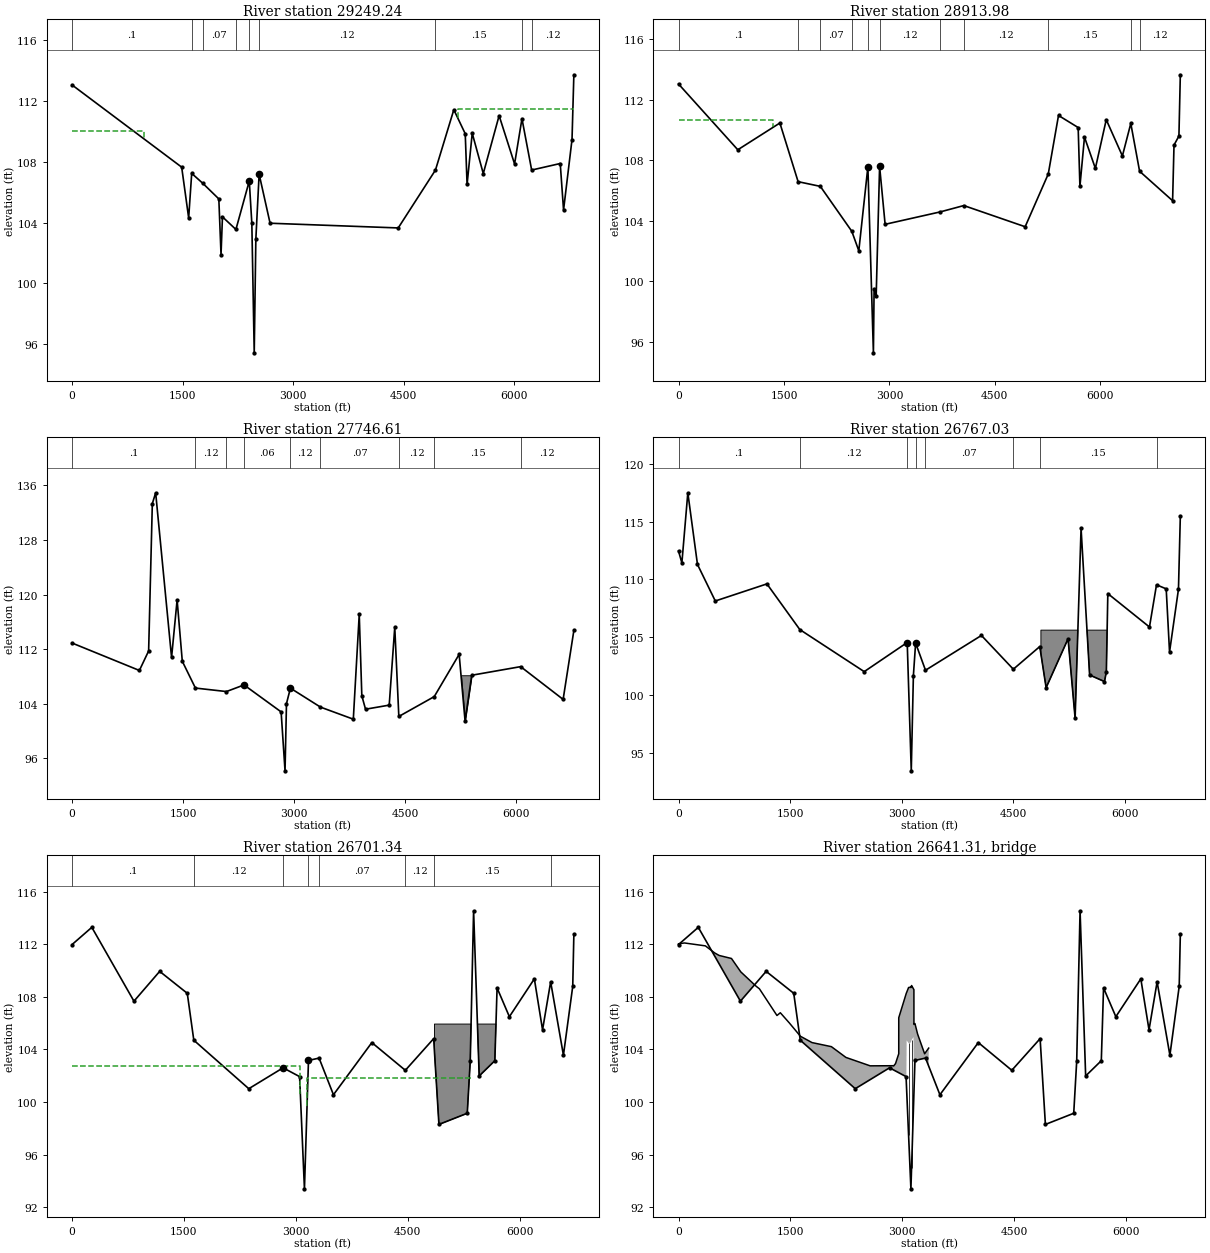
Type RM Length L Ch R = 1 ,29249.24,752.78,335.25,36.36
Node Name=J
XS GIS Cut Line= 6
3014981.7832093513856653.47091793014980.9872791913854636.4152408
3014980.98727919 13854456.2276093014980.9784209413854218.3832684
3015183.1886464513854058.74349593015349.9235491913849943.5860438
#Sta/Elev= 30
       0  113.06 1487.83  107.65 1582.69  104.31 1623.87  107.24 1773.94  106.59
  1992.1  105.56 2021.93   101.9 2041.41  104.38 2224.06  103.55 2405.36  106.74
 2440.05  103.96 2472.62   95.43 2494.55  102.91 2539.14  107.19 2687.77  103.96
 4427.12  103.65 4932.67  107.46 5181.84  111.43 5336.78  109.85 5361.77  106.51
 5431.74  109.88 5581.69  107.23  5796.6  111.04 6006.52  107.86 6106.78  110.84
 6238.36  107.46 6626.29  107.89 6671.27  104.83 6786.23  109.47 6811.22  113.73
#Mann= 9 ,-1 , 0
       0      .1       0 1623.87     .12       0 1773.94     .07       0
 2224.06     .12       0 2405.36     .06       0 2539.14     .12       0
 4932.67     .15       0 6106.78     .07       0 6238.36     .12       0
#XS Ineff= 2 ,-1
       0  978.57  110.03 5236.82 6811.22  111.48
Permanent Ineff=
       F       F
Bank Sta=2405.36,2539.14
XS Rating Curve= 0 ,0
Exp/Cntr=0.3,0.1

Type RM Length L Ch R = 1 ,28913.98,678.96,1167.38,1107.04
XS GIS Cut Line= 6
3016392.4411491913856697.28907183015842.9100960213854644.5599095
3015409.2000054413854341.07003093015284.2301110313854254.4599679
3015210.20007536 13854110.7401113015406.3401030313849945.3199642
#Sta/Elev= 30
       0  113.05  843.02   108.7 1441.62  110.47 1701.01  106.59    2017  106.28
  2464.6  103.31 2564.48  102.02 2693.61  107.57 2772.15   95.27  2781.9   99.49
 2811.32      99 2860.31   107.6 2938.69  103.77 3721.77  104.59 4058.28  105.01
 4930.79  103.61  5259.7   107.1 5405.23  110.97  5684.9  110.17 5709.87  106.28
  5774.8  109.54 5929.62  107.47 6084.43  110.69 6314.16  108.29 6433.57  110.44
 6558.78  107.28 7028.33  105.33  7048.3  109.01 7118.22  109.61  7138.2  113.66
#Mann= 11 ,-1 , 0
       0      .1       0 1701.01     .12       0    2017     .07       0
  2464.6     .12       0 2693.61     .06       0 2860.31     .12       0
 3721.77     .07       0 4058.28     .12       0  5259.7     .15       0
 6433.57     .07       0 6558.78     .12       0
#XS Ineff= 2 ,-1
       0 1346.84  110.64 5405.23  7138.2  110.97
Permanent Ineff=
       F       F
Bank Sta=2693.61,2860.31
XS Rating Curve= 0 ,0
Exp/Cntr=0.3,0.1

Type RM Length L Ch R = 1 ,27746.61,754.3,979.58,782.93
Node Name=I
XS GIS Cut Line= 5
3016633.4573994413856706.83432833016262.0700188613854549.5200734
 3016258.7898417 13853947.519965 3016274.130034113853819.2600509
3016485.5098606913849965.0699247
#Sta/Elev= 30
       0  112.91   909.6  108.89 1034.55  111.75 1084.53  133.34 1129.51  134.93
 1344.41   110.8 1419.38  119.22 1489.35  110.24 1666.78  106.31 2085.59   105.8
 2323.38  106.77 2824.78  102.82  2877.6   94.18 2897.14  104.03 2950.22   106.3
 3356.36  103.52 3800.23  101.75 3880.23   117.1 3915.23  105.18 3965.23  103.21
 4285.23  103.81 4360.23  115.24 4415.27  102.15  4893.9  105.06 5230.24  111.25
 5310.24  101.51 5400.24  108.19 6061.34  109.45 6635.25  104.65 6780.25  114.75
#Mann= 9 ,-1 , 0
       0      .1       0 1666.78     .12       0 2085.59     .07       0
 2323.38     .06       0 2950.22     .12       0 3356.36     .07       0
 4415.27     .12       0  4893.9     .15       0 6061.34     .12       0
#XS Ineff= 2 ,-1
       0 1419.38     110 5230.24 6780.25     110
Permanent Ineff=
       F       F
#Block Obstruct= 1 ,-1
 5230.24 5400.24  108.19
Bank Sta=2323.38,2950.22
XS Rating Curve= 0 ,0
Exp/Cntr=0.3,0.1

Type RM Length L Ch R = 1 ,26767.03,97.23,65.69,61.81
Node Name=H
XS GIS Cut Line= 4
3016915.9624118713856709.25558333017030.7098857813853690.9499401
3017086.4099056113853566.00990133017139.3799440313849977.7001488
#Sta/Elev= 30
       0  112.45   44.93  111.42  124.81  117.49  254.62  111.29  494.26  108.13
 1188.22  109.61 1630.33  105.66 2496.27  102.02 3074.22  104.54 3128.74   93.44
 3157.27  101.67 3187.26  104.49 3320.02  102.14 4071.95  105.15 4500.78  102.23
 4856.43  104.19 4941.61  100.63 5236.49  104.86 5331.46      98 5411.42  114.41
 5526.38  101.73  5726.3  101.16 5751.29     102 5771.28  108.77 6331.07  105.88
 6425.73  109.53 6555.98  109.18 6600.96  103.72 6720.91  109.15  6745.9  115.46
#Mann= 8 ,-1 , 0
       0      .1       0 1630.33     .12       0 3074.22     .06       0
 3187.26     .12       0 3320.02     .07       0 4500.78     .12       0
 4856.43     .15       0 6425.73     .12       0
#XS Ineff= 3 ,-1
       0 2931.49  102.52 3275.78 5401.43  101.79 5401.43  6745.9     109
Permanent Ineff=
       F       F       F
#Block Obstruct= 1 ,-1
 4871.64 5771.28  105.61
Bank Sta=3074.22,3187.26
XS Rating Curve= 0 ,0
Exp/Cntr=0.5,0.3

Type RM Length L Ch R = 1 ,26701.34,88.69,90.2,86.37
BEGIN DESCRIPTION:
Upstream Section - GROESCHKE RD
END DESCRIPTION:
XS GIS Cut Line= 6
3016993.0682287813856712.97637643017133.1972136113853656.8309139
3017136.2024569413853613.60068543017140.8615683613853546.5834309
 3017144.732951713853356.83676323017240.9758694513849989.7109515
#Sta/Elev= 30
       0  111.98  264.94  113.29  829.83  107.67 1174.75  109.94 1544.68  108.27
 1632.31   104.7 2369.51  101.01 2829.41   102.6 3050.81  101.93  3115.7   93.39
 3169.88  103.16 3311.84  103.34  3504.6  100.55 4019.38  104.52 4468.42  102.41
 4848.14  104.82 4918.94   98.29 5298.76   99.14 5338.74  103.11 5383.72  114.55
 5458.68  101.98 5668.58  103.14 5698.56  108.68 5863.48  106.49 6198.32  109.37
 6308.27  105.49 6416.94  109.14 6588.13  103.56 6713.07   108.8 6728.06  112.75
#Mann= 8 ,-1 , 0
       0      .1       0 1632.31     .12       0 2829.41     .06       0
 3169.88     .12       0 3311.84     .07       0 4468.42     .12       0
 4848.14     .15       0 6416.94     .12       0
#XS Ineff= 3 ,-1
       0 3060.78  102.74 3150.57 5378.72  101.79 5378.72 6728.06     109
Permanent Ineff=
       F       F       F
#Block Obstruct= 1 ,-1
 4858.97 5718.55  105.93
Bank Sta=2829.41,3169.88
XS Rating Curve= 0 ,0
Exp/Cntr=0.5,0.3

Type RM Length L Ch R = 3 ,26641.31,,,
BEGIN DESCRIPTION:
GROESCHKE RD
END DESCRIPTION:
Node Name=GROESCHKE RD
Bridge Culvert--1,0,-1,-1, 0
Deck Dist Width WeirC Skew NumUp NumDn MinLoCord MaxHiCord MaxSubmerge Is_Ogee
49,22.8,2.6,0, 40, 40, , , 0.98, 0, 0,0,,
       0   79.98  359.92   484.9  544.89  709.85  834.82 1039.78 1084.77 1319.72
 1364.71 1484.69 1634.66 1789.63 2049.57 2244.53 2569.47  2879.4 2884.03 2909.26
 2952.46 2952.58 3054.09 3058.73 3060.78 3084.49 3085.59 3101.38 3114.47 3115.68
 3124.62 3125.67 3148.18 3150.57 3156.04 3156.39 3169.87 3205.37 3299.42 3354.24
  112.04   112.1  111.88  111.34  111.15  110.92   109.9  108.81  108.61  106.58
  106.79  106.02     105  104.52  104.21  103.39  102.75  102.76  102.74  102.92
  103.67  106.41  108.28  108.34  108.37  108.71  108.71  108.73  108.72  108.71
  108.86  108.85  108.63   108.6  108.55   105.9  105.97  105.17  103.67   104.1
       0       0       0       0       0       0       0       0       0       0
       0       0       0       0       0       0       0       0       0       0
       0       0       0  104.68  104.67  104.48  104.47   104.5  104.53  104.55
   104.7  104.72  104.92  104.95       0       0       0       0       0       0
       0   79.98  359.92   484.9  544.89  709.85  834.82 1039.78 1084.77 1319.72
 1364.71 1484.69 1634.66 1789.63 2049.57 2244.53 2569.47  2879.4 2884.03 2909.26
 2952.46 2952.58 3054.09 3058.73 3060.78 3084.49 3085.59 3101.38 3114.47 3115.68
 3124.62 3125.67 3148.18 3150.57 3156.04 3156.39 3169.87 3205.37 3299.42 3354.24
  112.04   112.1  111.88  111.34  111.15  110.92   109.9  108.81  108.61  106.58
  106.79  106.02     105  104.52  104.21  103.39  102.75  102.76  102.74  102.92
  103.67  106.41  108.28  108.34  108.37  108.71  108.71  108.73  108.72  108.71
  108.86  108.85  108.63   108.6  108.55   105.9  105.97  105.17  103.67   104.1
       0       0       0       0       0       0       0       0       0       0
       0       0       0       0       0       0       0       0       0       0
       0       0       0  104.68  104.67  104.48  104.47   104.5  104.53  104.55
   104.7  104.72  104.92  104.95       0       0       0       0       0       0
Pier Skew, UpSta & Num, DnSta & Num=  ,3084.66, 2 ,3084.66, 2 , 0 , 0 , 0 ,,
    1.33    1.33
      90     105
    1.33    1.33
      90     105
Pier Skew, UpSta & Num, DnSta & Num=  ,3124.65, 2 ,3124.65, 2 , 0 , 0 , 0 ,,
    1.33    1.33
      90     105
    1.33    1.33
      90     105
Abutment Skew #Up #Dn= , 4 , 4
    3055 3060.93 3068.16 3074.61
  102.53  102.53  100.92   99.56
    3055 3060.93 3068.16 3074.61
  102.53  102.53  100.92   99.56
Abutment Skew #Up #Dn= , 4 , 4
 3131.19 3138.62 3148.13    3155
   98.67  100.02  102.72  102.72
 3131.19 3138.62 3148.13    3155
   98.67  100.02  102.72  102.72
BR Coef=-1 , 1 , 1 ,1.25, 0 ,,,0.8,-1,2,0,
WSPro=,,,, 1 ,,,, 0 ,,,, 0 ,,,,-1 ,-1 ,-1 , 0 , 0 , 0 , 0 , 0
BC Design=,, 0 ,, 0 ,,,,,,
BC Use User HTab Curves=0
BC User HTab FreeFlow(D)= 0

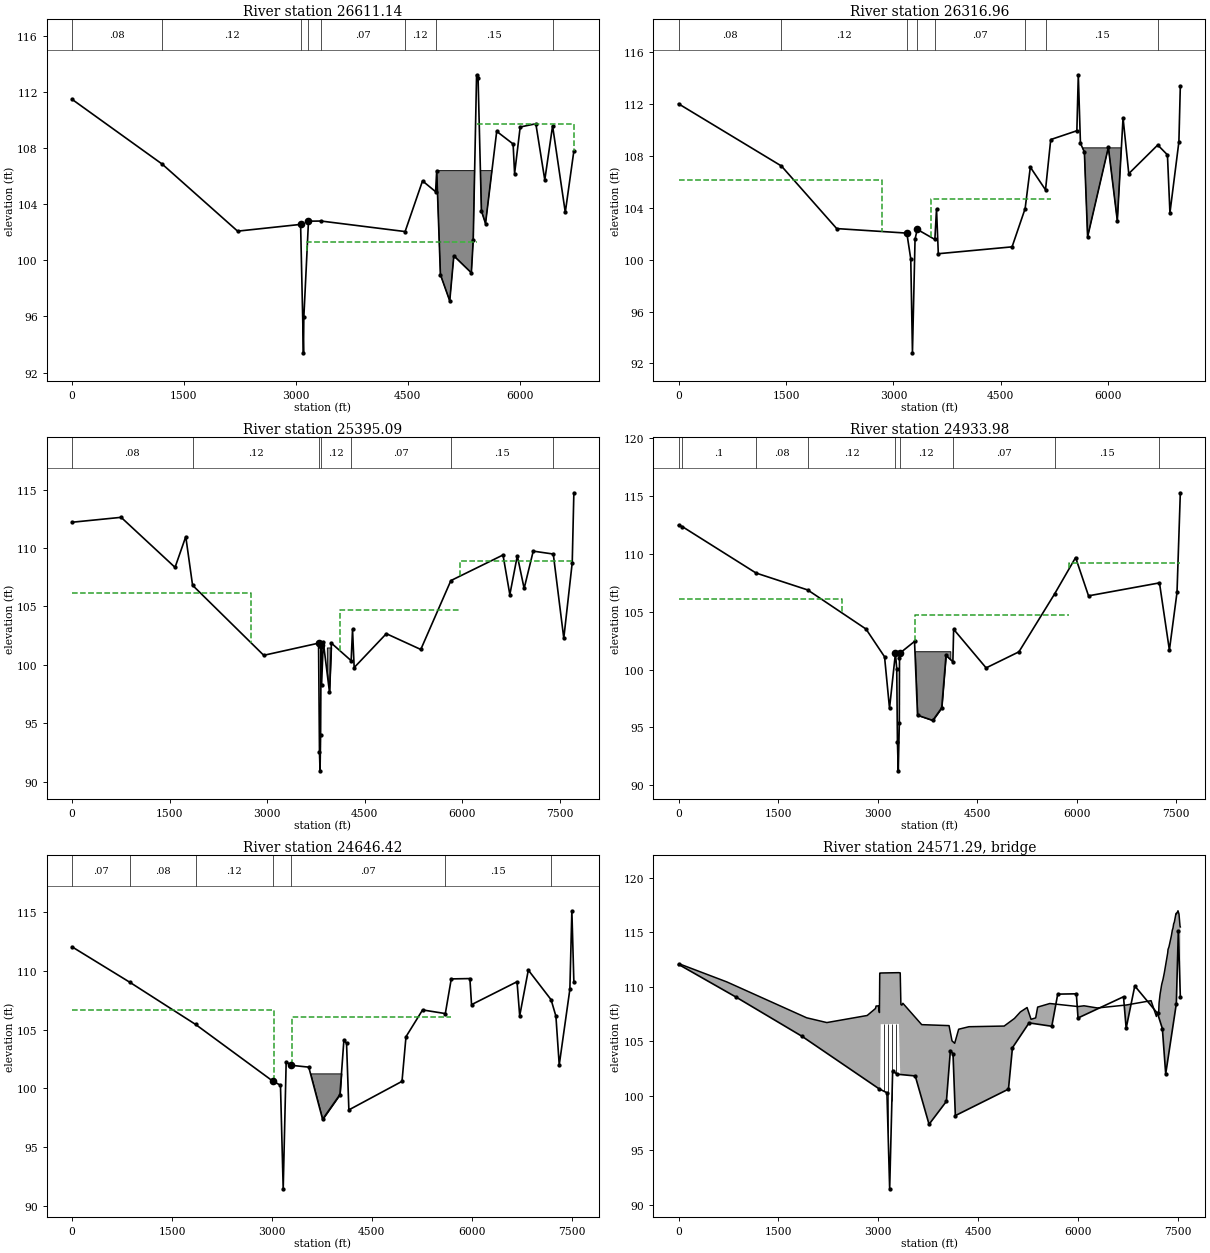
Type RM Length L Ch R = 1 ,26611.14,240.4,294.18,436.75
BEGIN DESCRIPTION:
Downstream Section - GROESCHKE RD
END DESCRIPTION:
XS GIS Cut Line= 6
3017078.6218634413856741.43760553017218.75084828 13853685.292143
3017221.7560916113853642.06191453017226.4152030213853575.0446601
3017230.2865863613853385.29799233017326.5295041113850018.1721807
#Sta/Elev= 30
       0  111.47 1209.73  106.85 2219.54  102.08 3064.18  102.56  3102.7   93.41
  3107.5   95.93 3169.88  102.79 3338.19   102.8  4465.4  102.05 4699.05  105.66
 4874.43  104.89 4888.96  106.39 4938.93   98.98 5063.87   97.11 5118.84  100.32
 5353.73   99.11 5378.72  101.43  5423.7  113.22 5443.69  112.98 5488.67  103.52
 5543.64  102.62 5693.57  109.19 5913.46  108.29 5933.45  106.18 6008.41   109.5
 6218.31  109.73 6338.25  105.73 6442.86  109.58 6613.12  103.42 6728.06  107.79
#Mann= 8 ,-1 , 0
       0     .08       0 1209.73     .12       0 3064.18     .06       0
 3169.88     .12       0 3338.19     .07       0  4465.4     .12       0
 4874.43     .15       0 6442.86     .12       0
#XS Ineff= 3 ,-1
       0 3058.73  102.24 3150.57  5423.7  101.29  5423.7 6728.06  109.74
Permanent Ineff=
       F       F       F
#Block Obstruct= 1 ,-1
 4888.96 5668.58  106.39
Bank Sta=3064.18,3169.88
XS Rating Curve= 0 ,0
Exp/Cntr=0.5,0.3

Type RM Length L Ch R = 1 ,26316.96,325.67,921.87,827.32
XS GIS Cut Line= 5
3017153.6705978713856969.32724163017491.0800280313853799.9398796
3017512.3900247813853651.95001813017672.9881287813852853.0871145
3017784.3205832813850001.4980014
#Sta/Elev= 30
       0  112.03 1436.19  107.23 2208.12   102.4 3187.29  102.05 3242.11  100.06
  3265.7   92.81 3301.92  101.57 3331.82  102.34 3578.71  101.56 3601.76  103.91
 3626.75  100.46 4656.45  100.99 4838.66  103.94 4911.35  107.14 5123.42  105.39
 5196.23  109.27 5561.08  109.95 5581.07  114.27 5611.06  108.98 5666.04  108.31
 5711.02  101.76  6000.9  108.67 6125.85     103 6205.82  110.95 6285.78  106.64
 6690.11  108.85 6825.56  108.09 6860.55  103.62  6985.5   109.1 7005.49   113.4
#Mann= 8 ,-1 , 0
       0     .08       0 1436.19     .12       0 3187.29     .06       0
 3331.82     .12       0 3578.71     .07       0 4838.66     .12       0
 5123.42     .15       0 6690.11     .12       0
#XS Ineff= 3 ,-1
       0 2846.17  106.13 3529.18 5196.23  104.69 5196.23 7005.49  109.27
Permanent Ineff=
       F       F       F
#Block Obstruct= 1 ,-1
 5611.06 6200.82  108.63
Bank Sta=3187.29,3331.82
XS Rating Curve= 0 ,0
Exp/Cntr=0.3,0.1

Type RM Length L Ch R = 1 ,25395.09,770.48,461.11,261.4
XS GIS Cut Line= 5
3017554.5690742713857408.40641593017749.6044453513854246.9320959
3018134.45013236  13853880.650023018322.99995211 13853832.409959
3018403.63627377 13850009.697132
#Sta/Elev= 30
       0   112.2   754.4  112.62 1583.74  108.34 1748.61  110.97 1853.22  106.81
 2947.66  100.82 3790.72  101.86 3804.75   92.54 3813.69   90.94 3822.25      94
 3829.86  101.69  3837.1   98.29 3863.45  101.96 3958.37   97.69 3988.36  101.86
 4292.06  100.36 4313.23  103.05 4338.22   99.77 4833.03  102.67 5362.82  101.32
 5825.58  107.21 6627.33   109.4 6732.29  106.01 6847.24  109.33  6952.2  106.54
 7092.15  109.73 7400.56  109.48 7561.96  102.28 7691.91  108.75  7716.9  114.72
#Mann= 7 ,-1 , 0
       0     .08       0 1853.22     .12       0 3790.72     .06       0
 3829.86     .12       0 4292.06     .07       0 5825.58     .15       0
 7400.56     .12       0
#XS Ineff= 3 ,-1
       0 2757.96  106.13 4119.72 5972.58  104.69 5972.58  7716.9   108.9
Permanent Ineff=
       F       F       F
#Block Obstruct= 1 ,-1
 3918.39 3988.36  101.49
Bank Sta=3790.72,3829.86
XS Rating Curve= 0 ,0
Exp/Cntr=0.3,0.1

Type RM Length L Ch R = 1 ,24933.98,585.34,287.56,138.2
XS GIS Cut Line= 4
3018186.9385444413857532.49409433018348.4999011213854356.5001182
3018481.2506198613854130.48285373018538.6366599513850009.6987724
#Sta/Elev= 30
       0  112.48   58.34  112.36 1168.87  108.35 1946.62  106.89 2825.66  103.51
 3105.23  101.11 3180.12   96.65 3269.14  101.41 3288.92  100.09 3299.48   93.75
  3312.1   91.25 3327.66   95.35 3330.53     101 3333.43  101.41 3557.13  102.44
 3602.09   96.06 3831.87   95.61 3966.75    96.7 4031.69  101.23 4135.04  100.68
 4146.58  103.49 4636.12  100.15 5130.66  101.54 5667.79  106.54 5984.87  109.69
 6179.68  106.38  7249.1   107.5 7398.55  101.69 7513.44  106.68 7563.39  115.29
#Mann= 9 ,-1 , 0
       0     .08       0   58.34      .1       0 1168.87     .08       0
 1946.62     .12       0 3269.14     .06       0 3333.43     .12       0
 4135.04     .07       0 5667.79     .15       0  7249.1     .12       0
#XS Ineff= 3 ,-1
       0 2459.72  106.13 3557.13 5889.95  104.69 5889.95 7563.39  109.26
Permanent Ineff=
       F       F       F
#Block Obstruct= 1 ,-1
 3557.13 4096.63  101.59
Bank Sta=3269.14,3333.43
XS Rating Curve= 0 ,0
Exp/Cntr=0.5,0.3

Type RM Length L Ch R = 1 ,24646.42,136.69,174.3,267.88
BEGIN DESCRIPTION:
Upstream Section - BARKER CYPRESS RD
END DESCRIPTION:
Node Name=G
XS GIS Cut Line= 6
3018848.8712756913857468.4305741 3018893.024730713855230.2552604
3018829.8303032813854858.03290783018597.5223689413854002.8987913
3018556.2606404413853662.60025933018681.85389319 13849980.437348
#Sta/Elev= 30
       0  112.04  868.24  109.02 1853.19  105.44  3010.9  100.62 3128.82  100.26
 3169.78   91.44 3214.38  102.25 3283.76  101.96 3553.68   101.8    3761   97.36
 4021.72   99.47 4081.19  104.12 4120.85  103.82 4155.71   98.16 4953.37  100.59
  5013.2  104.39 5262.46  106.67 5603.73  106.36 5692.95  109.31 5972.45  109.34
 5997.41  107.12 6680.41  109.07 6720.21  106.17 6849.65  110.06 7191.55  107.54
 7263.92  106.14 7313.83  101.99 7473.55  108.43 7503.49  115.11 7533.44  109.08
#Mann= 7 ,-1 , 0
       0     .07       0  868.24     .08       0 1853.19     .12       0
  3010.9     .06       0 3283.76     .07       0 5603.73     .15       0
 7191.55     .12       0
#XS Ineff= 3 ,-1
       0 3035.72   106.7 3308.54 5692.95  106.09 5692.95 7533.44   107.5
Permanent Ineff=
       F       F       F
#Block Obstruct= 1 ,-1
 3560.41 4046.43101.2673
Bank Sta=3010.9,3283.76
XS Rating Curve= 0 ,0
Exp/Cntr=0.5,0.3

Type RM Length L Ch R = 3 ,24571.29,,,
BEGIN DESCRIPTION:
BARKER CYPRESS RD
END DESCRIPTION:
Node Name=BARKER CYPRESS
Bridge Culvert--1,0,-1,-1, 0
Deck Dist Width WeirC Skew NumUp NumDn MinLoCord MaxHiCord MaxSubmerge Is_Ogee
24,130.5,2.6,0, 60, 60, , , 0.98, 0, 0,0,,
       0   24.52  726.03 1923.35 2226.19 2832.17 2956.28 2966.21 3000.97 3015.86
 3020.83 3025.79 3035.72 3298.63 3308.54 3328.36 3338.28 3353.14 3368.01 3650.67
 4061.37 4105.98 4145.74 4205.57 4360.11 4888.56 5043.11 5132.84 5232.55 5292.38
 5361.78 5391.43 5574.29 5997.41 6087.25 6286.89 6720.21 7094.21 7174.07 7189.05
 7209.01    7214 7228.98 7253.93  7273.9 7293.86 7343.78 7348.77 7363.74 7398.68
 7413.65 7423.63 7433.62  7443.6 7468.56 7478.54  7498.5 7513.48 7528.45 7533.44
  111.94  112.06  110.43  107.14   106.7  107.35  107.99  108.22  108.23  107.62
  111.24  111.24  111.25  111.28  111.28  111.26  108.35   108.3  108.47  106.51
  106.42  105.02   104.8  106.09  106.32  106.38  107.08  107.68  108.08     107
  107.13  108.12  108.45  108.17  108.24  108.04  108.31  108.71  107.26  107.54
  107.75  108.48  109.29  110.21  110.68  111.29  113.09  113.41  113.67  114.66
  115.19  115.38  115.77  115.92  116.72   116.7  116.96  116.66  115.57  115.48
       0       0       0       0       0       0       0       0       0       0
       0       0  106.55  106.58  106.58       0       0       0       0       0
       0       0       0       0       0       0       0       0       0       0
       0       0       0       0       0       0       0       0       0       0
       0       0       0       0       0       0       0       0       0       0
       0       0       0       0       0       0       0       0       0       0
       0   24.52  726.03 1923.35 2226.19 2832.17 2956.28 2966.21 3000.97 3015.86
 3020.83 3025.79 3035.72 3298.63 3308.54 3328.36 3338.28 3353.14 3368.01 3650.67
 4061.37 4105.98 4145.74 4205.57 4360.11 4888.56 5043.11 5132.84 5232.55 5292.38
 5361.78 5391.43 5574.29 5997.41 6087.25 6286.89 6720.21 7094.21 7174.07 7189.05
 7209.01    7214 7228.98 7253.93  7273.9 7293.86 7343.78 7348.77 7363.74 7398.68
 7413.65 7423.63 7433.62  7443.6 7468.56 7478.54  7498.5 7513.48 7528.45 7533.44
  111.94  112.06  110.43  107.14   106.7  107.35  107.99  108.22  108.23  107.62
  111.24  111.24  111.25  111.28  111.28  111.26  108.35   108.3  108.47  106.51
  106.42  105.02   104.8  106.09  106.32  106.38  107.08  107.68  108.08     107
  107.13  108.12  108.45  108.17  108.24  108.04  108.31  108.71  107.26  107.54
  107.75  108.48  109.29  110.21  110.68  111.29  113.09  113.41  113.67  114.66
  115.19  115.38  115.77  115.92  116.72   116.7  116.96  116.66  115.57  115.48
       0       0       0       0       0       0       0       0       0       0
       0       0  106.51  106.54  106.54       0       0       0       0       0
       0       0       0       0       0       0       0       0       0       0
       0       0       0       0       0       0       0       0       0       0
       0       0       0       0       0       0       0       0       0       0
       0       0       0       0       0       0       0       0       0       0
Pier Skew, UpSta & Num, DnSta & Num=  ,3088.68, 2 ,3088.68, 2 , 0 , 0 , 0 ,,
     1.4     1.4
      90     107
     1.4     1.4
      90     107
Pier Skew, UpSta & Num, DnSta & Num=  ,3145.88, 2 ,3145.88, 2 , 0 , 0 , 0 ,,
     1.4     1.4
      90     107
     1.4     1.4
      90     107
Pier Skew, UpSta & Num, DnSta & Num=  ,3203.08, 2 ,3203.08, 2 , 0 , 0 , 0 ,,
     1.4     1.4
      90     107
     1.4     1.4
      90     107
Pier Skew, UpSta & Num, DnSta & Num=  ,3260.48, 2 ,3260.48, 2 , 0 , 0 , 0 ,,
     1.4     1.4
      90     107
     1.4     1.4
      90     107
BR Coef=-1 , 1 , 1 ,0.9, 0 ,,,0.8,0,1.2,0,
WSPro=,,,, 1 ,,,, 0 ,,,, 0 ,,,,-1 ,-1 ,-1 , 0 , 0 , 0 , 0 , 0
BC Design=,, 0 ,, 0 ,,,,,,
BC Use User HTab Curves=0
BC User HTab FreeFlow(D)= 0