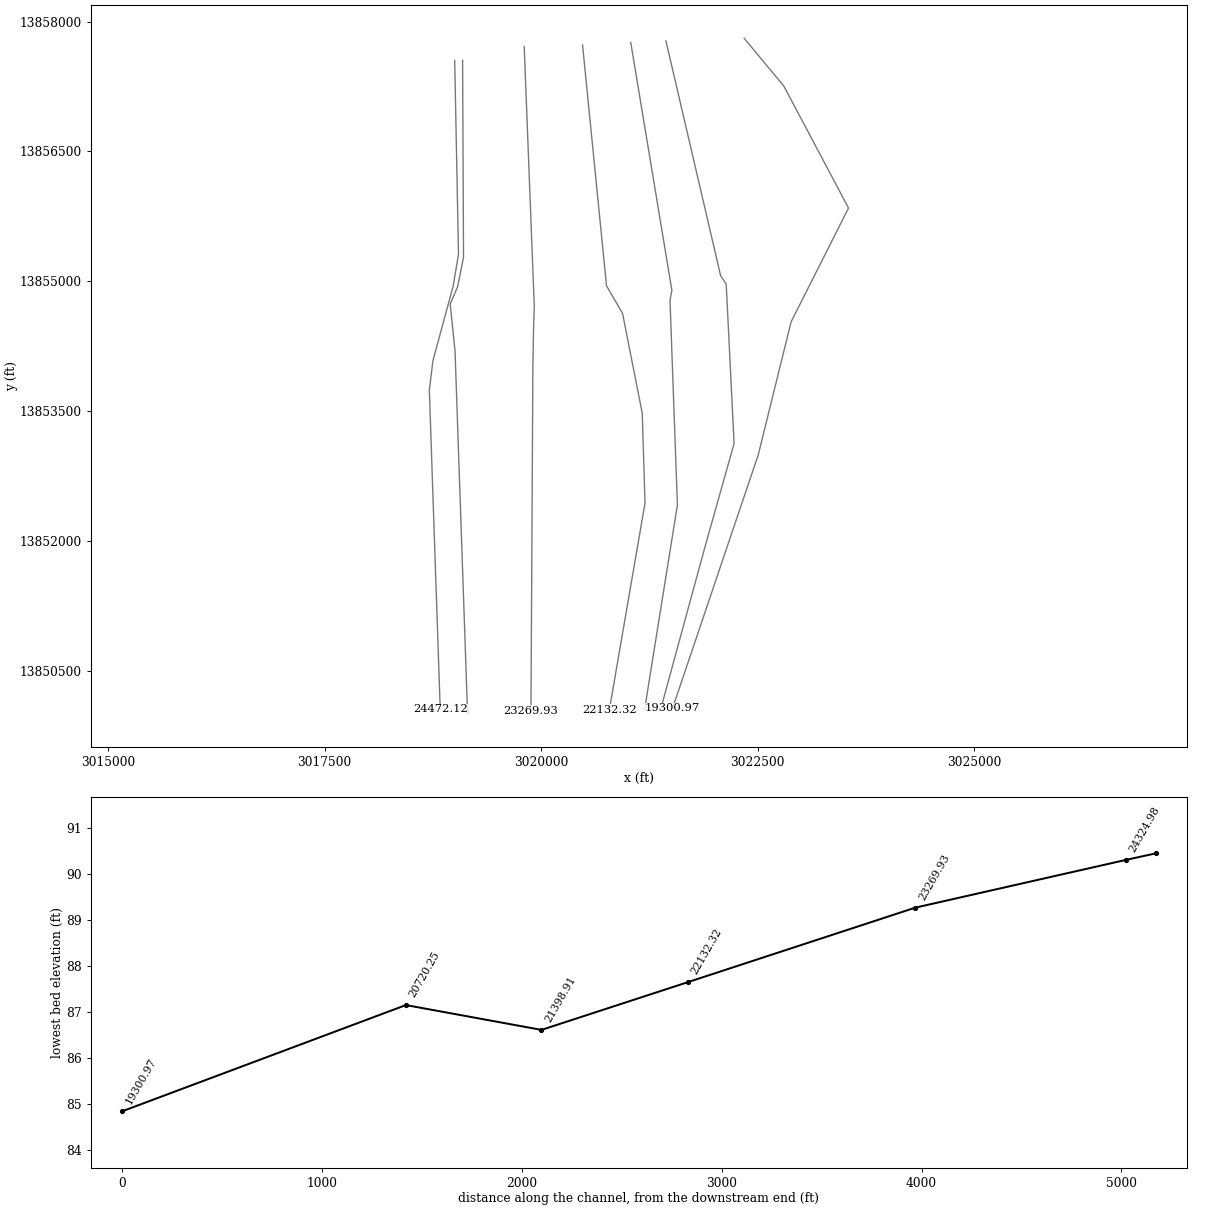
HEC-RAS study U101-00-00.prj: U101-00-00 2019 (Re-Study)

--- U101-00-00.g01 (geometry) --- (continued)

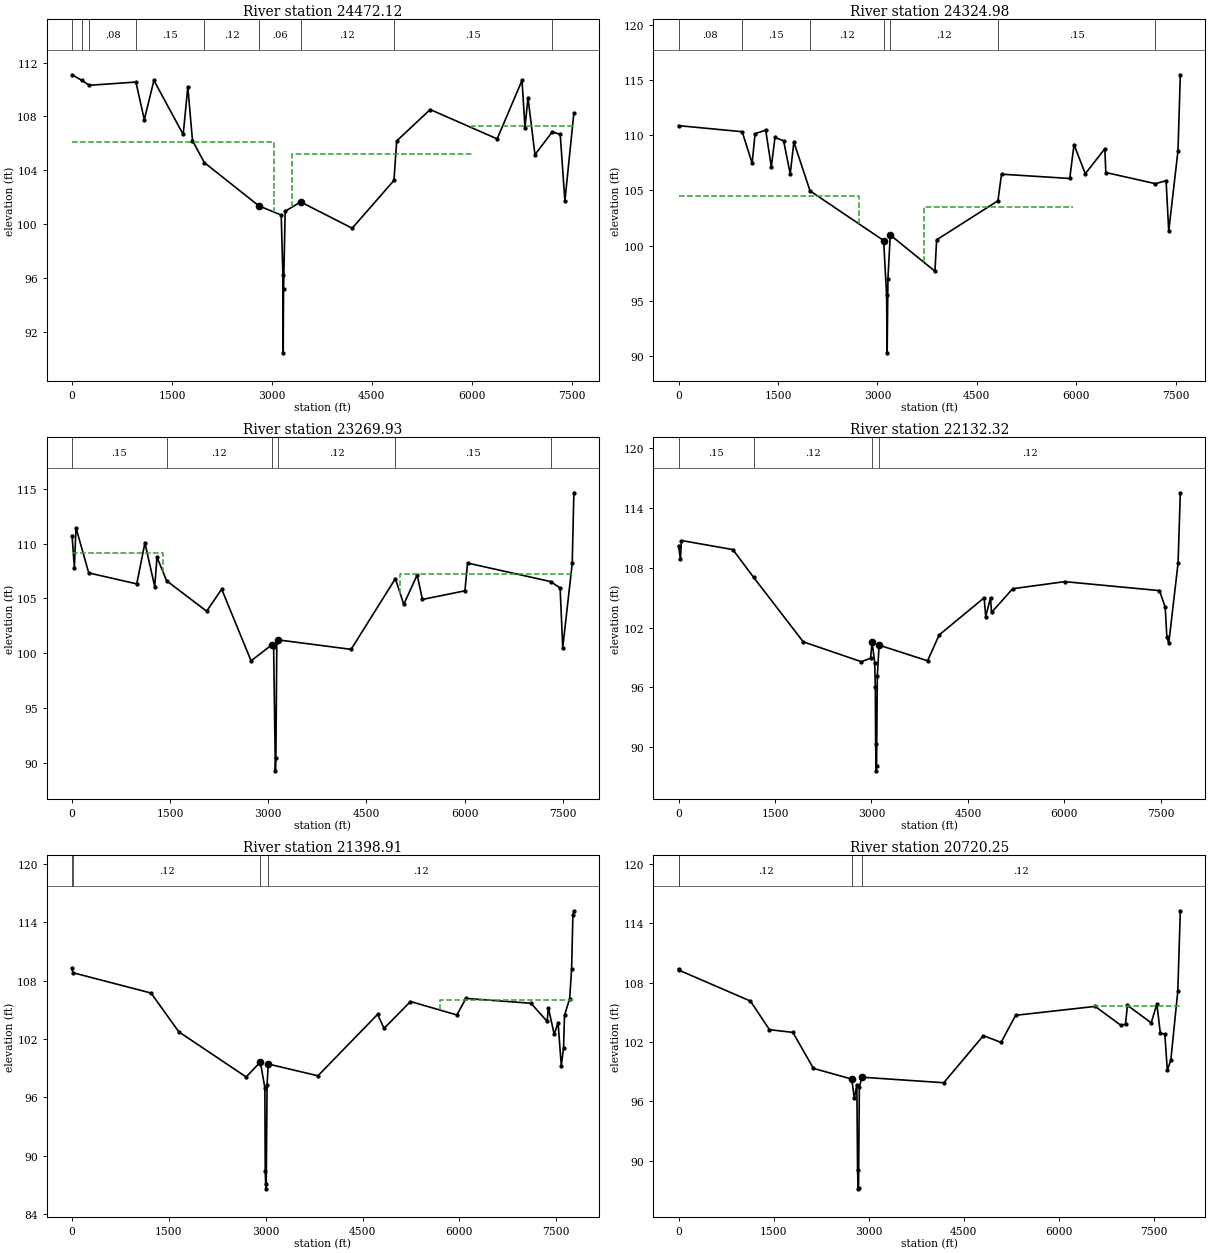
Type RM Length L Ch R = 1 ,24472.12,53.29,147.14,353.32
BEGIN DESCRIPTION:
Downstream Section - BARKER CYPRESS RD
END DESCRIPTION:
XS GIS Cut Line= 6
 3019000.246629113857550.44254923019044.4000841113855312.2672355
3018981.2056566913854940.04488283018748.8977223613854084.9107663
3018707.6359938513853744.61223443018833.2292466213850062.4493231
#Sta/Elev= 30
       0  111.09  148.73  110.67  258.58  110.31  958.36  110.55 1084.41  107.76
 1228.95  110.67 1668.18  106.66 1738.05  110.19 1807.93   106.2 1986.02  104.57
 2807.36  101.35 3139.99  100.68 3164.82   96.25 3169.78   90.45 3174.74   95.16
 3199.52  100.96 3431.74  101.65 4205.57    99.7 4832.78  103.25 4873.61  106.18
 5376.61  108.51 6381.72  106.33 6754.95  110.67 6799.73  107.17 6844.65  109.39
 6949.47  105.16 7210.69  106.86  7328.8  106.66 7398.68  101.73 7533.44  108.24
#Mann= 9 ,-1 , 0
       0     .08       0  148.73     .07       0  258.58     .08       0
  958.36     .15       0 1986.02     .12       0 2807.36     .06       0
 3431.74     .12       0 4832.78     .15       0 7210.69     .12       0
#XS Ineff= 3 ,-1
       0 3035.72   106.1 3308.54 6007.39   105.2 6007.39 7533.44  107.26
Permanent Ineff=
       F       F       F
Bank Sta=2807.36,3431.74
XS Rating Curve= 0 ,0
Exp/Cntr=0.5,0.3

Type RM Length L Ch R = 1 ,24324.98,839.83,1055.05,948.95
Node Name=F
XS GIS Cut Line= 6
3019091.53680086 13857553.6544853019102.2339579513855278.7295729
3019034.4854057713854939.98714023018948.3812472813854738.8717288
3019004.3981956113854192.02242883019148.6177234513850013.4549985
#Sta/Elev= 30
       0  110.86  960.31  110.31 1109.98  107.45 1154.97  110.13 1314.97  110.45
 1399.97  107.14 1454.97  109.79 1584.96  109.49 1684.96  106.49 1739.96  109.38
 1983.65  104.96 3094.04  100.47 3139.02   95.51 3147.15   90.31 3159.01   97.01
 3193.99  100.97 3868.44   97.69 3893.41  100.53 4818.24  104.06 4872.51  106.47
 5901.56  106.08  5966.5  109.14 6136.35  106.51 6431.08  108.77 6446.06  106.62
 7194.59  105.61 7355.23  105.88 7395.19  101.33 7535.06  108.61 7570.03  115.46
#Mann= 7 ,-1 , 0
       0     .08       0  960.31     .15       0 1983.65     .12       0
 3094.04     .06       0 3193.99     .12       0 4818.24     .15       0
 7194.59     .12       0
#XS Ineff= 3 ,-1
       0 2729.79   104.5 3704.43 5951.52   103.5 5951.52 7570.03  107.82
Permanent Ineff=
       F       F       F
Bank Sta=3094.04,3193.99
XS Rating Curve= 0 ,0
Exp/Cntr=0.3,0.1

Type RM Length L Ch R = 1 ,23269.93,860.85,1137.61,1181.89
Node Name=E
XS GIS Cut Line= 5
 3019802.776848213857710.59347563019919.1201194413854707.2100467
3019911.44985919 13854497.8298883019902.8501388613854033.3301609
3019880.6598945313850043.7200298
#Sta/Elev= 30
       0  110.73   34.95   107.8   59.91  111.44  254.63  107.32  988.56  106.32
 1113.38  110.05 1263.17  106.08 1298.11  108.76 1445.22   106.6 2057.01  103.83
 2286.68  105.84 2736.03    99.3 3050.54  100.75 3080.47  100.58 3107.41   89.27
 3115.24   90.41 3129.31  100.99 3140.34  101.22  4264.7  100.35  4941.7   106.8
 5069.62  104.45  5274.6  107.14  5354.6   104.9 6004.53  105.69 6044.53  108.22
 7315.54  106.53 7459.39  105.94 7499.39  100.51 7644.37   108.2 7669.37  114.63
#Mann= 6 ,-1 , 0
       0     .15       0 1445.22     .12       0 3050.54     .06       0
 3140.34     .12       0  4941.7     .15       0 7315.54     .12       0
#XS Ineff= 2 ,-1
       0 1392.98  109.14 5019.63 7669.37  107.25
Permanent Ineff=
       F       F
Bank Sta=3050.54,3140.34
XS Rating Curve= 0 ,0
Exp/Cntr=0.3,0.1

Type RM Length L Ch R = 1 ,22132.32,719.04,733.41,504.02
Node Name=D
XS GIS Cut Line= 6
3020476.1941365313857730.30340993020752.8700923613854949.3299693
3020937.7998406113854631.16000193021165.2400025313853478.7899314
3021197.3819986113852441.06726933020785.5471923613850054.0307048
#Sta/Elev= 30
       0   110.2      30  108.86      45  110.72  844.91  109.81 1168.68  107.02
 1939.79  100.57 2843.75   98.58 2986.16   98.93 3010.75  100.52 3050.11    98.5
 3060.17   96.04  3065.2   90.29 3073.31   87.65 3079.26    88.1 3091.18   97.13
 3118.99  100.24 3872.94   98.67 4052.88  101.26 4752.08  104.98 4777.04   103.1
 4851.92     105 4866.89  103.51 5196.33  105.89 6005.31   106.6 7478.65   105.7
 7568.55  104.04 7593.52  101.07 7623.49  100.44 7768.32  108.46 7803.28   115.5
#Mann= 4 ,-1 , 0
       0     .15       0 1168.68     .12       0 3010.75     .06       0
 3118.99     .12       0
#XS Ineff= 1 ,-1
 6005.31 7803.28   106.6
Permanent Ineff=
       F
Bank Sta=3010.75,3118.99
XS Rating Curve= 0 ,0
Exp/Cntr=0.3,0.1

Type RM Length L Ch R = 1 ,21398.91,596.08,678.65,710.26
Node Name=C
XS GIS Cut Line= 5
3021032.39184302 13857758.5910833021507.5598559413854895.7598664
3021485.6399522713854785.03994353021571.1555292813852418.6201357
3021192.3357488713850057.6750544
#Sta/Elev= 30
       0  109.32   11.59  108.81 1223.74  106.72 1653.29  102.74 2697.21    98.1
 2916.72   99.63 2986.61      97  2992.5   88.46 3001.99   86.61 3008.28   87.12
 3020.87   97.26 3039.84   99.43 3809.17   98.22 4733.36  104.53 4833.27  103.09
 5242.91  105.85 5961.84  104.47 6101.61  106.17 7109.97  105.67 7359.56  103.81
 7379.53  105.19 7469.38  102.48 7529.28  103.68  7579.2   99.26 7614.15  101.08
 7629.12  104.43 7708.99  106.15 7738.94  109.16 7758.91  114.75 7773.89  115.17
#Mann= 4 ,-1 , 0
       0     .07       0   11.59     .12       0 2916.72     .06       0
 3039.84     .12       0
#XS Ineff= 1 ,-1
 5697.27 7773.89     106
Permanent Ineff=
       F
Bank Sta=2916.72,3039.84
XS Rating Curve= 0 ,0
Exp/Cntr=0.3,0.1

Type RM Length L Ch R = 1 ,20720.25,1428.23,1419.29,902.29
Node Name=B
XS GIS Cut Line= 6
3021438.6886026113857776.29281933022069.9301222713855066.7798656
3022134.6101110313854968.11011543022225.4908347713853127.9635333
 3021893.731327713851950.68832883021380.7546633613850071.2485181
#Sta/Elev= 30
       0  109.38   15.19  109.24 1133.81  106.14 1433.49  103.25 1803.11  102.97
 2127.77   99.33 2732.12   98.25 2772.08   96.29 2812.06   97.68 2823.73   89.01
 2833.16   87.15  2838.9   87.28 2851.48   97.41 2890.22   98.44 4183.23   97.88
 4807.36  102.64 5086.93  101.96 5316.58   104.7 6570.02   105.6 6979.65  103.67
 7049.58  103.81 7079.56  105.71 7454.21  103.94 7544.13  105.83 7599.08  102.88
 7669.01  102.79 7708.98   99.14 7763.93  100.17 7873.82  107.14 7913.79  115.27
#Mann= 4 ,-1 , 0
       0     .07       0   15.19     .12       0 2732.12     .06       0
 2890.22     .12       0
#XS Ineff= 1 ,-1
 6545.05 7913.79   105.6
Permanent Ineff=
       F
Bank Sta=2732.12,2890.22
XS Rating Curve= 0 ,0
Exp/Cntr=0.3,0.1

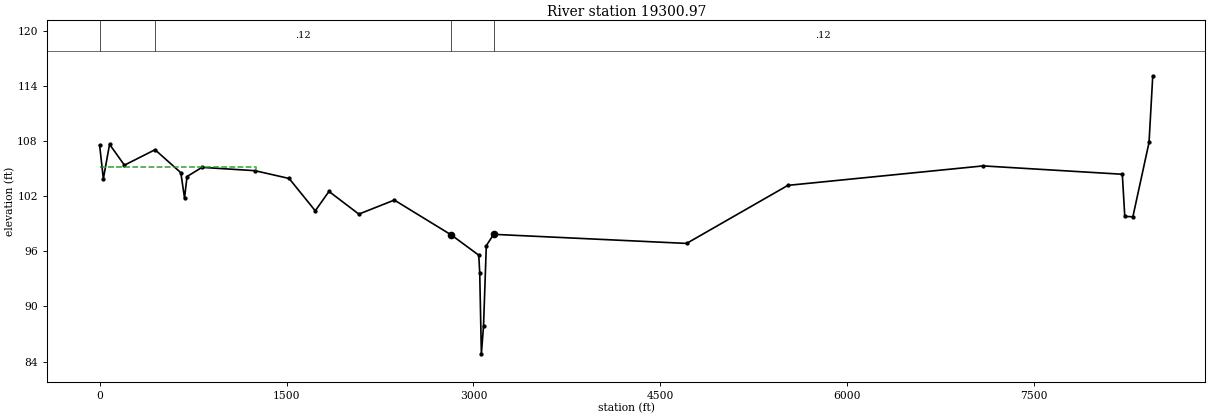
Type RM Length L Ch R = 1 ,19300.97,0,0,0
Node Name=A
XS GIS Cut Line= 6
3022342.0532656913857805.85739273022799.5661301913857254.9254237
3023546.5360929413855846.91478833022883.8523789513854533.3248958
 3022504.623806713852999.01037913021515.7160076113850074.0798773
#Sta/Elev= 30
       0  107.54   29.84  103.89   79.57  107.65  198.93  105.38  444.49  107.06
  651.48  104.56  681.32   101.8  701.21  104.14  821.06  105.14 1245.76  104.78
 1520.57  103.93 1730.42  100.41 1840.34  102.52 2080.17  100.05 2364.83  101.58
 2823.27   97.77 3042.44   95.58 3049.96   93.69 3063.41   84.84 3080.75   87.91
 3102.95   96.61 3161.48   97.85 4710.21   96.86 5522.99  103.18  7089.4   105.3
 8206.63  104.39 8226.58    99.8 8291.42   99.76 8421.08  107.85 8451.01  115.11
#Mann= 4 ,-1 , 0
       0     .07       0  444.49     .12       0 2823.27     .06       0
 3161.48     .12       0
#XS Ineff= 2 , 0
       0 1255.75  105.13  7089.4       0   105.3
Permanent Ineff=
       F       F
Bank Sta=2823.27,3161.48
XS Rating Curve= 0 ,0
Exp/Cntr=0.3,0.1

Chan Stop Cuts=-1
Use User Specified Reach Order=0
Composite Channel Slope=5